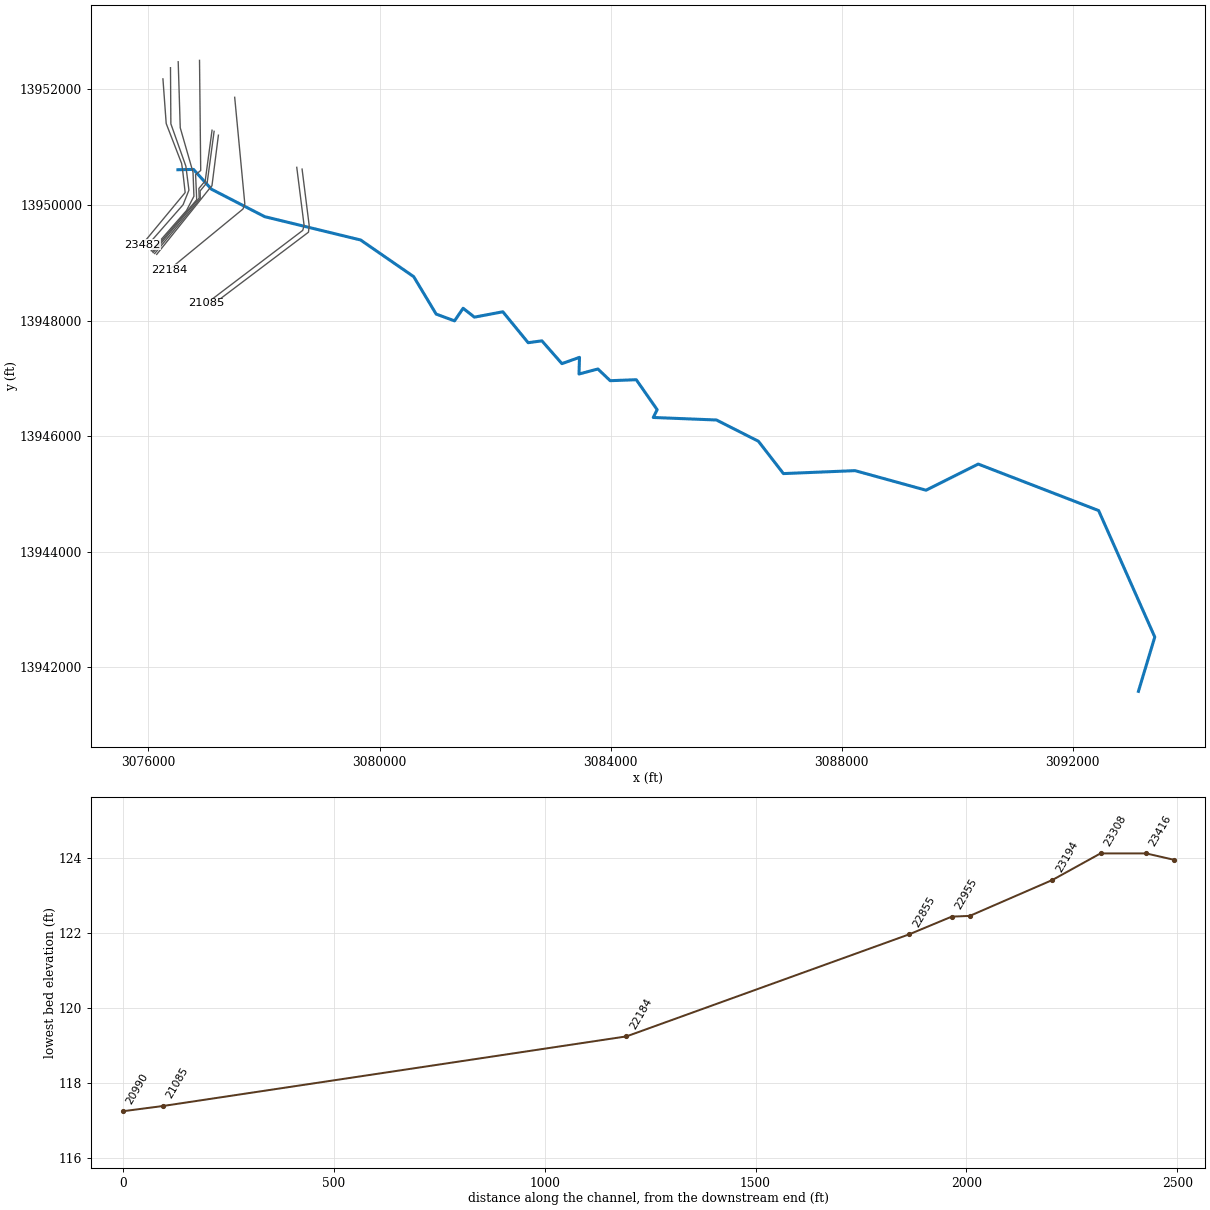
--- K124-00-00.prj (project) ---

Proj Title=K124-00-00
Current Plan=p08
Default Exp/Contr=.3,.1
English Units
Geom File=g05
Flow File=f07
Flow File=f05
Plan File=p07
Plan File=p08
Y Axis Title=Elevation
X Axis Title(PF)=Main Channel Distance
X Axis Title(XS)=Station
BEGIN DESCRIPTION:
Cypress Creek Watershed
Seals Gully
HCFCD Unit K124-00-00
Flood Hazard Model
10, 2, 1, 0.2%
Filename K124-00-00
Prepared by: Halff Associates  DATE:  03/26/04
Reviewed by:  _________  DATE:  __________________
STATUS (FINAL)
END DESCRIPTION:
DSS Export Rating Curves= 0
DSS Export Rating Curve Sorted= 0
DSS Export Volume Flow Curves= 0
DXF OffsetX= 0
DXF OffsetY= 0
DXF ScaleX= 1
DXF ScaleY= 10

--- K124-00-00.p08 (plan) ---

Plan Title=Effective FW 2013
Version=Version 3.0.1  May 2012
Short Identifier=Eff+LOMR FW
Geom File=g05
Flow File=f05
Subcritical Flow
K Sum by GR= 0
Std Step Tol= 0.01
Critical Tol= 0.01
Num of Std Step Trials= 20
Max Error Tol= 0.3
Flow Tol Ratio= 0.001
Split Flow NTrial= 30
Split Flow Tol= 0.02
Split Flow Ratio= 0.02
Log Output Level= 0
Friction Slope Method= 1
Unsteady Friction Slope Method= 2
Parabolic Critical Depth
Global Vel Dist= 0 , 0 , 0
Global Log Level= 0
CheckData=True
Encroach Param=-1 ,0,0, 2
Encroach River=K124-00-00
Encroach Reach=K124-00-00_0017
Encroach Node=23482
       1 4950.46    5100
Encroach Node=23416
       1    4933    5100
Encroach Node=23362
       1 4921.75    5130
Encroach Node=23308
       1 4931.75    5150
Encroach Node=23194
       1    4940 5061.64
Encroach Node=22998
       1  4862.4    5029
Encroach Node=22976.5
       1    4900    5029
Encroach Node=22955
       1  4967.7    5029
Encroach Node=22855
       1  4978.2    5028
Encroach Node=22184
       1  4939.6  5042.7
Encroach Node=21085
       1  4945.9  5049.7
Encroach Node=20990
       1  4949.3  5037.3
Encroach Node=20960.5
       1  4949.3  5037.3
Encroach Node=20931
       1  4949.3  5037.3
Encroach Node=20828
       1  4955.2  5045.2
Encroach Node=19675
       1  4972.6  5065.6
Encroach Node=19575
       1  4972.6  5065.6
Encroach Node=19556.5
       1  4972.6  5065.6
Encroach Node=19538
       1  4972.6  5065.6
Encroach Node=19488
       1  4958.4  5051.6
Encroach Node=18891
       1    4949  5048.2
Encroach Node=18788
       1  4955.1  5055.1
Encroach Node=18769
       1  4955.1  5065.1
Encroach Node=18750
       1  4955.1  5055.1
Encroach Node=18650
       1  4964.9  5044.9
Encroach Node=18506
       1  4956.1  5048.8
Encroach Node=18408
       1  4920.3  5043.1
Encroach Node=18398
       1  4925.5  5042.5
Encroach Node=18388
       1  4925.5  5042.5
Encroach Node=18310
       1  4915.1  5039.9
Encroach Node=18281.5
       1  4955.1  5029.9
Encroach Node=18253
       1  4945.1  5039.9
Encroach Node=18151
       1  4953.8  5045.8
Encroach Node=18012
       1  4952.4  5052.4
Encroach Node=17990
       1  4952.4  5052.4
Encroach Node=17968
       1  4952.4  5052.4
Encroach Node=17872
       1  4937.4  5047.4
Encroach Node=17166
       1  4955.9  5024.3
Encroach Node=16045
       1     490     630
Encroach Node=15551
       1     275     400
Encroach Node=15443
       1     277     400
Encroach Node=15390
       1     306     441
Encroach Node=15351
       1     306     441
Encroach Node=15312
       1     354     505
Encroach Node=15112
       1   114.3   227.3
Encroach Node=15057
       1   141.7   255.7
Encroach Node=14812
       1     482     609
Encroach Node=14107
       1     508     623
Encroach Node=13584
       1    4915 5032.56
Encroach Node=12215
       1  4959.7  5049.7
Encroach Node=11963
       1 3487.54 3577.54
Encroach Node=11951.5
       1 3487.54 3577.54
Encroach Node=11940
       1 3442.54 3577.54
Encroach Node=11897
       1  4928.2    5056
Encroach Node=11842.5
       1  4928.2    5056
Encroach Node=11788
       1  4928.2    5056
Encroach Node=11682
       1  4949.9  5138.6
Encroach Node=10561
       1    4938  5061.1
Encroach Node=10216
       1    4938  5061.1
Encroach Node=10006
       1    4938  5061.1
Encroach Node=9900
       1    4938  5061.1
Encroach Node=9890
       1    4938  5061.1
Encroach Node=9880
       1    4938  5061.1
Encroach Node=9777
       1    4938  5061.1
Encroach Node=9308
       1  4855.4  5053.7
Encroach Node=9205
       1    4798    5097
Encroach Node=9172
       1    4798 5098.08
Encroach Node=9139
       1 4812.25 5097.97
Encroach Node=9035
       1  4940.8  5068.8
Encroach Node=8662
       1 4955.84 5038.79
Encroach Node=8561
       1 4898.19 5098.19
Encroach Node=8560
       1 4898.19 5098.19
Encroach Node=8559
       1 4898.19 5098.19
Encroach Node=8557
       1  4898.2  5098.2
Encroach Node=8529
       1  4898.2  5098.2
Encroach Node=8501
       1  4898.2  5098.2
Encroach Node=8399
       1  4942.3  5061.3
Encroach Node=7170
       1  4947.8  5032.9
Encroach Node=6441
       1  4948.2  5030.9
Encroach Node=5603
       1  4959.3  5049.4
Encroach Node=4986
       1  4907.9    5060
Encroach Node=4883
       1  4907.9    5060
Encroach Node=4871.5
       1    4880    5116
Encroach Node=4870
       1  4960.5  5044.4
Encroach Node=4860
       1  4960.5  5044.4
Encroach Node=4779
       1  4957.9  5041.5
Encroach Node=4266
       1    4885    5050
Encroach Node=3416
       1  4959.8  5059.8
Encroach Node=3253
       1  4937.4  5107.4
Encroach Node=3150
       1 4928.41  5080.3
Encroach Node=3093
       1 4928.41  5080.3
Encroach Node=3036
       1 4928.41    5075
Encroach Node=2936
       1  4928.9  5107.9
Encroach Node=1706
       1  4939.5    5037
BEGIN DESCRIPTION:
FEMA Effective Floodway 2007 + LOMR 07-06-2244P + LOMR 10-06-0320P + LOMR 12-06-2710P
END DESCRIPTION:
Computation Interval=1HOUR
Output Interval=1HOUR
Run HTab= 0
Run UNet= 0
Run PostProcess= 0
UNET Theta= 1
UNET ZTol= 0.02
UNET ZSATol= 0.1
UNET MxIter= 20
UNET MaxInSteps= 20
UNET DtIC= 0
UNET DtMin= 0
UNET MaxCRTS= 20
UNET WFStab= 2
UNET SFStab= 1
UNET WFX= 1
UNET SFX= 1
UNET Convert EG Bridges=-1
UNET Use Existing IB Tables=-1
Instantaneous Interval=1HOUR
Write IC File= 0
IC Time=0
Write Velocity= 0
Write Detailed= 0

--- K124-00-00.p07 (plan) ---

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Plan Title=Effective MP 2013
Short Identifier=Eff+LOMR MP
Geom File=g05
Flow File=f07
FEMA Effective Multi-Profile 2007 + LOMR 07-06-2244P + LOMR 10-06-0320P + LOMR 12-06-2710P

--- K124-00-00.f05 (steady flow) ---

Flow Title=Effective FW 2013
Program Version=4.10
Number of Profiles= 2
Profile Names=1PCT_100yr, 1PCTFloodway_100yrFW
River Rch & RM=K124-00-00,K124-00-00_0017 ,23482
    1903    1903
River Rch & RM=K124-00-00,K124-00-00_0017 ,22184
    2011    2011
River Rch & RM=K124-00-00,K124-00-00_0017 ,20990
    2141    2141
River Rch & RM=K124-00-00,K124-00-00_0017 ,19488
    2177    2177
River Rch & RM=K124-00-00,K124-00-00_0017 ,18788
    2260    2260
River Rch & RM=K124-00-00,K124-00-00_0017 ,15551
    3212    3212
River Rch & RM=K124-00-00,K124-00-00_0017 ,13584
    3328    3328
River Rch & RM=K124-00-00,K124-00-00_0017 ,11963
    5194    5194
River Rch & RM=K124-00-00,K124-00-00_0017 ,10561
    5319    5319
River Rch & RM=K124-00-00,K124-00-00_0017 ,9205
    5331    5331
River Rch & RM=K124-00-00,K124-00-00_0017 ,8561
    5444    5444
River Rch & RM=K124-00-00,K124-00-00_0017 ,7170
    5586    5586
River Rch & RM=K124-00-00,K124-00-00_0017 ,5603
    5610    5610
River Rch & RM=K124-00-00,K124-00-00_0017 ,4860
    5775    5775
River Rch & RM=K124-00-00,K124-00-00_0017 ,3150
    5911    5911
River Rch & RM=K124-00-00,K124-00-00_0017 ,1706
    6085    6085
Boundary for River Rch & Prof#=K124-00-00,K124-00-00_0017 , 1
Up Type= 0
Dn Type= 3
Dn Slope=0.0032
Boundary for River Rch & Prof#=K124-00-00,K124-00-00_0017 , 2
Up Type= 0
Dn Type= 3
Dn Slope=0.0032
DSS Import GetInterval= 0
DSS Import GetPeak= 0
DSS Import FillOption= 0

--- K124-00-00.f07 (steady flow) ---

Flow Title=Effective MP 2013
Version=Version 3.0.1  May 2012
Number of Profiles= 4
Profile Names=10PCT_10yr, 2PCT_50yr, 1PCT_100yr, 0.2PCT_500yr
River Rch & RM=K124-00-00,K124-00-00_0017 ,23482
     929    1542    1903    2455
River Rch & RM=K124-00-00,K124-00-00_0017 ,22184
    1012    1696    2011    2779
River Rch & RM=K124-00-00,K124-00-00_0017 ,20990
    1129    1897    2141    3234
River Rch & RM=K124-00-00,K124-00-00_0017 ,19488
    1141    1921    2177    3270
River Rch & RM=K124-00-00,K124-00-00_0017 ,18788
    1176    1957    2260    3353
River Rch & RM=K124-00-00,K124-00-00_0017 ,15551
    1765    2609    3212    4551
River Rch & RM=K124-00-00,K124-00-00_0017 ,13584
    1794    2815    3328    4860
River Rch & RM=K124-00-00,K124-00-00_0017 ,11963
    2781    4341    5194    7620
River Rch & RM=K124-00-00,K124-00-00_0017 ,10561
    2870    4453    5319    7773
River Rch & RM=K124-00-00,K124-00-00_0017 ,9205
    2890    4475    5331    7790
River Rch & RM=K124-00-00,K124-00-00_0017 ,8561
    2964    4573    5444    7919
River Rch & RM=K124-00-00,K124-00-00_0017 ,7170
    3068    4701    5586    8099
River Rch & RM=K124-00-00,K124-00-00_0017 ,5603
    3103    4735    5610    8137
River Rch & RM=K124-00-00,K124-00-00_0017 ,4860
    3222    4886    5775    8337
River Rch & RM=K124-00-00,K124-00-00_0017 ,3150
    3326    5010    5911    8507
River Rch & RM=K124-00-00,K124-00-00_0017 ,1706
    3450    5168    6085    8723
Boundary for River Rch & Prof#=K124-00-00,K124-00-00_0017 , 1
Up Type= 0
Dn Type= 3
Dn Slope=.0032
Boundary for River Rch & Prof#=K124-00-00,K124-00-00_0017 , 2
Up Type= 0
Dn Type= 3
Dn Slope=.0032
Boundary for River Rch & Prof#=K124-00-00,K124-00-00_0017 , 3
Up Type= 0
Dn Type= 3
Dn Slope=.0032
Boundary for River Rch & Prof#=K124-00-00,K124-00-00_0017 , 4
Up Type= 0
Dn Type= 3
Dn Slope=.0032
DSS Import GetInterval= 0
DSS Import GetPeak= 0
DSS Import FillOption= 0

--- K124-00-00.g05 (geometry) ---

Geom Title=K124-00-00 2013
Version=Version 3.0.1  May 2012

River Reach=K124-00-00      ,K124-00-00_0017
Reach XY= 30
      3076510.54     13950610.21      3076779.63     13950615.42
      3077091.26     13950272.54      3078012.27     13949797.71
      3079671.99     13949394.07      3080591.75       13948759.
      3080980.15     13948111.08      3081298.73     13947993.89
      3081447.17     13948211.77      3081642.48     13948058.13
      3082134.67     13948151.01      3082573.04     13947615.42
      3082810.83     13947648.13      3083157.24     13947253.44
      3083461.92     13947361.95      3083453.24     13947073.75
       3083780.5     13947160.56      3083993.17      13946958.3
      3084444.56      13946974.8      3084806.54      13946455.7
      3084738.89      13946321.4      3085832.58     13946277.75
      3086559.15     13945909.69        3086992.       13945350.
      3088231.02     13945401.01      3089460.19     13945062.47
      3090363.83     13945514.73      3092448.04     13944710.04
      3093420.26      13942520.8      3093137.27      13941580.7

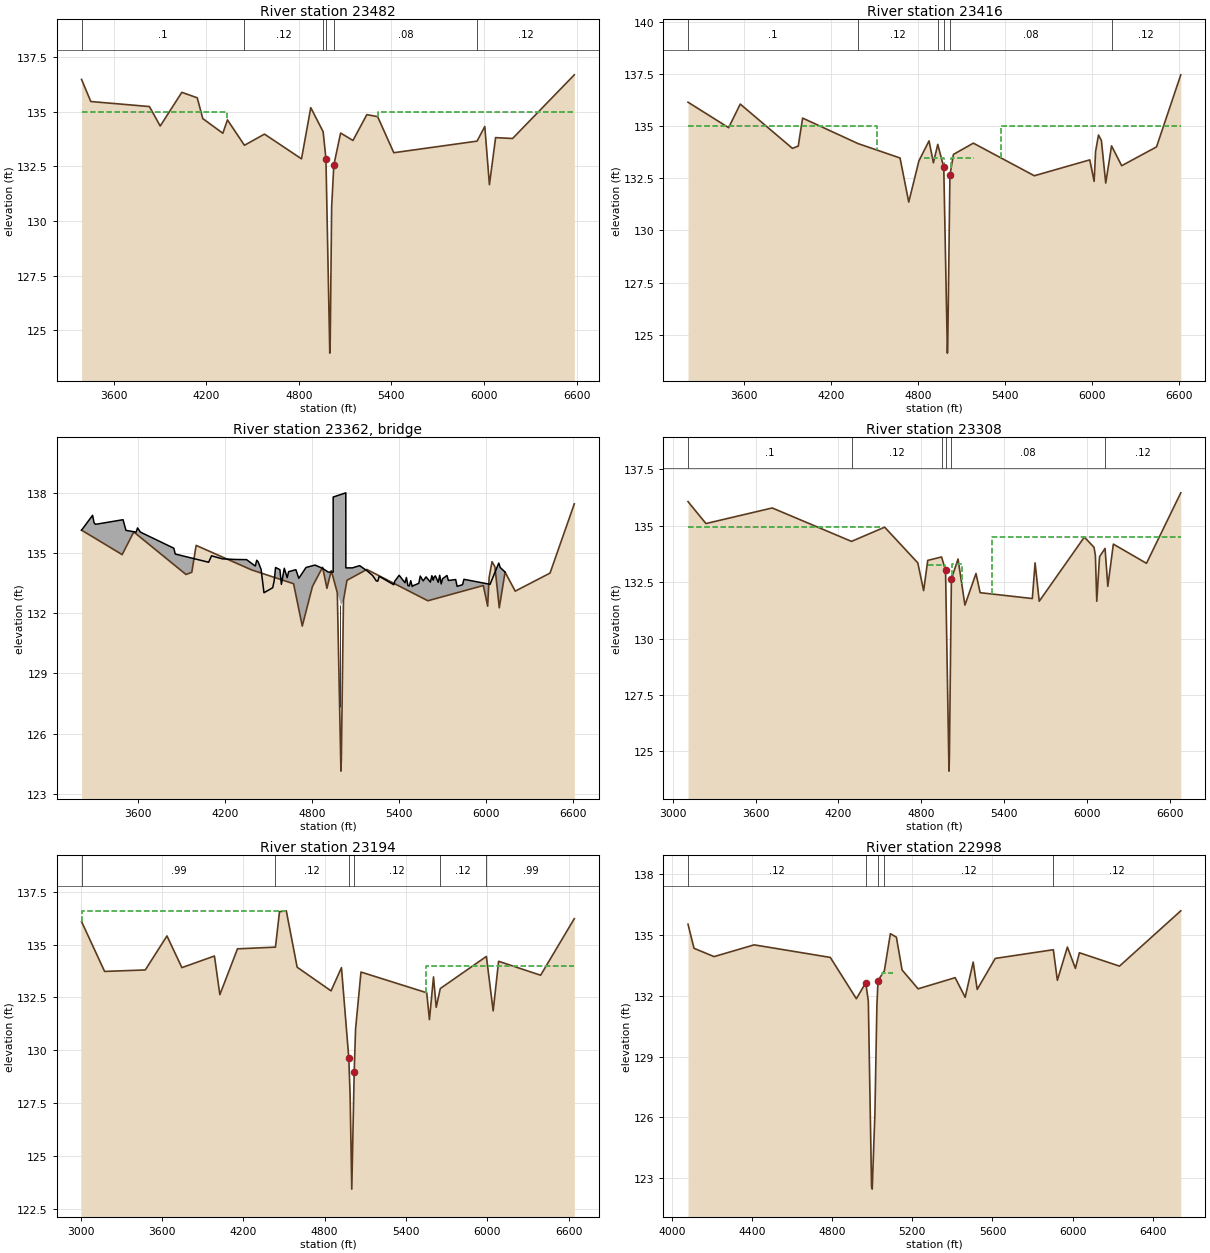
Type RM Length L Ch R = 1 ,23482   ,63.4,66,68.3
BEGIN DESCRIPTION:
S8_RHODES RD-US-XS 4
END DESCRIPTION:
XS GIS Cut Line= 6
       3076250.8       13952183.      3076307.34     13951409.46
      3076574.25       13950719.      3076591.25       13950607.
      3076635.63     13950214.82      3075889.36     13949313.39
#Sta/Elev= 30
  3391.2  136.47  3451.2  135.46  3831.2  135.23  3901.2  134.34  4041.2  135.88
  4141.2  135.63  4177.1  134.68  4307.1  134.01  4337.1  134.62  4447.1  133.46
  4577.1  133.97  4817.1  132.84  4877.1  135.18  4957.3  134.08  4975.5  132.85
  5000.4  123.96  5003.3  124.53  5012.5  130.65  5026.6  132.55  5070.6  134.02
  5150.6  133.68  5240.6  134.86  5310.6  134.77  5415.3  133.12  5955.3  133.65
  6005.3  134.32  6035.3  131.66  6075.3  133.81  6185.3  133.77  6585.6  136.68
#Mann= 6 ,-1 , 0
  3391.2      .1       0  4447.1     .12       0  4957.3     .05       0
  4975.5     .04       0  5026.6     .08       0  5955.3     .12       0
#XS Ineff= 2 , 0
       0  4337.1     135  5310.6       0     135
Permanent Ineff=
       F       F
Bank Sta=4975.5,5026.6
XS Rating Curve= 0
Exp/Cntr=.5,.3

Type RM Length L Ch R = 1 ,23416   ,108,108,142
BEGIN DESCRIPTION:
Upstream Section of Bridge/Culvert/Weir
END DESCRIPTION:
XS GIS Cut Line= 6
       3076381.6       13952376.      3076388.13     13951404.32
      3076647.96     13950671.04      3076700.64     13950256.61
      3076599.51     13950003.78      3075968.64     13949283.83
#Sta/Elev= 30
  3212.3  136.14  3492.3  134.92  3572.3  136.05  3932.3  133.93  3972.3  134.04
  4002.3  135.38    4384  134.16    4674  133.47    4734  131.36    4804  133.33
    4874  134.29    4904  133.24    4934  134.12  4975.5  133.02  5000.4  124.13
  5003.3   124.7  5017.9  132.64    5042  133.64  5179.3  134.18  5599.8  132.62
  5982.1  133.38  6012.1  132.35  6022.1  133.78  6042.1  134.57  6062.1  134.31
  6092.1  132.27  6132.1  134.05  6202.1   133.1  6442.1     134  6609.4  137.45
#Mann= 6 ,-1 , 0
  3212.3      .1       0    4384     .12       0    4934     .05       0
  4975.5     .04       0  5017.9     .08       0  6132.1     .12       0
#XS Ineff= 4 ,-1
  3212.3    4514     135 4839.13 4974.18  133.48 5025.82 5180.73  133.46
    5370  6609.4     135
Permanent Ineff=
       F       F       F       F
Bank Sta=4975.5,5017.9
XS Rating Curve= 0
Exp/Cntr=.5,.3

Type RM Length L Ch R = 3 ,23362   ,,,
BEGIN DESCRIPTION:
23383 RHODES RD
Structure ID: K124-00-00-S8
END DESCRIPTION:
Bridge Culvert--1,0,-1,-1, 0
Deck Dist Width WeirC Skew NumUp NumDn MinLoCord MaxHiCord MaxSubmerge Is_Ogee
33,42,2.6,0, 80, 80, , , .95, 0, ,,,
  3212.3  3288.4  3298.4  3308.4  3498.4  3518.4  3588.4  3598.4  3618.4  3848.4
  3858.4  4088.4  4108.4  4182.9  4266.5  4349.9  4409.9  4419.9  4429.9  4449.9
  4469.9  4529.9  4539.9  4549.9  4579.9  4589.9  4609.9  4629.9  4639.9  4689.9
  4709.9  4759.9  4759.9  4821.9  4872.5  4913.2  4946.9    4947  5034.2  5034.3
  5079.5  5129.6  5181.2  5218.8  5244.4  5254.4  5264.4  5364.4    5372    5402
    5442    5452    5462    5472    5482    5492  5497.3  5537.3  5547.3  5567.3
  5587.3  5617.3  5627.3  5637.3  5641.5  5651.5  5671.5  5681.5  5691.5  5701.5
  5731.5  5741.5  5791.5  5801.5  5838.6  5848.6  6028.6  6088.6  6098.6  6132.1
  136.14  136.88  136.51  136.43  136.66  136.13  136.04  136.25  136.04  135.24
  134.95  134.54  134.86  134.71  134.68  134.67  134.35  134.64  134.56  134.19
  133.02  133.27   133.6  134.28  134.17  133.44  134.24  133.77  134.07  134.17
  133.74  134.28  134.28   134.4  134.24  134.05  134.05  137.79     138  134.26
  134.26  134.37  134.11  133.88  133.61   133.6  133.84  133.42   133.6  133.89
  133.52  133.78  133.38  133.36  133.62  133.33  133.37  133.49  133.85  133.61
  133.81  133.55  133.87  133.65  133.79  133.86  133.54  133.89  133.46  133.72
  133.88  133.63  133.68  133.34  133.42  133.69  133.44   134.5  134.28  134.05
                                                                                
                                                                                
                                                                                
                           132.6  132.44  132.25  132.25  132.29   132.5  132.46
  132.46
                                                                                
                                                                                
                                                                                
  3110.7  3208.4  3288.4  3298.4  3308.4  3498.4  3518.4  3588.4  3598.4  3618.4
  3848.4  3858.4  4088.4  4108.4  4182.9  4266.5  4349.9  4409.9  4419.9  4429.9
  4449.9  4469.9  4529.9  4539.9  4549.9  4579.9  4589.9  4609.9  4629.9  4639.9
  4689.9  4709.9  4759.9  4759.9  4821.9  4872.5  4913.2  4946.9    4947  5034.2
  5034.3  5079.5  5129.6  5181.2  5218.8  5244.4  5254.4  5264.4  5364.4    5372
    5402    5442    5452    5462    5472    5482    5492  5497.3  5537.3  5547.3
  5567.3  5587.3  5617.3  5627.3  5637.3  5641.5  5651.5  5671.5  5681.5  5691.5
  5701.5  5731.5  5741.5  5791.5  5801.5  5838.6  5848.6  6028.6  6088.6  6120.6
  136.06  136.92  136.88  136.51  136.43  136.66  136.13  136.04  136.25  136.04
  135.24  134.95  134.54  134.86  134.71  134.68  134.67  134.35  134.64  134.56
  134.19  133.02  133.27   133.6  134.28  134.17  133.44  134.24  133.77  134.07
  134.17  133.74  134.28  134.28   134.4  134.24  134.05  134.05  137.79     138
  134.26  134.26  134.37  134.11  133.88  133.61   133.6  133.84  133.42   133.6
  133.89  133.52  133.78  133.38  133.36  133.62  133.33  133.37  133.49  133.85
  133.61  133.81  133.55  133.87  133.65  133.79  133.86  133.54  133.89  133.46
  133.72  133.88  133.63  133.68  133.34  133.42  133.69  133.44   134.5   134.3
                                                                                
                                                                                
                                                                                
                                   132.6  132.44  132.25  132.25  132.29   132.5
  132.46  132.46
                                                                                
                                                                                
                                                                                
Pier Skew, UpSta & Num, DnSta & Num=  ,4991.4, 2 ,4991.4, 2 , 0 , 0 , 0 ,,
     1.3     1.3
  125.81  133.39
     1.3     1.3
  125.12   132.7
BR Coef= 1 , 1 , 1 ,1.25, 0 ,,,.8,0,2,0,
WSPro=,,,, 1 ,,,, 0 ,,,, 0 ,,,,-1 ,-1 ,-1 , 0 , 0 , 0 , 0 , 0
BC Design=,, 0 ,, 0 ,,,,,,
BC HTab HWMax=137.77

Type RM Length L Ch R = 1 ,23308   ,170.1,114,69.1
BEGIN DESCRIPTION:
Downstream Section of Bridge/Culvert/Weir
END DESCRIPTION:
XS GIS Cut Line= 6
        3076515.       13952479.      3076550.53     13951335.92
       3076771.6     13950566.63      3076787.32     13950150.66
       3076659.7     13949905.06       3076048.1     13949206.77
#Sta/Elev= 30
  3110.7  136.06  3240.7  135.09  3720.7  135.78  4294.6   134.3  4534.6  134.93
  4774.6  133.35  4816.8  132.12  4846.8  133.46  4946.8  133.61  4975.5  133.02
  5000.4  124.13  5003.3   124.7  5017.9  132.64    5066  133.52    5116  131.48
    5196  132.88    5226  132.03  5603.9  131.77  5623.9  133.35  5653.9  131.65
  5980.6  134.49  6050.6  134.04  6060.6  133.68  6070.6  131.65  6090.6  133.62
  6130.6  133.99  6150.6  132.31  6190.6  134.18  6430.6  133.33  6678.9  136.45
#Mann= 6 ,-1 , 0
  3110.7      .1       0  4294.6     .12       0  4946.8     .05       0
  4975.5     .04       0  5017.9     .08       0  6130.6     .12       0
#XS Ineff= 4 ,-1
  3110.7  4504.6  134.92 4851.04 4974.18  133.26 5025.82 5093.35   133.3
  5314.3  6678.9   134.5
Permanent Ineff=
       F       F       F       F
Bank Sta=4975.5,5017.9
XS Rating Curve= 0
Exp/Cntr=.5,.3

Type RM Length L Ch R = 1 ,23194   ,170.3,196,157.8
BEGIN DESCRIPTION:
S8_RHODES RD-DS-XS 1
END DESCRIPTION:
XS GIS Cut Line= 5
       3076884.1       13952503.      3076904.76     13950596.67
      3076816.28     13950524.81      3076835.48     13950090.46
      3076069.77     13949194.73
#Sta/Elev= 30
  3007.4  136.09  3177.4  133.73  3477.4   133.8  3637.4  135.41  3747.4  133.91
  3987.4  134.46  4027.4  132.63  4157.4   134.8  4437.4  134.88  4467.4  136.56
  4517.4   136.6  4597.4  133.93  4847.4  132.81  4924.2  133.91  4978.1  129.64
  4988.1  127.85 5000.23  123.42  5018.1  128.96  5028.2     131  5068.2   133.7
    5553  132.72    5573  131.45    5603  133.47    5623  132.03    5653  132.92
    5993  134.44    6043  131.86    6083  134.21    6393  133.55  6641.4  136.23
#Mann= 6 ,-1 , 0
  3007.4     .99       0  4437.4     .12       0  4978.1     .04       0
  5018.1     .12       0    5653     .12       0    5993     .99       0
#XS Ineff= 2 , 0
       0 4517.43   136.6    5550       0     134
Permanent Ineff=
       F       F
Bank Sta=4978.1,5018.1
XS Rating Curve= 0
Exp/Cntr=.5,.3

Type RM Length L Ch R = 1 ,22998   ,51.8,43,43
BEGIN DESCRIPTION:
Upstream Section of Bridge/Culvert/Weir
END DESCRIPTION:
XS GIS Cut Line= 6
       3077100.9       13951294.      3076982.45     13950415.62
      3076941.88     13950367.92      3076872.96     13950284.34
      3076878.36     13950119.57       3076081.4     13949175.12
#Sta/Elev= 30
  4080.9  135.54  4110.9  134.35  4210.9  133.94  4410.9  134.52  4790.9   133.9
  4920.9  131.86  4967.7  132.65  4980.6  131.74  4996.7  122.56    5000  122.46
  5013.4  126.19  5023.4  131.56    5029  132.76  5060.6  133.24  5090.6  135.07
  5120.6   134.9    5149  133.28    5229  132.35  5413.8   132.9  5463.8  131.93
  5503.8  133.67  5523.8  132.32  5613.8  133.85  5903.8  134.28  5923.8  132.77
  5973.8  134.41  6013.8  133.36  6033.8  134.13  6233.8  133.47  6539.6   136.2
#Mann= 5 ,-1 , 0
  4080.9     .12       0  4967.7     .04       0    5029     .04       0
  5060.6     .12       0  5903.8     .12       0
#XS Ineff= 3 ,-1
    4800  4967.7   131.8 5047.88 5104.91  133.13 5110.86 6020.84  133.15
Permanent Ineff=
       F       F       T
Bank Sta=4967.7,5029
XS Rating Curve= 0
Exp/Cntr=.5,.3

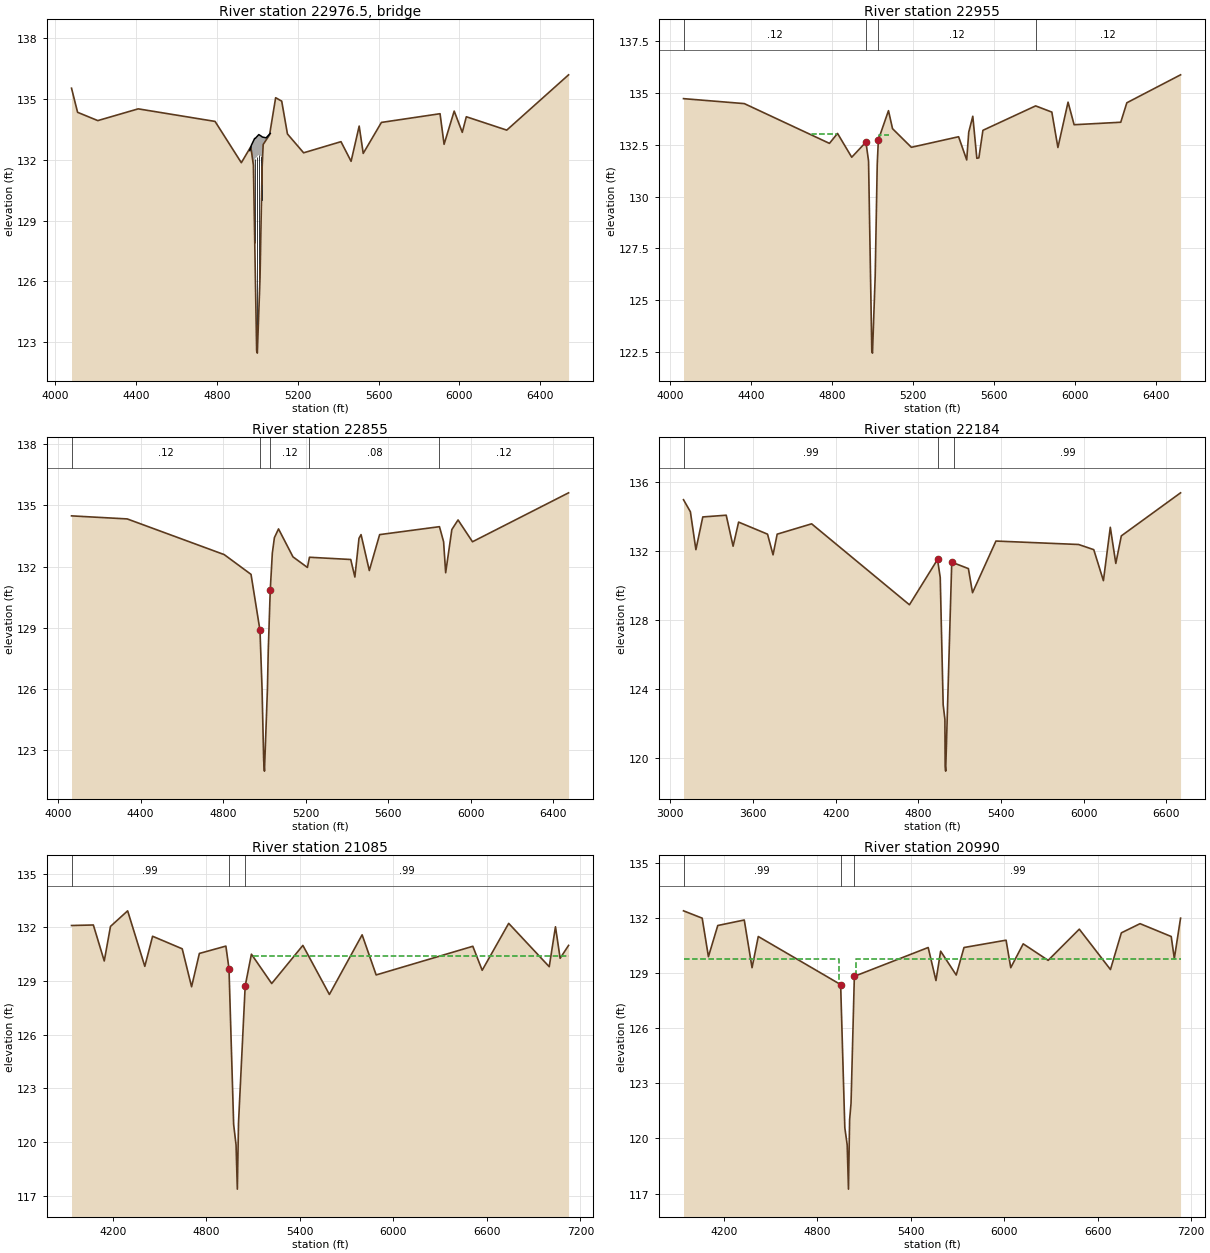
Type RM Length L Ch R = 3 ,22976.5 ,,,
BEGIN DESCRIPTION:
23002 WOOD BRIDGE 340' DS RHODES RD
Structure ID: K124-00-00-S9-1
END DESCRIPTION:
Bridge Culvert--1,0,-1,-1, 0
Deck Dist Width WeirC Skew NumUp NumDn MinLoCord MaxHiCord MaxSubmerge Is_Ogee
11.5,20,2,0, 11, 11, , , .95, 0, ,,,
  4962.9  4970.4  4986.7 4986.79  4989.6  5007.4  5021.1  5021.2  5024.6  5043.3
  5064.2
  132.46  132.72  133.06  133.06  133.06  133.25  133.16  133.16  133.13  133.09
  133.31
                          132.06  132.06  132.25  132.15
        
  4962.9  4970.4  4986.7 4986.79  4989.6  5007.4  5021.1  5021.2  5024.6  5043.3
  5064.2
  132.46  132.72  133.06  133.06  133.06  133.25  133.16  133.16  133.13  133.09
  133.31
                          132.06  132.06  132.25  132.15
        
Pier Skew, UpSta & Num, DnSta & Num=  ,4987.3, 2 ,4987.3, 2 , 0 , 0 , 0 ,,
       1       1
  126.59  133.03
       1       1
  126.63  133.07
Pier Skew, UpSta & Num, DnSta & Num=  ,4998.2, 2 ,4998.2, 2 , 0 , 0 , 0 ,,
       1       1
  121.48  133.16
       1       1
  121.52   133.2
Pier Skew, UpSta & Num, DnSta & Num=  ,5009, 2 ,5009, 2 , 0 , 0 , 0 ,,
       1       1
  123.75  133.24
       1       1
  123.79  133.28
Pier Skew, UpSta & Num, DnSta & Num=  ,5020.5, 2 ,5020.5, 2 , 0 , 0 , 0 ,,
       1       1
  128.71  133.16
       1       1
  128.75   133.2
BR Coef= 1 , 1 , 1 ,1.25, 0 ,,,.8,0,2,0,
WSPro=,,,, 1 ,,,, 0 ,,,, 0 ,,,,-1 ,-1 ,-1 , 0 , 0 , 0 , 0 , 0
BC Design=,, 0 ,, 0 ,,,,,,
BC HTab HWMax=136.92

Type RM Length L Ch R = 1 ,22955   ,99.8,100,99.9
BEGIN DESCRIPTION:
Downstream Section of Bridge/Culvert/Weir
END DESCRIPTION:
XS GIS Cut Line= 6
       3077136.7       13951275.      3077017.41     13950390.33
      3076973.14     13950338.28      3076894.95     13950243.46
       3076896.8     13950110.35      3076108.28     13949159.76
#Sta/Elev= 30
  4067.6  134.73  4367.6  134.49  4787.6  132.57  4827.6  133.05  4897.6   131.9
  4967.7  132.63  4980.6  131.72  4996.7  122.54    5000  122.44  5013.4  126.17
  5023.4  131.54    5029  132.74  5078.9  134.15  5098.9  133.28  5191.8  132.38
  5424.9  132.89  5464.9  131.77  5474.9  133.11  5494.9  133.88  5514.9  131.85
  5524.9  131.87  5544.9   133.2  5804.9  134.38  5884.9  134.08  5914.9  132.37
  5964.9  134.56  5994.9  133.47  6224.9  133.59  6254.9  134.53    6520  135.88
#Mann= 4 ,-1 , 0
  4067.6     .12       0  4967.7     .04       0    5029     .12       0
  5804.9     .12       0
#XS Ineff= 4 ,-1
    4700    4820     133    4820  4967.7   131.8 5032.99    5080  132.99
 5100.85 6020.84     133
Permanent Ineff=
       F       F       F       T
Bank Sta=4967.7,5029
XS Rating Curve= 0
Exp/Cntr=.5,.3

Type RM Length L Ch R = 1 ,22855   ,655.3,671,682.1
BEGIN DESCRIPTION:
S9-1_WOOD BRIDGE-DS-XS 1
END DESCRIPTION:
XS GIS Cut Line= 4
       3077211.1       13951208.      3077099.43     13950332.67
      3077047.57     13950271.94      3076142.85     13949144.39
#Sta/Elev= 30
  4064.8  134.49  4334.8  134.34  4804.8  132.59  4934.8  131.62  4978.2  128.87
 4988.12  126.02 4996.09   122.5 4999.79  121.97 5014.23     126 5018.28   127.9
    5028  130.87    5038  132.66    5048  133.42    5068  133.85    5138  132.48
    5208  131.96    5218  132.46    5418  132.35    5438  131.49    5458  133.39
    5468  133.57    5508  131.81    5558  133.57    5848  133.96    5868  133.22
    5878   131.7    5908  133.82    5938  134.29    6008  133.22  6473.7  135.62
#Mann= 5 ,-1 , 0
  4064.8     .12       0  4978.2     .04       0    5028     .12       0
    5218     .08       0    5848     .12       0
#XS Ineff= 2 , 0
       0                    5068       0  133.85
Permanent Ineff=
       F       F
Bank Sta=4978.2,5028
XS Rating Curve= 0
Exp/Cntr=.3,.1

Type RM Length L Ch R = 1 ,22184   ,1099.8,1099,1091.4
BEGIN DESCRIPTION:
Cross Section K124-00-00-X11
END DESCRIPTION:
XS GIS Cut Line= 4
        3077493.      13951863.7      3077668.55      13950015.6
      3077636.63     13949929.92      3076353.72      13948876.4
#Sta/Elev= 30
  3095.7     135  3145.7   134.3  3185.7   132.1  3235.7     134  3405.7   134.1
  3455.7   132.3  3495.7   133.7  3705.7     133  3745.7   131.8  3775.7     133
  4025.7   133.6  4735.7   128.9  4939.6  131.53  4959.2  130.48  4980.5  123.09
  4993.1  122.25  4994.9  119.55  4998.6  119.24  5042.7  131.36  5060.1  131.32
  5163.6     131  5193.6   129.6  5363.6   132.6  5963.6   132.4  6073.6   132.1
  6143.6   130.3  6193.6   133.4  6233.6   131.3  6273.6   132.9  6703.6   135.4
#Mann= 3 ,-1 , 0
  3095.7     .99       0  4939.6     .04       0  5060.1     .99       0
#XS Ineff= 2 , 0
       0    4930   131.3    5055       0   131.3
Permanent Ineff=
       F       F
Bank Sta=4939.6,5042.7
XS Rating Curve= 0
Exp/Cntr=.3,.1

Type RM Length L Ch R = 1 ,21085   ,87.6,95,105
BEGIN DESCRIPTION:
S9_BRIDGEVIEW-US-XS 4
END DESCRIPTION:
XS GIS Cut Line= 4
      3078567.34      13950651.5      3078695.36      13949639.8
      3078670.41     13949559.66      3077010.14      13948299.8
#Sta/Elev= 30
  3935.9   132.1  4075.9  132.13  4145.9  130.12  4185.9  132.05  4295.9  132.92
  4405.9  129.82  4455.9   131.5  4645.9   130.8  4705.9  128.68  4755.9  130.54
  4925.9  130.95  4945.9  129.69 4975.76  120.99 4991.14  119.85 4999.44  117.38
 5006.92  121.08  5049.7  128.72  5089.7   130.5  5219.7  128.86  5419.7  130.99
  5589.7  128.25  5799.7  131.58  5889.7  129.34  6509.7  130.94  6569.7   129.6
  6739.7  132.22  6999.7   129.8  7039.7  132.03  7069.7  130.27  7123.8  130.99
#Mann= 3 , 0 , 0
  3935.9     .99       0  4945.9     .04       0  5049.7     .99       0
#XS Ineff= 2 , 0
       0    4923   130.8    5100       0   130.4
Permanent Ineff=
       F       F
Bank Sta=4945.9,5049.7
XS Rating Curve= 0
Exp/Cntr=.5,.3

Type RM Length L Ch R = 1 ,20990   ,58.9,59,60.8
BEGIN DESCRIPTION:
Upstream Section of Bridge/Culvert/Weir
END DESCRIPTION:
XS GIS Cut Line= 4
      3078659.56      13950620.8      3078782.23     13949647.08
      3078770.17     13949528.49      3077102.36       13948269.
#Sta/Elev= 30
  3940.6  132.41  4060.6  132.01  4100.6  129.91  4160.6  131.61  4330.6  131.91
  4380.6  129.31  4420.6  131.01  4949.3  128.39  4976.1  120.59  4991.3  119.65
  4999.5  117.24  5006.9  121.02    5016  121.92  5037.3  128.84  5511.2  130.41
  5561.2  128.61  5591.2  130.21  5691.2  128.91  5741.2  130.41  6011.2  130.81
  6041.2  129.31  6121.2  130.61  6281.2  129.71  6481.2  131.41  6681.2  129.21
  6751.2  131.21  6871.2  131.71  7071.2  131.01  7091.2  129.81  7131.2  132.01
#Mann= 3 ,-1 , 0
  3940.6     .99       0  4949.3     .04       0  5037.3     .99       0
#XS Ineff= 2 , 0
       0  4939.3   129.8  5047.3       0   129.8
Permanent Ineff=
       F       F
Bank Sta=4949.3,5037.3
XS Rating Curve= 0
Exp/Cntr=.5,.3