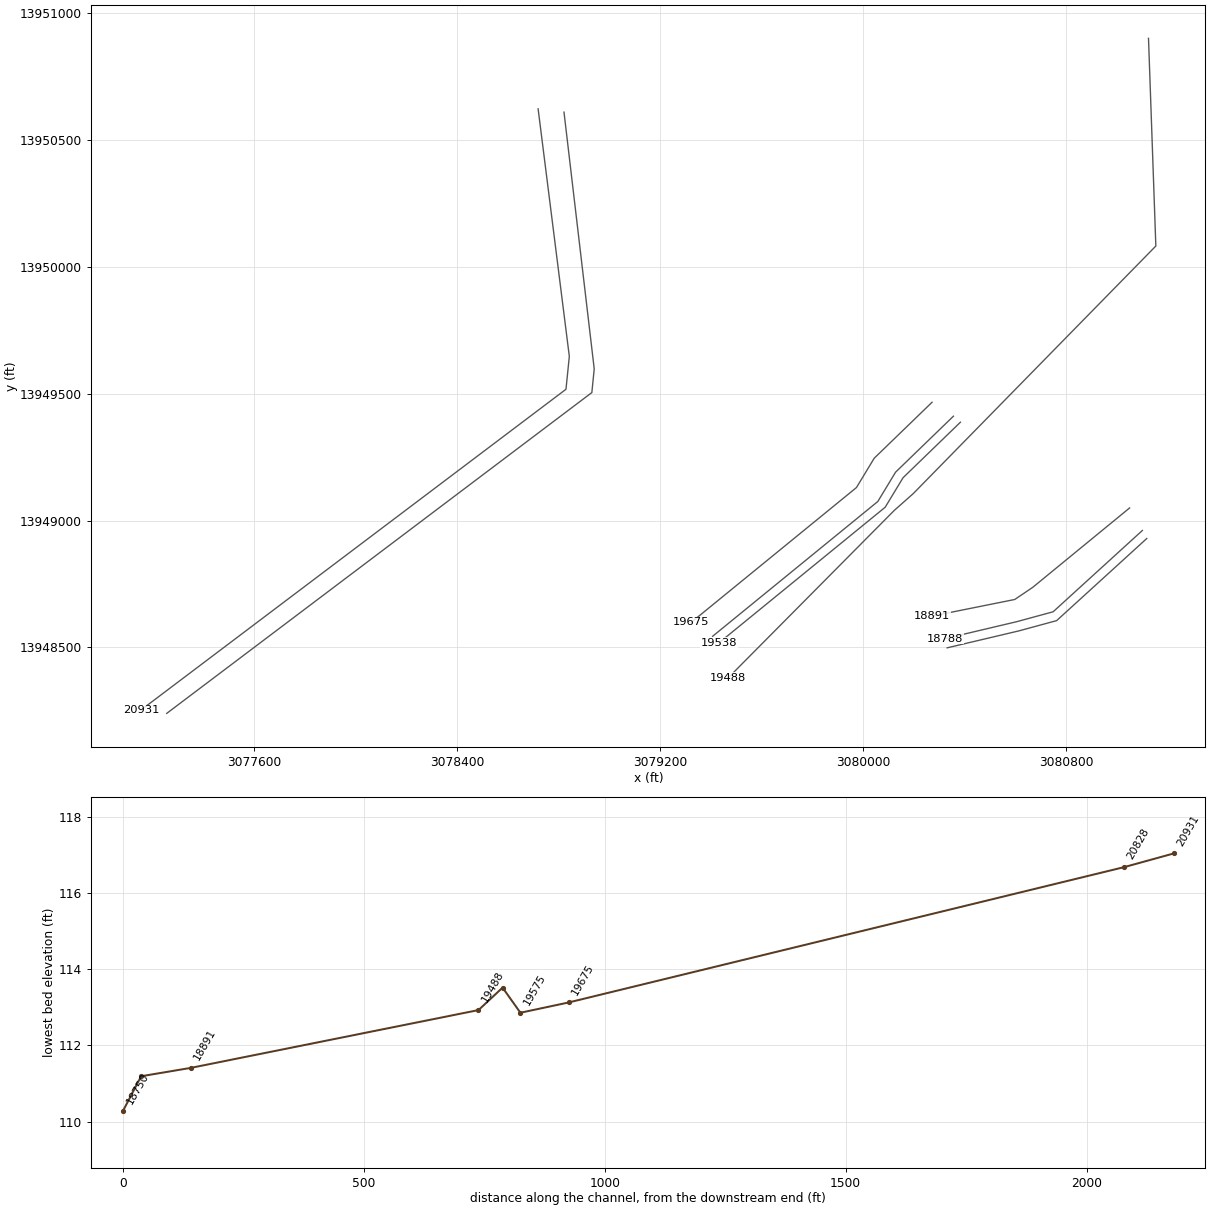
HEC-RAS study K124-00-00.prj: K124-00-00

--- K124-00-00.g05 (geometry) --- (continued)

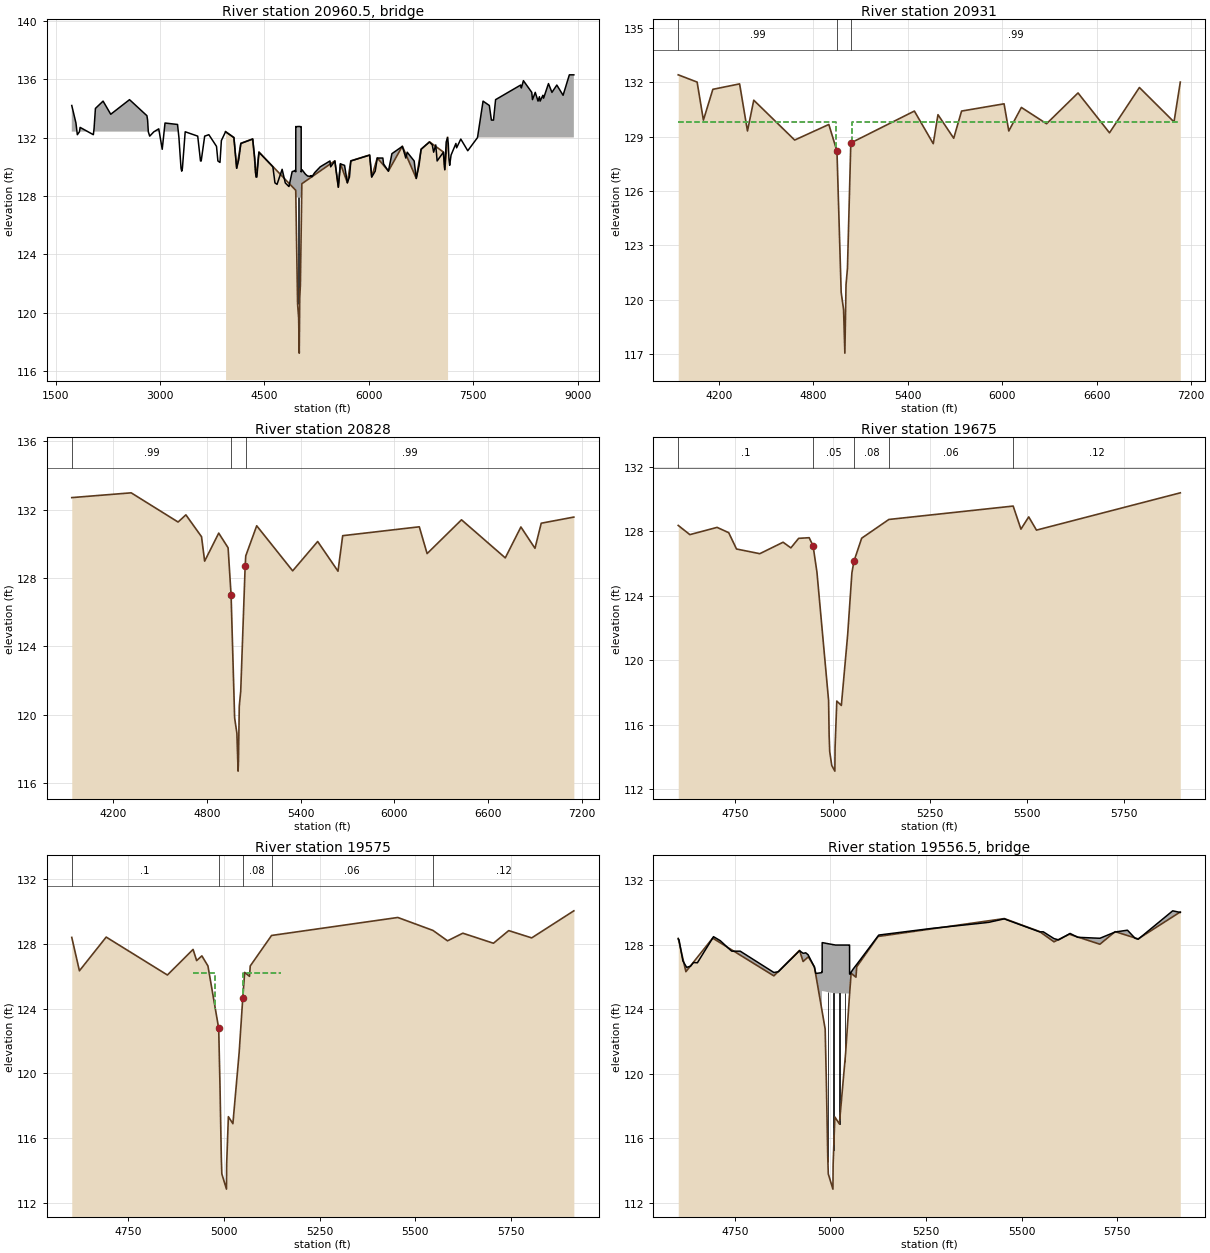
Type RM Length L Ch R = 3 ,20960.5 ,,,
BEGIN DESCRIPTION:
20993 BRIDGEVIEW DRIVE
Structure ID: K124-00-00-S9
END DESCRIPTION:
Bridge Culvert--1,0,-1,-1, 0
Deck Dist Width WeirC Skew NumUp NumDn MinLoCord MaxHiCord MaxSubmerge Is_Ogee
10,36,2.6,0, 168, 168, , , .95, 0, ,,,
  1730.6  1790.6  1810.6  1840.6  1850.6  2040.6  2050.6  2070.6  2180.6  2290.6
  2560.6  2810.6  2820.6  2830.6  2850.6  2910.6  2980.6  3020.5  3030.6  3070.6
  3250.6  3270.6  3300.6  3310.6  3320.6  3360.6  3540.6  3580.6  3590.6  3640.6
  3700.6  3810.6  3830.6  3860.6  3880.6  3940.6  4060.6  4100.6  4130.6  4160.6
  4330.6  4360.6  4370.6  4380.6  4390.6  4420.6  4620.6  4650.6  4680.6  4753.6
  4799.5  4801.8  4851.5  4852.2  4894.6  4897.6  4935.8  4938.1  4949.3 4949.57
 4949.68 4949.79 4949.91    4950  4950.4  4950.9    4951  4965.3  4976.1  4979.3
  4990.9  4991.3  4996.1    4998  4998.3  4999.5  5001.6  5001.8  5001.9  5003.4
  5006.9    5016  5023.7  5026.9  5027.4 5027.49  5027.6 5027.71  5027.8 5034.37
 5034.51  5034.6  5037.3  5039.9  5087.3    5088  5119.2  5134.6  5150.7  5170.7
  5172.4  5182.9  5221.2  5301.2  5441.2  5451.2  5511.2  5561.2  5591.2  5651.2
  5691.2  5721.2  5741.2  6011.2  6041.2  6091.2  6121.2  6201.2  6211.2  6281.2
  6331.2  6481.2  6531.2  6551.2  6651.2  6681.2  6721.2  6751.2  6871.2  6911.2
  6931.2  6961.2  6981.2  7071.2  7091.2  7111.2  7131.2  7141.2  7151.2  7161.2
  7181.2  7251.2  7261.2  7321.2  7421.2  7561.2  7641.2  7731.2  7761.2  7791.2
  7821.2  8181.2  8191.2  8221.2  8341.2  8351.2  8391.2  8431.2  8451.2  8461.2
  8501.2  8511.2  8581.2  8631.2  8701.2  8791.2  8881.2  8945.9
   134.2     133   132.2   132.4   132.7   132.2   132.6     134   134.5   133.6
   134.6   133.5   133.2   132.4   132.1   132.4   132.6  131.48   131.2     133
   132.9     132   129.9   129.7   129.9   132.4   132.1   130.4   130.4   132.1
   132.2   131.4   130.4   130.3   131.8   132.4     132   129.9   130.5   131.6
   131.9   130.6   129.6   129.3   129.3     131     130   128.9   128.8  129.83
  128.89  128.88  128.65  128.66  129.59  129.67  129.73  129.76  129.66  129.66
  132.76  132.76  132.76  132.76  132.75  132.75  132.75  132.75  132.76  132.76
  132.76  132.76  132.76  132.76  132.76  132.76  132.76  132.76  132.76  132.76
  132.76  132.75  132.75  132.75  132.75  132.75  132.75  129.65  129.66  129.74
  129.74  129.74  129.77   129.8   129.5   129.5  129.37  129.36  129.35   129.4
  129.34  129.32   129.6     130   130.4     130   130.4   128.6   130.2   130.1
   128.9   129.3   130.4   130.8   129.3   129.7   130.6   130.6   130.2   129.7
   130.9   131.4   130.6     131   130.4   129.2   130.1   131.2   131.7   131.5
     131   131.5   130.4     131   129.8   131.7     132   131.6   130.5   130.1
   130.8   131.6   131.3   131.9   131.1     132   134.5   134.2   133.2   133.2
   134.6   135.6   135.4   135.9   135.1   134.6   135.1   134.5   134.8   134.5
   134.9   134.7   135.7   135.1   135.6   134.9   136.3   136.3
                                                                                
                                                                                
                                                                                
                                                                                
                                                                                
                                                                                
                                                  127.89  127.89   127.9   127.9
   127.9   127.9   127.9   127.9   127.9   127.9   127.9   127.9   127.9   127.9
   127.9  127.89  127.89  127.89  127.89  127.89  127.89  127.89   127.9  127.98
  127.98
                                                                                
                                                                                
                                                                                
                                                                                
                                                                                
                                                                                
                                                                
  1730.6  1790.6  1810.6  1840.6  1850.6  2040.6  2050.6  2070.6  2180.6  2290.6
  2560.6  2810.6  2820.6  2830.6  2850.6  2910.6  2980.6  3020.5  3030.6  3070.6
  3250.6  3270.6  3300.6  3310.6  3320.6  3360.6  3540.6  3580.6  3590.6  3640.6
  3700.6  3810.6  3830.6  3860.6  3880.6  3940.6  4060.6  4100.6  4130.6  4160.6
  4330.6  4360.6  4370.6  4380.6  4390.6  4420.6  4620.6  4650.6  4680.6  4753.6
  4799.5  4801.8  4851.5  4852.2  4894.6  4897.6  4935.8  4938.1  4949.3 4949.57
 4949.68 4949.79 4949.91    4950  4950.4  4950.9    4951  4965.3  4976.1  4979.3
  4990.9  4991.3  4996.1    4998  4998.3  4999.5  5001.6  5001.8  5001.9  5003.4
  5006.9    5016  5023.7  5026.9  5027.4 5027.49  5027.6 5027.71  5027.8 5034.37
 5034.51  5034.6  5037.3  5039.9  5087.3    5088  5119.2  5134.6  5150.7  5170.7
  5172.4  5182.9  5221.2  5301.2  5441.2  5451.2  5511.2  5561.2  5591.2  5651.2
  5691.2  5721.2  5741.2  6011.2  6041.2  6091.2  6121.2  6201.2  6211.2  6281.2
  6331.2  6481.2  6531.2  6551.2  6651.2  6681.2  6721.2  6751.2  6871.2  6911.2
  6931.2  6961.2  6981.2  7071.2  7091.2  7111.2  7131.2  7141.2  7151.2  7161.2
  7181.2  7251.2  7261.2  7321.2  7421.2  7561.2  7641.2  7731.2  7761.2  7791.2
  7821.2  8181.2  8191.2  8221.2  8341.2  8351.2  8391.2  8431.2  8451.2  8461.2
  8501.2  8511.2  8581.2  8631.2  8701.2  8791.2  8881.2  8945.9
   134.2     133   132.2   132.4   132.7   132.2   132.6     134   134.5   133.6
   134.6   133.5   133.2   132.4   132.1   132.4   132.6  131.48   131.2     133
   132.9     132   129.9   129.7   129.9   132.4   132.1   130.4   130.4   132.1
   132.2   131.4   130.4   130.3   131.8   132.4     132   129.9   130.5   131.6
   131.9   130.6   129.6   129.3   129.3     131     130   128.9   128.8  129.83
  128.89  128.88  128.65  128.66  129.59  129.67  129.73  129.76  129.66  129.66
  132.76  132.76  132.76  132.76  132.75  132.75  132.75  132.75  132.76  132.76
  132.76  132.76  132.76  132.76  132.76  132.76  132.76  132.76  132.76  132.76
  132.76  132.75  132.75  132.75  132.75  132.75  132.75  129.65  129.66  129.74
  129.74  129.74  129.77   129.8   129.5   129.5  129.37  129.36  129.35   129.4
  129.34  129.32   129.6     130   130.4     130   130.4   128.6   130.2   130.1
   128.9   129.3   130.4   130.8   129.3   129.7   130.6   130.6   130.2   129.7
   130.9   131.4   130.6     131   130.4   129.2   130.1   131.2   131.7   131.5
     131   131.5   130.4     131   129.8   131.7     132   131.6   130.5   130.1
   130.8   131.6   131.3   131.9   131.1     132   134.5   134.2   133.2   133.2
   134.6   135.6   135.4   135.9   135.1   134.6   135.1   134.5   134.8   134.5
   134.9   134.7   135.7   135.1   135.6   134.9   136.3   136.3
                                                                                
                                                                                
                                                                                
                                                                                
                                                                                
                                                                                
                                                  127.89  127.89   127.9   127.9
   127.9   127.9   127.9   127.9   127.9   127.9   127.9   127.9   127.9   127.9
   127.9  127.89  127.89  127.89  127.89  127.89  127.89  127.89   127.9  127.98
  127.98
                                                                                
                                                                                
                                                                                
                                                                                
                                                                                
                                                                                
                                                                
Pier Skew, UpSta & Num, DnSta & Num=  ,4976.1, 2 ,4976.1, 2 , 0 , 0 , 0 ,,
     1.4     1.4
  119.42   128.9
     1.4     1.4
  119.28  128.76
Pier Skew, UpSta & Num, DnSta & Num=  ,5001.8, 2 ,5001.8, 2 , 0 , 0 , 0 ,,
     1.4     1.4
  116.53   128.9
     1.4     1.4
  116.39  128.76
Abutment Skew #Up #Dn= , 2 , 2
  4949.8    4951
  128.15  127.83
  4949.8    4951
  128.01  127.69
BR Coef= 1 , 1 , 1 ,1.25, 0 ,,,.8,0,2,0,
WSPro=,,,, 1 ,,,, 0 ,,,, 0 ,,,,-1 ,-1 ,-1 , 0 , 0 , 0 , 0 , 0
BC Design=,, 0 ,, 0 ,,,,,,
BC HTab HWMax=132.41

Type RM Length L Ch R = 1 ,20931   ,102.5,103,106.9
BEGIN DESCRIPTION:
Downstream Section of Bridge/Culvert/Weir
END DESCRIPTION:
XS GIS Cut Line= 4
      3078718.55      13950623.3       3078841.5     13949647.32
      3078828.33     13949517.79      3077153.55       13948253.
#Sta/Elev= 30
  3940.6  132.41  4060.6  132.01  4100.6  129.91  4160.6  131.61  4330.6  131.91
  4380.6  129.31  4420.6  131.01  4680.6  128.81  4897.6  129.67  4949.3   128.2
  4976.1   120.4  4991.3  119.46  4999.5  117.05  5006.9  120.83    5016  121.73
  5037.3  128.65  5441.2  130.41  5561.2  128.61  5591.2  130.21  5691.2  128.91
  5741.2  130.41  6011.2  130.81  6041.2  129.31  6121.2  130.61  6281.2  129.71
  6481.2  131.41  6681.2  129.21  6871.2  131.71  7091.2  129.81  7131.2  132.01
#Mann= 3 ,-1 , 0
  3940.6     .99       0  4949.3     .04       0  5037.3     .99       0
#XS Ineff= 2 , 0
       0 4942.63   129.8 5043.97       0   129.8
Permanent Ineff=
       F       F
Bank Sta=4949.3,5037.3
XS Rating Curve= 0
Exp/Cntr=.5,.3

Type RM Length L Ch R = 1 ,20828   ,1171.8,1153,1132.9
BEGIN DESCRIPTION:
S9_BRIDGEVIEW-DS-XS 1
END DESCRIPTION:
XS GIS Cut Line= 4
      3078820.49      13950610.3      3078939.57     13949598.22
      3078930.27     13949504.84      3077255.49     13948240.15
#Sta/Elev= 30
  3936.1  132.71  4316.1  132.99  4616.1  131.28  4666.1   131.7  4766.1  130.42
  4786.1  128.99  4876.1  130.63  4936.1  129.77  4955.2     127 4977.88  119.81
 4992.31  118.91 5000.09  116.69 5002.42  117.29 5007.57   120.5 5016.77  121.36
  5045.2  128.68  5049.1   129.3  5119.1  131.06  5349.1  128.42  5509.1  130.14
  5639.1   128.4  5669.1  130.48  6159.1     131  6209.1  129.43  6429.1  131.41
  6709.1  129.18  6809.1  130.99  6899.1  129.74  6939.1  131.21  7147.7  131.57
#Mann= 3 ,-1 , 0
  3936.1     .99       0  4955.2     .04       0  5049.1     .99       0
#XS Ineff= 2 , 0
       0    4879   130.5    5122       0   130.8
Permanent Ineff=
       F       F
Bank Sta=4955.2,5045.2
XS Rating Curve= 0
Exp/Cntr=.3,.1

Type RM Length L Ch R = 1 ,19675   ,99.7,100,101.7
BEGIN DESCRIPTION:
WALK BRIDGE_S6-3_US-XS 4
END DESCRIPTION:
XS GIS Cut Line= 4
      3080270.49      13949466.6      3080042.68     13949246.03
      3079972.68     13949130.39      3079321.77     13948598.99
#Sta/Elev= 30
  4602.8  128.35  4632.8  127.78  4702.8  128.23  4732.8   127.9  4752.8  126.89
  4812.8   126.6  4872.8  127.31  4892.8  126.96  4912.8  127.55  4939.9  127.59
  4949.9  127.09  4959.9  125.46  4989.9   117.5 4991.27  115.37 4992.81  114.34
 4998.06  113.48 5006.05  113.13 5006.55  114.58 5011.01  117.47 5022.73   117.2
 5039.01  121.58  5049.9  125.41  5055.1  126.13  5075.1  127.56  5145.1  128.72
  5465.1  129.55  5485.1  128.12  5505.1  128.88  5525.1  128.06  5895.4  130.37
#Mann= 5 ,-1 , 0
  4602.8      .1       0  4949.9     .05       0  5055.1     .08       0
  5145.1     .06       0  5465.1     .12       0
#XS Ineff= 2 , 0
       0  4912.8  127.55               0
Permanent Ineff=
       F       F
Bank Sta=4949.9,5055.1
XS Rating Curve= 0
Exp/Cntr=.5,.3

Type RM Length L Ch R = 1 ,19575   ,36.6,37,36.5
BEGIN DESCRIPTION:
Upstream Section of Bridge/Culvert/Weir
END DESCRIPTION:
XS GIS Cut Line= 4
      3080354.63     13949411.64      3080126.82     13949191.02
      3080056.82     13949075.37      3079405.91     13948543.98
#Sta/Elev= 30
  4602.1  128.39  4622.1  126.33  4692.1  128.41  4852.1  126.07  4919.2  127.65
  4928.5  126.96  4942.2  127.25  4958.1  126.63  4986.2  122.78  4989.6  119.21
    4993  114.84  4994.4   113.8  5006.5  112.86    5007   114.4  5011.5  117.33
  5023.3   116.9  5039.7  121.29  5049.1  124.64  5054.1  126.23  5066.7  125.99
  5068.7  126.63  5124.4  128.51  5454.4  129.62  5546.4  128.82  5584.4  128.18
  5624.4  128.65  5704.4  128.03  5744.4  128.81  5804.4  128.36  5914.6  130.03
#Mann= 5 ,-1 , 0
  4602.1      .1       0  4986.2     .05       0  5049.1     .08       0
  5124.4     .06       0  5546.4     .12       0
#XS Ineff= 3 ,-1
  4602.1  4919.2  127.65  4919.2  4977.7  126.22  5049.9    5150  126.18
Permanent Ineff=
       F       F       F
Bank Sta=4986.2,5049.1
XS Rating Curve= 0
Exp/Cntr=.5,.3

Type RM Length L Ch R = 3 ,19556.5 ,,,
BEGIN DESCRIPTION:
19578 1300 FEET US FROM SPRING CYPRESS
Structure ID: K124-00-00-S6-3
END DESCRIPTION:
Bridge Culvert--1,0,-1,-1, 0
Deck Dist Width WeirC Skew NumUp NumDn MinLoCord MaxHiCord MaxSubmerge Is_Ogee
10,19,2.6,0, 89, 89, , , .95, 0, ,,,
  4602.1  4604.2  4612.1  4614.2  4622.1  4624.2  4634.2  4642.1  4652.1  4692.1
  4694.2  4712.1  4734.2  4742.1  4764.2  4852.1  4864.2  4894.2  4914.2  4915.4
  4919.2  4928.5  4931.3  4935.4  4941.9  4942.2  4958.1  4961.7  4977.4  4977.5
 4977.61 4977.68 4978.29  4978.4 4978.51  4986.2  4989.6  4992.9    4993  4993.4
  4994.4  4999.2  5006.5    5007  5007.1  5008.4  5011.5  5012.8  5015.7  5023.3
  5026.3  5037.7  5039.7  5049.1 5049.89    5050 5050.11    5053 5053.09  5053.2
  5053.3  5054.1  5058.7  5059.3  5066.7  5068.7  5124.4  5126.4  5264.4  5396.4
  5414.4  5446.4  5454.4  5546.4  5556.4  5564.4  5568.3  5584.4  5596.4  5624.4
  5626.4  5646.4  5704.4  5744.4  5776.4  5796.4  5804.4  5894.7  5914.6
  128.36   128.3  127.27     127  126.68   126.6  126.67   126.9  126.88  128.41
   128.5  128.25  127.76   127.6   127.6  126.28  126.33  127.04  127.51  127.54
  127.63  127.47  127.48   127.5  127.37  127.35  126.61  126.22  126.27  126.33
  126.33  126.33  126.33  128.13  128.13   128.1  128.08  128.07  128.07  128.06
  128.06  128.04  128.01  128.01     128     128  127.99  127.98  127.98  127.98
  127.98  127.98  127.98  127.98  127.98  127.98  126.18  126.19  126.23  126.27
  126.27   126.3  126.47  126.49  126.72  126.78  128.54   128.6  129.01  129.34
  129.39  129.56   129.6   128.8   128.8  128.68  128.62  128.38   128.3  128.67
   128.7  128.46   128.4  128.79   128.9   128.4  128.34   130.1     130
                                                                                
                                                                                
                                                                                
          125.13  125.13  125.13  125.13   125.1  125.08  125.07  125.07  125.06
  125.06  125.04  125.01  125.01     125     125  124.99  124.98  124.98  124.98
  124.98  124.98  124.98  124.98  124.98  124.98
                                                                                
                                                                                
                                                                        
  4602.1  4604.2  4612.1  4614.2  4622.1  4624.2  4634.2  4642.1  4652.1  4692.1
  4694.2  4712.1  4734.2  4742.1  4764.2  4852.1  4864.2  4894.2  4914.2  4915.4
  4919.2  4928.5  4931.3  4935.4  4941.9  4942.2  4958.1  4961.7  4977.4  4977.5
 4977.61 4977.68 4978.29  4978.4 4978.51  4986.2  4989.6  4992.9    4993  4993.4
  4994.4  4999.2  5006.5    5007  5007.1  5008.4  5011.5  5012.8  5015.7  5023.3
  5026.3  5037.7  5039.7  5049.1 5049.89    5050 5050.11    5053 5053.09  5053.2
  5053.3  5054.1  5058.7  5059.3  5066.7  5068.7  5124.4  5126.4  5264.4  5396.4
  5414.4  5446.4  5454.4  5546.4  5556.4  5564.4  5568.3  5584.4  5596.4  5624.4
  5626.4  5646.4  5704.4  5744.4  5776.4  5796.4  5804.4  5894.7  5914.6
  128.36   128.3  127.27     127  126.68   126.6  126.67   126.9  126.88  128.41
   128.5  128.25  127.76   127.6   127.6  126.28  126.33  127.04  127.51  127.54
  127.63  127.47  127.48   127.5  127.37  127.35  126.61  126.22  126.27  126.33
  126.33  126.33  126.33  128.13  128.13   128.1  128.08  128.07  128.07  128.06
  128.06  128.04  128.01  128.01     128     128  127.99  127.98  127.98  127.98
  127.98  127.98  127.98  127.98  127.98  127.98  126.18  126.19  126.23  126.27
  126.27   126.3  126.47  126.49  126.72  126.78  128.54   128.6  129.01  129.34
  129.39  129.56   129.6   128.8   128.8  128.68  128.62  128.38   128.3  128.67
   128.7  128.46   128.4  128.79   128.9   128.4  128.34   130.1     130
                                                                                
                                                                                
                                                                                
          125.13  125.13  125.13  125.13   125.1  125.08  125.07  125.07  125.06
  125.06  125.04  125.01  125.01     125     125  124.99  124.98  124.98  124.98
  124.98  124.98  124.98  124.98  124.98  124.98
                                                                                
                                                                                
                                                                        
Pier Skew, UpSta & Num, DnSta & Num=  ,4993.4, 2 ,4993.4, 2 , 0 , 0 , 0 ,,
       1       1
  113.32  126.07
       1       1
  114.15   126.9
Pier Skew, UpSta & Num, DnSta & Num=  ,5008.4, 2 ,5008.4, 2 , 0 , 0 , 0 ,,
       1       1
  114.02     126
       1       1
  114.85  126.83
Pier Skew, UpSta & Num, DnSta & Num=  ,5023.3, 2 ,5023.3, 2 , 0 , 0 , 0 ,,
       1       1
  115.87  125.98
       1       1
   116.7  126.81
Pier Skew, UpSta & Num, DnSta & Num=  ,5037.7, 2 ,5037.7, 2 , 0 , 0 , 0 ,,
       1       1
  119.59  125.98
       1       1
  120.42  126.81
BR Coef= 1 , 1 , 1 ,1.25, 0 ,,,.8,0,2,0,
WSPro=,,,, 1 ,,,, 0 ,,,, 0 ,,,,-1 ,-1 ,-1 , 0 , 0 , 0 , 0 , 0
BC Design=,, 0 ,, 0 ,,,,,,
BC HTab HWMax=130.12

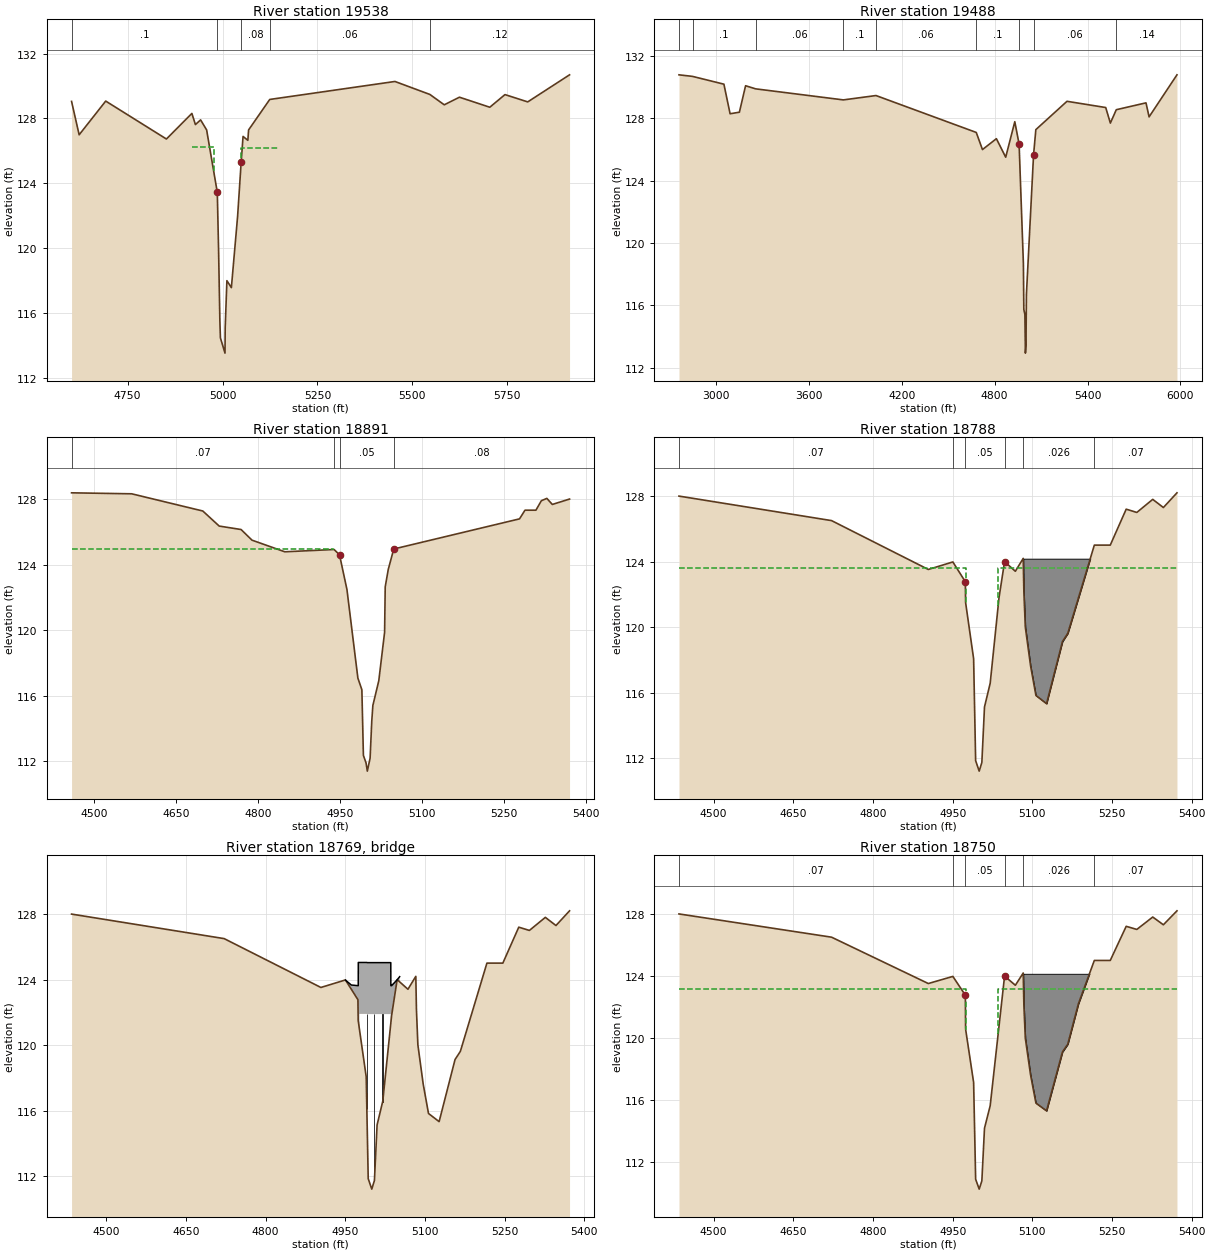
Type RM Length L Ch R = 1 ,19538   ,63.3,50,36.5
BEGIN DESCRIPTION:
Downstream Section of Bridge/Culvert/Weir
END DESCRIPTION:
XS GIS Cut Line= 4
      3080382.26     13949387.98      3080156.31     13949169.16
      3080085.86     13949052.77      3079432.28     13948519.19
#Sta/Elev= 30
  4602.1  129.05  4622.1  126.99  4692.1  129.07  4852.1  126.73  4919.2  128.31
  4928.5  127.62  4942.2  127.91  4958.1  127.29  4986.2  123.44  4989.6  119.87
    4993   115.5  4994.4  114.46  5006.5  113.52    5007  115.06  5011.5  117.99
  5023.3  117.56  5039.7  121.95  5049.1   125.3  5054.1  126.89  5066.7  126.65
  5068.7  127.29  5124.4  129.17  5454.4  130.28  5546.4  129.48  5584.4  128.84
  5624.4  129.31  5704.4  128.69  5744.4  129.47  5804.4  129.02  5914.6  130.69
#Mann= 5 ,-1 , 0
  4602.1      .1       0  4986.2     .05       0  5049.1     .08       0
  5124.4     .06       0  5546.4     .12       0
#XS Ineff= 3 ,-1
  4602.1  4919.2  128.31  4919.2  4977.7  126.22  5049.9    5150  126.18
Permanent Ineff=
       F       F       F
Bank Sta=4986.2,5049.1
XS Rating Curve= 0
Exp/Cntr=.5,.3

Type RM Length L Ch R = 1 ,19488   ,607.9,597,578.2
BEGIN DESCRIPTION:
Cross Section K124-00-00-X10
END DESCRIPTION:
XS GIS Cut Line= 5
      3081123.21      13950901.2      3081152.13      13950082.5
      3080196.29      13949106.4      3080121.68     13949040.27
      3079466.95      13948379.8
#Sta/Elev= 30
  2762.5   130.8  2849.8   130.7  3052.5   130.2  3092.5   128.3  3152.5   128.4
  3192.5   130.1    3257   129.9  3823.9  129.19  4034.4  129.47  4681.8   127.1
  4721.8     126  4811.8   126.7  4871.9  125.51  4930.6  127.79  4958.4  126.35
  4986.1  118.67  4988.9  115.74  4995.7  115.41  4999.1  112.93  5002.9  113.43
  5005.6  116.69  5051.6  125.64  5066.4  127.28  5267.6   129.1  5517.6   128.7
  5547.6   127.7  5585.8  128.56  5777.6     129  5797.6   128.1  5977.6   130.8
#Mann= 9 ,-1 , 0
  2762.5     .06       0  2849.8      .1       0    3257     .06       0
  3823.9      .1       0  4034.4     .06       0  4681.8      .1       0
  4958.4     .05       0  5051.6     .06       0  5585.8     .14       0
#XS Ineff= 2 , 0
       0    4933   126.6               0
Permanent Ineff=
       F       F
#Block Obstruct= 1 ,-1
 2065.04 2731.71     129
Bank Sta=4958.4,5051.6
XS Rating Curve= 0
Exp/Cntr=.3,.1

Type RM Length L Ch R = 1 ,18891   ,125.4,103,89.7
BEGIN DESCRIPTION:
WOOD BRIDGE_S6-2_US-XS 4
END DESCRIPTION:
XS GIS Cut Line= 4
      3081048.81       13949050.      3080667.21     13948737.05
      3080596.28     13948689.12      3080271.22     13948623.77
#Sta/Elev= 30
    4459   128.4    4569  128.34    4699  127.29    4729  126.37    4769  126.16
    4789  125.51    4849   124.8    4939  124.94    4949  124.62  4962.6   122.5
  4982.6  117.09 4989.91  116.38  4992.7  112.37 4997.55  111.91 4999.88  111.41
 5004.95   112.2 5007.99  114.46 5010.01  115.42 5020.85  116.93 5031.48  119.89
  5032.6  122.66  5038.2  123.73  5048.2  124.97  5278.2  126.81  5288.2  127.34
  5308.2  127.34  5318.2  127.92  5328.2  128.06  5338.2  127.69  5369.7  128.02
#Mann= 4 ,-1 , 0
    4459     .07       0    4939     .08       0    4949     .05       0
  5048.2     .08       0
#XS Ineff= 2 , 0
       0    4937     125               0
Permanent Ineff=
       F       F
Bank Sta=4949,5048.2
XS Rating Curve= 0
Exp/Cntr=.5,.3

Type RM Length L Ch R = 1 ,18788   ,37.3,38,37.4
BEGIN DESCRIPTION:
Upstream Section of Bridge/Culvert/Weir
END DESCRIPTION:
XS GIS Cut Line= 4
      3081098.97      13948961.1      3080747.45     13948640.62
      3080603.59     13948601.49      3080321.38     13948534.78
#Sta/Elev= 30
  4434.7  128.02    4722  126.52  4904.2  123.53  4950.4  123.99  4973.9  122.78
  4974.4  121.51  4989.5  118.07  4993.3  111.83    5000  111.19    5005  111.72
    5010  115.12  5020.7  116.57  5037.3   121.8  5047.8  124.01  5068.1  123.42
  5082.9  124.21  5084.1  122.17  5086.8  120.02  5096.8  117.62  5106.8  115.82
  5126.8  115.32  5156.8  119.12  5166.8  119.62  5216.8  125.02  5246.8  125.02
  5276.8  127.22  5296.8  127.02  5326.8  127.82  5346.8  127.32  5372.4  128.22
#Mann= 6 ,-1 , 0
  4434.7     .07       0  4950.4     .08       0  4973.9     .05       0
  5047.8     .08       0  5082.9    .026       0  5216.8     .07       0
#XS Ineff= 2 , 0
       0  4974.6   123.6  5035.7       0   123.6
Permanent Ineff=
       F       F
#Block Obstruct= 1 ,-1
  5082.9 5209.25  124.19
Bank Sta=4973.9,5047.8
XS Rating Curve= 0
Exp/Cntr=.5,.3

Type RM Length L Ch R = 3 ,18769   ,,,
BEGIN DESCRIPTION:
18791 WD BRDG 500 FEET US OF SPRING CYPRESS RD.
Structure ID: BR K124-00-00-S6-2
END DESCRIPTION:
Bridge Culvert--1,0,-1,-1, 0
Deck Dist Width WeirC Skew NumUp NumDn MinLoCord MaxHiCord MaxSubmerge Is_Ogee
10,19,2.6,0, 35, 35, , , .95, 0, ,,,
  4950.4  4961.5  4974.5  4974.6  4974.7 4976.75  4976.9 4977.01  4983.5  4989.5
  4990.7  4991.9  4993.3    5000  5004.5    5005  5006.5    5008    5010  5020.4
  5020.7  5031.2  5035.2  5035.3 5035.39  5035.5 5035.61 5035.72  5035.8  5035.9
  5036.3  5037.3  5047.8  5049.3  5052.5
  123.98  123.68  123.64  125.06  125.06  125.06  125.06  125.06  125.06  125.06
  125.06  125.05  125.05  125.05  125.05  125.05  125.05  125.05  125.05  125.05
  125.05  125.05  125.05  125.05  125.05  125.05  125.05  125.05  125.05  123.64
  123.64  123.64     124  124.06  124.19
                                          121.91  121.91  121.91  121.91  121.91
  121.91   121.9   121.9   121.9   121.9   121.9   121.9   121.9   121.9   121.9
   121.9   121.9   121.9   121.9   121.9   121.9   121.9   121.9
                                        
  4950.4  4961.5  4974.5  4974.6  4974.7 4976.75  4976.9 4977.01  4983.5  4989.5
  4990.7  4991.9  4993.3    5000  5004.5    5005  5006.5    5008    5010  5020.4
  5020.7  5031.2  5035.2  5035.3 5035.39  5035.5 5035.61 5035.72  5035.8  5035.9
  5036.3  5037.3  5047.8  5049.3  5052.5
  123.98  123.68  123.64  125.06  125.06  125.06  125.06  125.06  125.06  125.06
  125.06  125.05  125.05  125.05  125.05  125.05  125.05  125.05  125.05  125.05
  125.05  125.05  125.05  125.05  125.05  125.05  125.05  125.05  125.05  123.64
  123.64  123.64     124  124.06  124.19
                                          121.91  121.91  121.91  121.91  121.91
  121.91   121.9   121.9   121.9   121.9   121.9   121.9   121.9   121.9   121.9
   121.9   121.9   121.9   121.9   121.9   121.9   121.9   121.9
                                        
Pier Skew, UpSta & Num, DnSta & Num=  ,4990.7, 2 ,4990.7, 2 , 0 , 0 , 0 ,,
       1       1
  114.18  122.91
       1       1
  113.19  121.92
Pier Skew, UpSta & Num, DnSta & Num=  ,5004.5, 2 ,5004.5, 2 , 0 , 0 , 0 ,,
       1       1
  110.28   122.9
       1       1
  109.29  121.91
Pier Skew, UpSta & Num, DnSta & Num=  ,5020.4, 2 ,5020.4, 2 , 0 , 0 , 0 ,,
       1       1
  114.75   122.9
       1       1
  113.76  121.91
BR Coef= 1 , 1 , 1 ,1.25, 0 ,,,.8,0,2,0,
WSPro=,,,, 1 ,,,, 0 ,,,, 0 ,,,,-1 ,-1 ,-1 , 0 , 0 , 0 , 0 , 0
BC Design=,, 0 ,, 0 ,,,,,,
BC HTab HWMax=128.22

Type RM Length L Ch R = 1 ,18750   ,99.2,100,99.3
BEGIN DESCRIPTION:
Downstream Section of Bridge/Culvert/Weir
END DESCRIPTION:
XS GIS Cut Line= 4
      3081116.42     13948929.52      3080761.34     13948605.79
       3080612.5      13948565.3      3080329.96     13948498.51
#Sta/Elev= 30
  4434.7  128.02    4722  126.52  4904.2  123.53  4950.4  123.99  4973.9  122.78
  4974.4  120.59  4989.5  117.15  4993.3  110.91    5000  110.27    5005   110.8
    5010   114.2  5020.7  115.65  5047.8  124.01  5068.1  123.42  5082.9  124.21
  5084.1  122.17  5086.8  120.02  5096.8  117.62  5106.8  115.82  5126.8  115.32
  5156.8  119.12  5166.8  119.62  5186.8  122.22  5216.8  125.02  5246.8  125.02
  5276.8  127.22  5296.8  127.02  5326.8  127.82  5346.8  127.32  5372.4  128.22
#Mann= 6 ,-1 , 0
  4434.7     .07       0  4950.4     .08       0  4973.9     .05       0
  5047.8     .08       0  5082.9    .026       0  5216.8     .07       0
#XS Ineff= 2 , 0
       0  4974.6  123.16  5035.7       0  123.16
Permanent Ineff=
       F       F
#Block Obstruct= 1 ,-1
 5082.58 5210.26  124.16
Bank Sta=4973.9,5047.8
XS Rating Curve= 0
Exp/Cntr=.5,.3