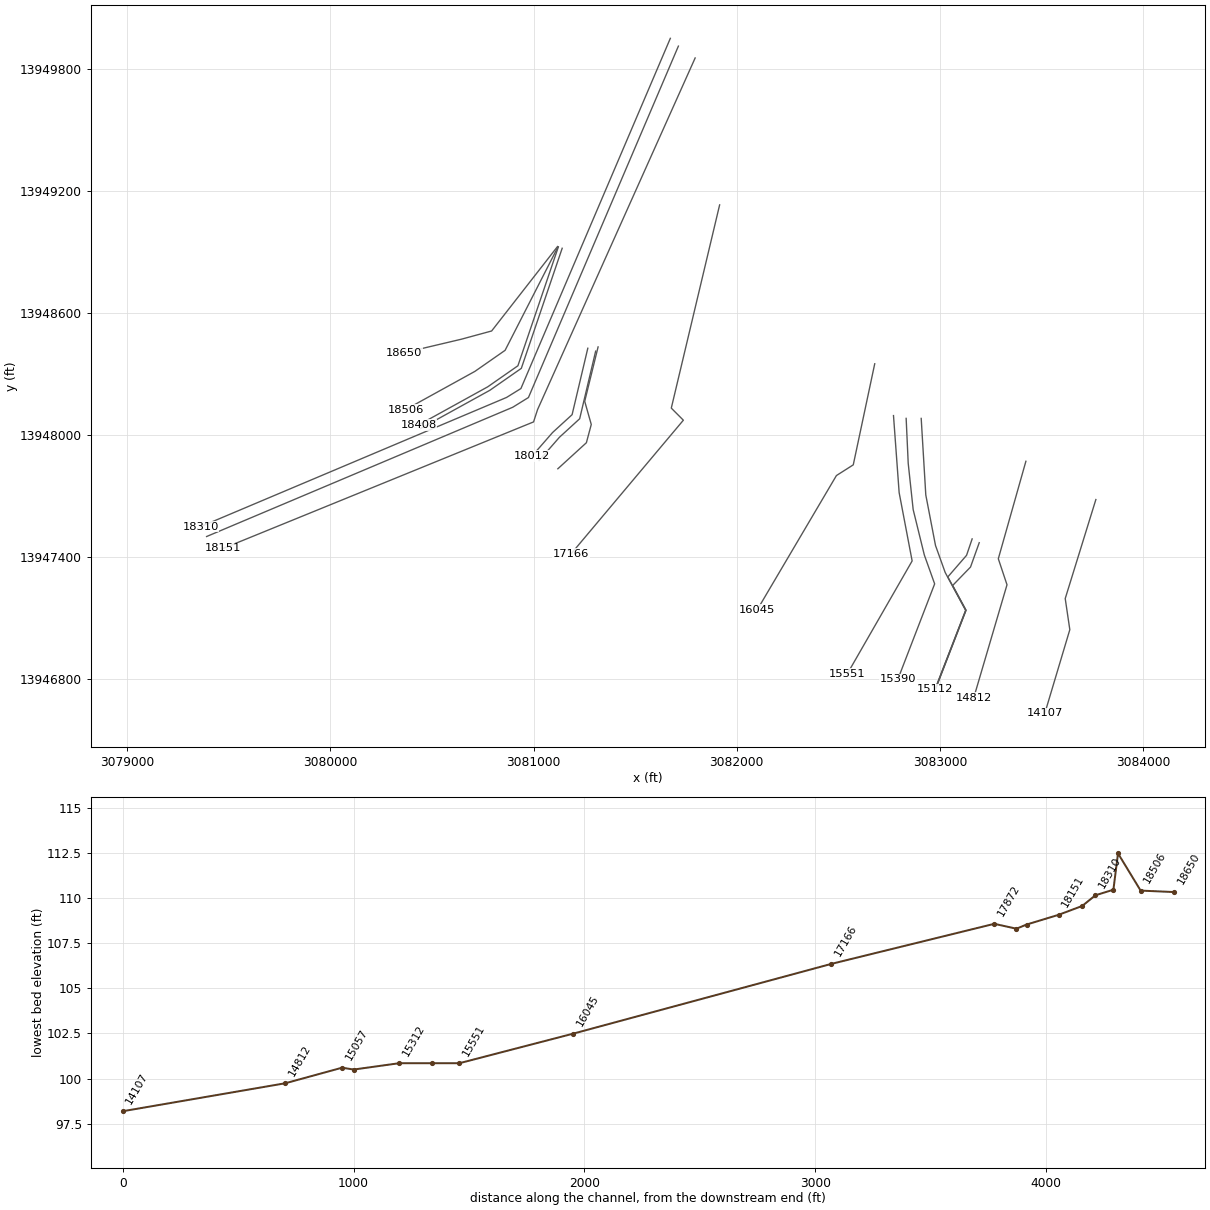
HEC-RAS study K124-00-00.prj: K124-00-00

--- K124-00-00.g05 (geometry) --- (continued)

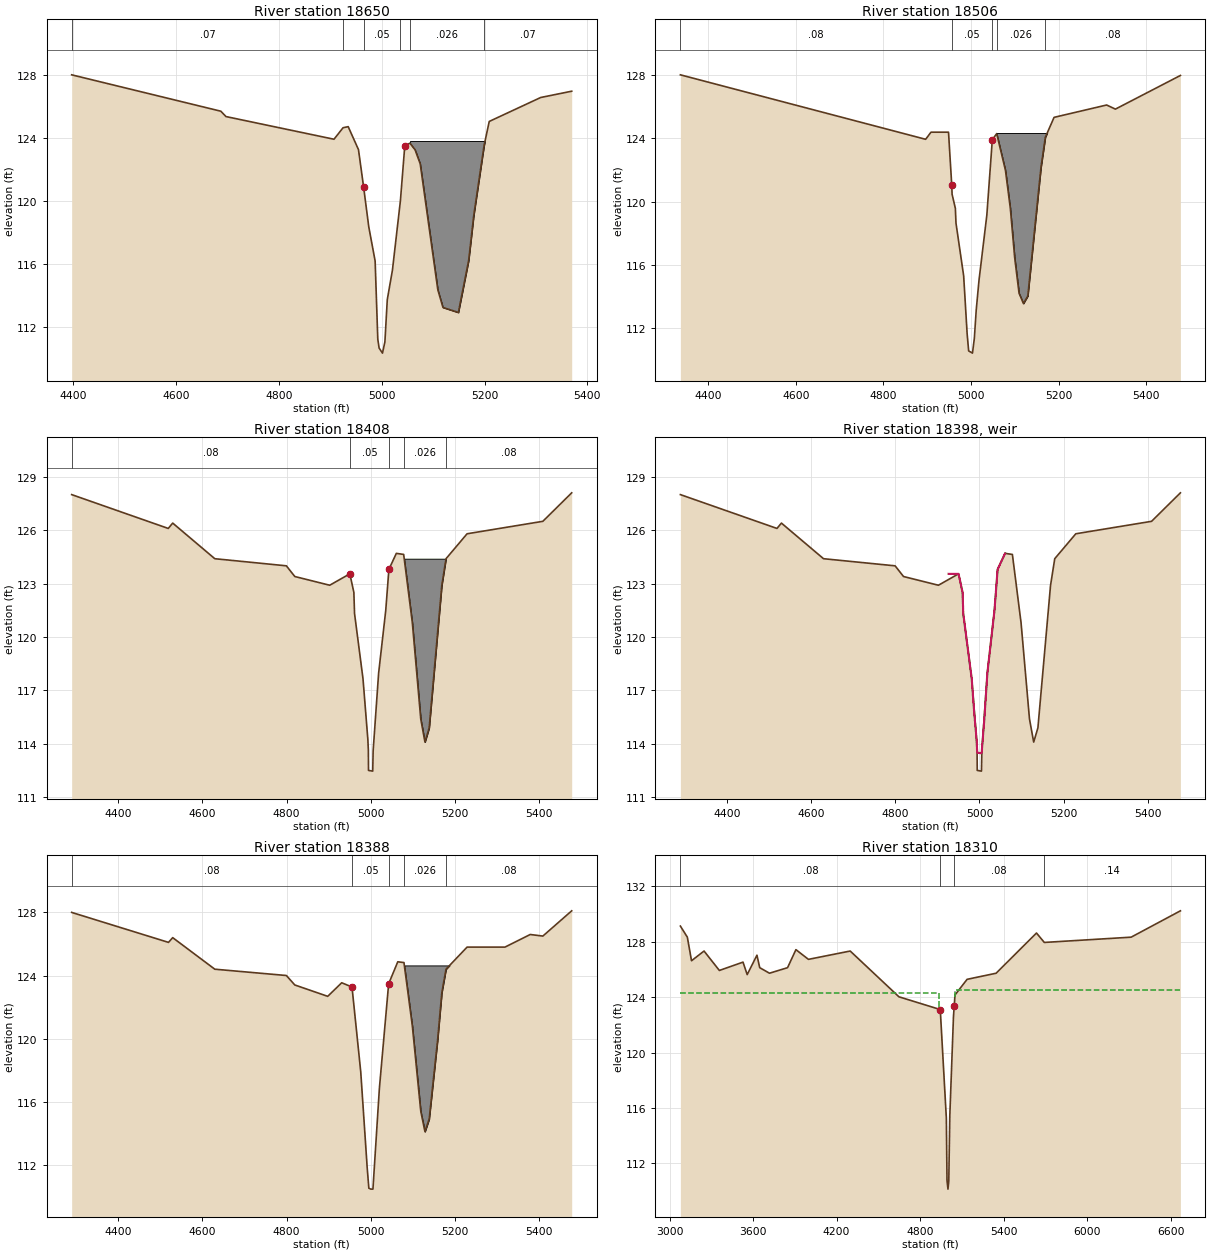
Type RM Length L Ch R = 1 ,18650   ,120.6,144,171.3
BEGIN DESCRIPTION:
WOOD BRIDGE_S6-2_DS-XS 1
END DESCRIPTION:
XS GIS Cut Line= 4
       3081118.1      13948927.9       3080793.7     13948511.94
      3080644.86     13948471.45      3080362.32     13948404.66
#Sta/Elev= 30
  4397.3     128  4687.3  125.69  4697.3  125.35  4907.3  123.91  4924.9  124.64
  4934.9  124.71  4954.9  123.25  4964.9  120.87  4974.9  118.35 4987.27  116.18
 4992.44  111.22 4995.03  110.65 5001.57  110.33 5006.24  111.04 5010.91  113.73
 5020.91   115.6 5036.42  120.01  5044.9  123.49  5054.9  123.66  5064.9  123.24
  5074.9  122.35  5109.1  114.36  5119.1  113.23  5149.1  112.91  5169.1  116.21
  5179.1  119.09  5199.1  123.51  5209.1  125.04  5309.1  126.56  5369.4  126.96
#Mann= 6 ,-1 , 0
  4397.3     .07       0  4924.9     .08       0  4964.9     .05       0
 5036.42     .08       0  5054.9    .026       0  5199.1     .07       0
#Block Obstruct= 1 ,-1
 5055.225214.233   123.8
Bank Sta=4964.9,5044.9
XS Rating Curve= 0
Exp/Cntr=.3,.1

Type RM Length L Ch R = 1 ,18506   ,97.4,98,98.9
BEGIN DESCRIPTION:
Weir_S6-1_US-XS 4
END DESCRIPTION:
XS GIS Cut Line= 4
      3081120.25      13948926.1      3080859.91      13948416.6
      3080711.44     13948313.02      3080371.38     13948125.22
#Sta/Elev= 30
  4336.6  128.02  4896.6  123.94  4908.8  124.39  4948.8  124.39  4956.1  121.08
    4957  120.46 4964.47  119.57 4965.86  118.64  4983.4   115.3 4991.36  111.63
 4994.81  110.55 5003.55  110.41  5007.8  111.35 5012.06  113.13 5018.39  115.01
  5036.3  119.14  5048.8  123.91  5058.8   124.3  5078.8  121.98  5089.9  119.59
  5099.9  116.45  5109.9   114.2  5119.9  113.55  5129.9  114.03  5159.9  122.15
  5169.9  124.07  5189.9  125.33  5309.9  126.11  5329.9  125.85  5478.3  127.98
#Mann= 5 ,-1 , 0
  4336.6     .08       0  4956.1     .05       0  5048.8     .08       0
  5058.8    .026       0  5169.9     .08       0
#Block Obstruct= 1 ,-1
 5057.535219.252  124.34
Bank Sta=4956.1,5048.8
XS Rating Curve= 0
Exp/Cntr=.7,.5

Type RM Length L Ch R = 1 ,18408   ,20,20,20.2
BEGIN DESCRIPTION:
Upstream Section of Bridge/Culvert/Weir
END DESCRIPTION:
XS GIS Cut Line= 4
      3081122.01     13948925.83      3080923.01     13948340.55
      3080774.55     13948236.97      3080434.49     13948049.17
#Sta/Elev= 30
  4289.6     128    4519   126.1  4529.6   126.4  4629.6   124.4  4799.6     124
  4819.6   123.4  4902.5  122.91  4950.3  123.55  4959.9  122.51  4961.5  121.32
  4981.6  117.66  4993.2  114.23  4994.3  113.65  4994.7  112.51  5004.7  112.47
  5005.7  113.61  5018.7  117.97  5035.6  121.49  5043.1   123.8  5060.8   124.7
  5078.2  124.64  5098.8   120.8  5118.8   115.4  5128.8   114.1  5138.8   114.9
  5168.8   122.9  5178.8   124.4  5228.8   125.8  5408.8   126.5  5477.3   128.1
#Mann= 5 ,-1 , 0
  4289.6     .08       0  4950.3     .05       0  5043.1     .08       0
  5078.2    .026       0  5178.8     .08       0
#XS Ineff= 2 , 0
       0  4983.2  114.24  5016.6       0  113.94
Permanent Ineff=
       F       F
#Block Obstruct= 1 ,-1
 5074.24 5222.18   124.4
Bank Sta=4950.3,5043.1
XS Rating Curve= 0
Exp/Cntr=.7,.5

Type RM Length L Ch R = 5 ,18398   ,,,
BEGIN DESCRIPTION:
100 FEET US FROM SPRING CYPRESS RD.
Structure ID: K124-00-00-S6-1
END DESCRIPTION:
IW Pilot Flow=0
#Inline Weir SE= 17
  4926.7  123.55  4950.3  123.55  4959.9  122.51  4961.5  121.32  4981.6  117.66
  4987.5  115.74  4993.2  114.23  4994.3  113.65  4994.7  113.51  5004.7  113.47
  5005.7  113.61  5006.6  113.93  5011.5  115.36  5018.7  117.97  5035.6  121.49
  5043.1   123.8  5060.8   124.7
IW Dist,WD,Coef,Skew,MaxSub,Min_El,Is_Ogee,SpillHt,DesHd
5,1,2.6,0,.95,, 0 ,1.5,10,0,0,

Type RM Length L Ch R = 1 ,18388   ,65.2,78,68.6
BEGIN DESCRIPTION:
Cross Section FIELD_DS
Located At: 100 FEET US FROM SPRING CYPRESS RD.
END DESCRIPTION:
XS GIS Cut Line= 4
      3081140.94     13948919.39      3080939.83      13948327.9
      3080785.13     13948219.97      3080444.16     13948031.66
#Sta/Elev= 30
  4289.6     128  4519.6   126.1  4529.6   126.4  4629.6   124.4  4799.6     124
  4819.6   123.4  4897.8  122.68    4931  123.54  4955.5  123.27  4976.3  117.88
  4991.5  111.84  4995.5  110.52  5000.2  110.46  5005.2  110.46  5020.5  116.84
  5042.5  123.47  5064.2  124.87  5078.9  124.82  5098.8   120.8  5118.8   115.4
  5128.8   114.1  5138.8   114.9  5158.8   119.9  5168.8   122.9  5178.8   124.4
  5228.8   125.8  5318.8   125.8  5378.8   126.6  5408.8   126.5  5477.3   128.1
#Mann= 5 ,-1 , 0
  4289.6     .08       0  4955.5     .05       0  5042.5     .08       0
  5078.9    .026       0  5178.8     .08       0
#Block Obstruct= 1 ,-1
  5077.9 5194.06  124.64
Bank Sta=4955.5,5042.5
XS Rating Curve= 0
Exp/Cntr=.7,.5

Type RM Length L Ch R = 1 ,18310   ,63.4,57,56.2
BEGIN DESCRIPTION:
Upstream Section of Bridge/Culvert/Weir
END DESCRIPTION:
XS GIS Cut Line= 4
      3081673.22      13949953.3      3080937.81     13948228.43
      3080867.11     13948184.57      3079361.96     13947548.53
#Sta/Elev= 30
  3078.1  129.12  3128.1  128.32  3158.1  126.62  3248.1  127.32  3358.1  125.92
  3528.1  126.52  3558.1  125.62  3628.1  127.02  3648.1  126.12  3718.1  125.72
  3848.1  126.12  3908.1  127.42  3998.1  126.72  4298.1  127.32  4648.1  124.02
  4945.1   123.1  4988.8  115.27  4993.6  110.77  5000.5  110.15  5006.3  110.72
  5013.7  115.44  5039.9  122.57 5045.61  123.38    5051  124.15  5137.9  125.28
  5346.4  125.72  5636.4  128.62  5692.6  127.94  6316.4  128.32  6670.4  130.22
#Mann= 4 ,-1 , 0
  3078.1     .08       0  4945.1     .05       0 5045.61     .08       0
  5692.6     .14       0
#XS Ineff= 2 , 0
       0    4934   124.3 5049.75       0   124.5
Permanent Ineff=
       F       F
Bank Sta=4945.1,5045.61
XS Rating Curve= 0
Exp/Cntr=.5,.3

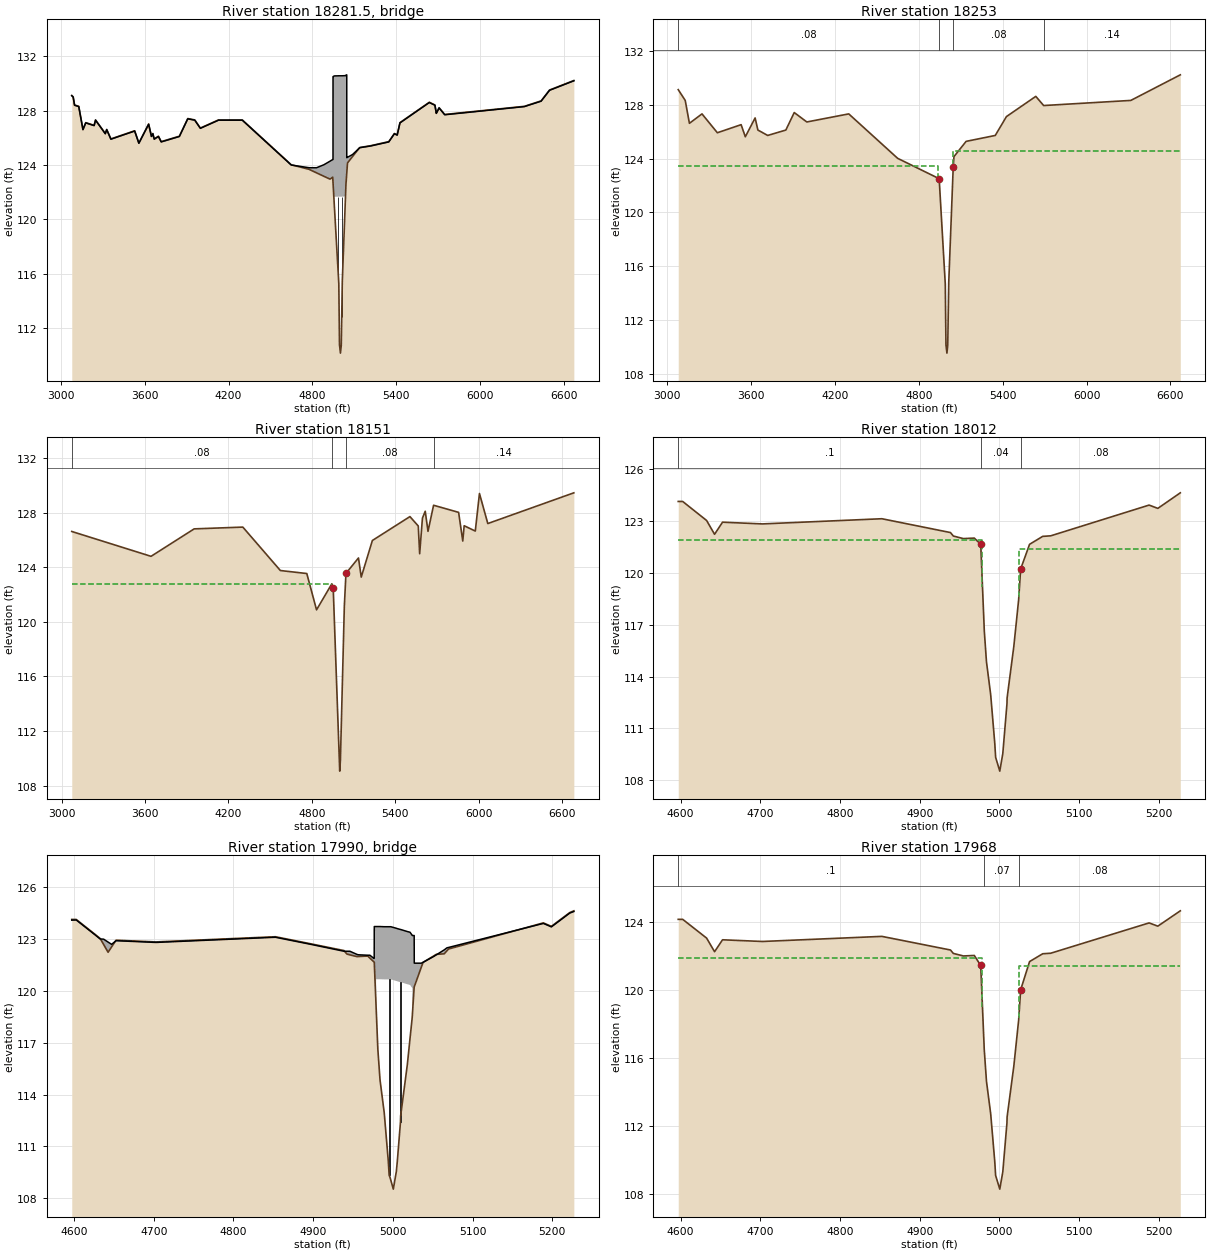
Type RM Length L Ch R = 3 ,18281.5 ,,,
BEGIN DESCRIPTION:
18313 SPRING CYPRESS ROAD
Structure ID: K124-00-00-S6
END DESCRIPTION:
Bridge Culvert--1,0,-1,-1, 0
Deck Dist Width WeirC Skew NumUp NumDn MinLoCord MaxHiCord MaxSubmerge Is_Ogee
10,35,2.6,0, 75, 75, , , .95, 0, ,,,
  3078.1  3088.1  3098.1  3128.1  3158.1  3178.1  3238.1  3248.1  3318.1  3328.1
  3358.1  3528.1  3558.1  3562.2  3628.1  3648.1  3658.1  3668.1  3698.1  3718.1
  3848.1  3908.1  3958.1  3998.1  4128.1  4298.1  4648.1  4776.5  4776.6  4806.6
  4826.6  4829.8  4881.8  4925.5    4930  4945.1 4947.19  4947.3 4947.41 4952.81
 4952.93 4952.98  4957.5  4988.8  4993.6  5000.5  5006.3  5013.7  5035.5 5036.27
 5036.45  5036.6  5039.9 5045.39  5045.5 5045.61    5051  5086.9  5137.9  5140.8
  5216.4  5346.4  5386.4  5406.4  5426.4  5636.4  5676.4  5686.4  5692.6  5706.4
  5746.4  6316.4  6436.4  6496.4  6670.4
   129.1     129   128.4   128.3   126.6   127.1   126.9   127.3   126.3   126.6
   125.9   126.5   125.6  125.68     127   126.1   126.3   125.9   126.1   125.7
   126.1   127.4   127.3   126.7   127.3   127.3     124   123.8   123.8   123.8
   123.8   123.8  124.02  124.28  124.31   124.4  124.41  130.51  130.51  130.54
  130.54  130.54  130.56  130.57  130.57  130.57  130.57  130.57  130.58  130.58
  130.59  130.59  130.61  130.64  130.64  124.54  124.57  124.77  125.27  125.28
   125.4   125.7   126.3   126.2   127.1   128.6   128.4   127.8  127.92   128.2
   127.7   128.3   128.7   129.5   130.2
                                                                                
                                                                                
                                                                                
                                                                                
          121.66  121.66  121.67  121.67  121.67  121.67  121.67  121.68  121.68
  121.69
                                                                                
                                        
  3078.1  3088.1  3098.1  3128.1  3158.1  3178.1  3238.1  3248.1  3318.1  3328.1
  3358.1  3528.1  3558.1  3562.2  3628.1  3648.1  3658.1  3668.1  3698.1  3718.1
  3848.1  3908.1  3958.1  3998.1  4128.1  4298.1  4648.1  4776.5  4776.6  4806.6
  4826.6  4829.8  4881.8  4925.5    4930  4945.1 4947.19  4947.3 4947.41 4952.81
 4952.93 4952.98  4957.5  4988.8  4993.6  5000.5  5006.3  5013.7  5035.5 5036.27
 5036.45  5036.6  5039.9 5045.39  5045.5 5045.61    5051  5086.9  5137.9  5140.8
  5216.4  5346.4  5386.4  5406.4  5426.4  5636.4  5676.4  5686.4  5692.6  5706.4
  5746.4  6316.4  6436.4  6496.4  6670.4
   129.1     129   128.4   128.3   126.6   127.1   126.9   127.3   126.3   126.6
   125.9   126.5   125.6  125.68     127   126.1   126.3   125.9   126.1   125.7
   126.1   127.4   127.3   126.7   127.3   127.3     124   123.8   123.8   123.8
   123.8   123.8  124.02  124.28  124.31   124.4  124.41  130.51  130.51  130.54
  130.54  130.54  130.56  130.57  130.57  130.57  130.57  130.57  130.58  130.58
  130.59  130.59  130.61  130.64  130.64  124.54  124.57  124.77  125.27  125.28
   125.4   125.7   126.3   126.2   127.1   128.6   128.4   127.8  127.92   128.2
   127.7   128.3   128.7   129.5   130.2
                                                                                
                                                                                
                                                                                
                                                                                
          121.66  121.66  121.67  121.67  121.67  121.67  121.67  121.68  121.68
  121.69
                                                                                
                                        
Pier Skew, UpSta & Num, DnSta & Num=  ,4983.6, 2 ,4983.6, 2 , 0 , 0 , 0 ,,
     1.3     1.3
  115.07  122.67
     1.3     1.3
  114.46  122.06
Pier Skew, UpSta & Num, DnSta & Num=  ,5009.6, 2 ,5009.6, 2 , 0 , 0 , 0 ,,
     1.3     1.3
  111.39  122.67
     1.3     1.3
  110.78  122.06
BR Coef= 1 , 1 , 1 ,1.25, 0 ,,,.8,0,2,0,
WSPro=,,,, 1 ,,,, 0 ,,,, 0 ,,,,-1 ,-1 ,-1 , 0 , 0 , 0 , 0 , 0
BR U #Sta/Elev= 75
  3078.1  129.12  3088.1  129.02  3098.1  128.42  3128.1  128.32  3158.1  126.62
  3178.1  127.12  3238.1  126.92  3248.1  127.32  3318.1  126.32  3328.1  126.62
  3358.1  125.92  3528.1  126.52  3558.1  125.62  3562.2   125.7  3628.1  127.02
  3648.1  126.12  3658.1  126.32  3668.1  125.92  3698.1  126.12  3718.1  125.72
  3848.1  126.12  3908.1  127.42  3958.1  127.32  3998.1  126.72  4128.1  127.32
  4298.1  127.32  4648.1  124.02  4776.5  123.68  4776.6  123.68  4806.6  123.53
  4826.6  123.44  4829.8  123.42  4881.8  123.17  4925.5  122.96    4930  122.99
  4945.1   123.1 4947.19  122.73  4947.3  122.71 4947.41  122.69 4952.81  121.72
 4952.93   121.7    4953  121.68  4957.5  120.88  4988.8  115.27  4993.6  110.77
  5000.5  110.15  5006.3  110.72  5013.7  115.44  5035.5  121.37 5036.27  121.58
 5036.39  121.61  5036.6  121.67  5039.9  122.57 5045.39  123.35  5045.5  123.37
 5045.61  123.38    5051  124.15  5086.9  124.62  5137.9  125.28  5140.8  125.29
  5216.4  125.42  5346.4  125.72  5386.4  126.32  5406.4  126.22  5426.4  127.12
  5636.4  128.62  5676.4  128.42  5686.4  127.82  5692.6  127.94  5706.4  128.22
  5746.4  127.72  6316.4  128.32  6436.4  128.72  6496.4  129.52  6670.4  130.22
BR U #Mann= 4
  3078.1     .08  4945.1     .04  5039.9     .08  5692.6     .14
BR D #Sta/Elev= 75
  3078.1  129.12  3088.1  129.02  3098.1  128.42  3128.1  128.32  3158.1  126.62
  3178.1  127.12  3238.1  126.92  3248.1  127.32  3318.1  126.32  3328.1  126.62
  3358.1  125.92  3528.1  126.52  3558.1  125.62  3562.2   125.7  3628.1  127.02
  3648.1  126.12  3658.1  126.32  3668.1  125.92  3698.1  126.12  3718.1  125.72
  3848.1  126.12  3908.1  127.42  3958.1  127.32  3998.1  126.72  4128.1  127.32
  4298.1  127.32  4648.1  124.02  4776.5  123.68  4776.6  123.68  4806.6  123.53
  4826.6  123.44  4829.8  123.42  4881.8  123.17  4925.5  122.96    4930  122.99
  4945.1  122.51 4947.19  122.14  4947.3  122.12 4947.41   122.1 4952.81  121.13
 4952.93  121.11    4953  121.09  4957.5  120.29  4988.8  114.68  4993.6  110.18
  5000.5  109.56  5006.3  110.13  5013.7  114.85  5035.5  120.78 5036.27  120.99
 5036.39  121.02  5036.6  121.08  5039.9  121.98 5045.39  122.76  5045.5  123.37
 5045.61  123.38    5051  124.15  5086.9  124.62  5137.9  125.28  5140.8  125.29
  5216.4  125.42  5346.4  125.72  5386.4  126.32  5406.4  126.22  5426.4  127.12
  5636.4  128.62  5676.4  128.42  5686.4  127.82  5692.6  127.94  5706.4  128.22
  5746.4  127.72  6316.4  128.32  6436.4  128.72  6496.4  129.52  6670.4  130.22
BR D #Mann= 4
  3078.1     .08  4945.1     .04  5039.9     .08  5692.6     .14
BC Design=,, 0 ,, 0 ,,,,,,
BC HTab HWMax=130.22

Type RM Length L Ch R = 1 ,18253   ,70.5,102,136.2
BEGIN DESCRIPTION:
Downstream Section of Bridge/Culvert/Weir
END DESCRIPTION:
XS GIS Cut Line= 4
      3081712.84     13949914.94      3080974.95     13948184.25
      3080897.55     13948136.24      3079390.97     13947499.59
#Sta/Elev= 30
  3078.1  129.12  3128.1  128.32  3158.1  126.62  3248.1  127.32  3358.1  125.92
  3528.1  126.52  3558.1  125.62  3628.1  127.02  3648.1  126.12  3718.1  125.72
  3848.1  126.12  3908.1  127.42  3998.1  126.72  4298.1  127.32  4648.1  124.02
  4945.1  122.51  4988.8  114.68  4993.6  110.18  5000.5  109.56  5006.3  110.13
  5013.7  114.85 5045.61  123.38    5051  124.15  5137.9  125.28  5346.4  125.72
  5426.4  127.12  5636.4  128.62  5692.6  127.94  6316.4  128.32  6670.4  130.22
#Mann= 4 ,-1 , 0
  3078.1     .08       0  4945.1     .04       0 5045.61     .08       0
  5692.6     .14       0
#XS Ineff= 2 , 0
       0 4938.43  123.43 5046.57       0  124.54
Permanent Ineff=
       F       F
Bank Sta=4945.1,5045.61
XS Rating Curve= 0
Exp/Cntr=.5,.3

Type RM Length L Ch R = 1 ,18151   ,165,139,132.8
BEGIN DESCRIPTION:
S6_SPRING CYPRESS-DS-XS 1
END DESCRIPTION:
XS GIS Cut Line= 4
      3081795.36      13949856.6      3081019.69     13948124.58
      3081000.03      13948064.1      3079473.49     13947441.34
#Sta/Elev= 30
  3073.8  126.62  3643.8   124.8  3953.8  126.81  4303.8  126.94  4573.8  123.76
  4763.8  123.54  4833.8  120.88  4943.8  122.79  4953.8  122.45 5000.55  109.07
 5005.42  109.87 5033.65  121.14  5045.3  123.55  5135.3  124.68  5155.3  123.28
  5235.3  125.96  5505.3  127.71  5565.3  127.02  5575.3  124.99  5595.3   127.6
  5615.3   128.1  5635.3  126.63  5675.3  128.54  5855.3  128.02  5885.3  125.92
  5895.3  127.04  5975.3  126.65  6005.3   129.4  6065.3   127.2  6683.9  129.45
#Mann= 4 ,-1 , 0
  3073.8     .08       0  4943.8     .04       0  5045.3     .08       0
  5675.3     .14       0
#XS Ineff= 2 , 0
       0    4943   122.8    5135       0   124.6
Permanent Ineff=
       F       F
Bank Sta=4953.8,5045.3
XS Rating Curve= 0
Exp/Cntr=.5,.3

Type RM Length L Ch R = 1 ,18012   ,46.5,44,43.8
BEGIN DESCRIPTION:
Upstream Section of Bridge/Culvert/Weir
END DESCRIPTION:
XS GIS Cut Line= 4
      3081267.05     13948426.93      3081189.76     13948099.83
      3081093.64     13948011.84      3080993.08     13947896.49
#Sta/Elev= 30
    4597  124.14  4602.6  124.14  4632.6  123.04  4642.6  122.24  4652.6  122.94
  4702.6  122.84  4852.6  123.14  4938.7  122.34  4942.3  122.14  4954.9  121.99
  4968.6  122.02  4976.7  121.66  4981.2  116.62  4983.9  114.86  4989.2  112.95
  4994.3  110.15  4995.4  109.33  5000.6  108.53  5004.4  109.55  5009.6  112.42
  5009.8  112.77  5018.2  115.74  5024.3  118.46  5026.8  120.23    5038  121.66
  5054.5  122.12  5064.5  122.15    5188  123.93    5199  123.74  5227.2  124.64
#Mann= 3 ,-1 , 0
    4597      .1       0  4976.7     .04       0  5026.8     .08       0
#XS Ineff= 2 , 0
       0  4978.9  121.89  5024.5       0  121.41
Permanent Ineff=
       F       F
Bank Sta=4976.7,5026.8
XS Rating Curve= 0
Exp/Cntr=.5,.3

Type RM Length L Ch R = 3 ,17990   ,,,
BEGIN DESCRIPTION:
18015 WD BRDG 270 FEET DS OF SPRING CYPRESS RD
Structure ID: K124-00-00-S5-1
END DESCRIPTION:
Bridge Culvert--1,0,-1,-1, 0
Deck Dist Width WeirC Skew NumUp NumDn MinLoCord MaxHiCord MaxSubmerge Is_Ogee
10,19,2.6,0, 66, 66, , , .95, 0, ,,,
    4597  4602.6    4627  4632.6    4637  4642.6    4647  4652.6  4702.6  4852.6
    4857    4897  4938.7  4940.8  4942.3  4946.1  4954.9  4956.1  4958.9  4968.6
  4971.2  4976.1  4976.6  4976.7  4978.5 4978.61  4978.7 4978.89    4979 4979.11
  4981.1  4981.2  4983.9  4989.2  4994.3  4995.4  4996.4  4997.4  5000.6  5004.4
  5005.6  5009.6  5009.8  5018.2  5021.6 5024.49 5024.69  5024.8  5024.9 5025.01
  5025.4  5026.8  5026.9  5035.7    5038  5051.4  5054.5  5064.5    5068    5070
    5188    5189    5198    5199  5222.1  5227.2
   124.1  124.11  123.22  123.01     123  122.83   122.7  122.91  122.81  123.11
  123.07   122.7   122.3   122.3   122.3   122.3  122.12   122.1  122.09  122.07
  122.07  121.89  121.89  123.73  123.73  123.73  123.73  123.73  123.73  123.73
  123.73  123.73  123.73  123.72  123.72  123.72  123.72  123.72  123.68  123.63
  123.61  123.56  123.56  123.44   123.4  123.21  123.21  123.21  123.21  123.21
  123.21  123.21  121.61  121.61  121.66     122  122.09  122.38   122.5  122.52
   123.9  123.91  123.73  123.71  124.51   124.6
                                                                                
                                                                                
                                                                  120.68  120.68
  120.68  120.68  120.68  120.67  120.67  120.67  120.67  120.67  120.63  120.58
  120.56  120.51  120.51  120.39  120.35  120.16
                                                                                
                                                
    4597  4602.6    4627  4632.6    4637  4642.6    4647  4652.6  4702.6  4852.6
    4857    4897  4938.7  4940.8  4942.3  4946.1  4954.9  4956.1  4958.9  4968.6
  4971.2  4976.1  4976.6  4976.7  4978.5 4978.61  4978.7 4978.89    4979 4979.11
  4981.1  4981.2  4983.9  4989.2  4994.3  4995.4  4996.4  4997.4  5000.6  5004.4
  5005.6  5009.6  5009.8  5018.2  5021.6 5024.49 5024.69  5024.8  5024.9 5025.01
  5025.4  5026.8  5026.9  5035.7    5038  5051.4  5054.5  5064.5    5068    5070
    5188    5189    5198    5199  5222.1  5227.2
   124.1  124.11  123.22  123.01     123  122.83   122.7  122.91  122.81  123.11
  123.07   122.7   122.3   122.3   122.3   122.3  122.12   122.1  122.09  122.07
  122.07  121.89  121.89  123.73  123.73  123.73  123.73  123.73  123.73  123.73
  123.73  123.73  123.73  123.72  123.72  123.72  123.72  123.72  123.68  123.63
  123.61  123.56  123.56  123.44   123.4  123.21  123.21  123.21  123.21  123.21
  123.21  123.21  121.61  121.61  121.66     122  122.09  122.38   122.5  122.52
   123.9  123.91  123.73  123.71  124.51   124.6
                                                                                
                                                                                
                                                                  120.68  120.68
  120.68  120.68  120.68  120.67  120.67  120.67  120.67  120.67  120.63  120.58
  120.56  120.51  120.51  120.39  120.35  120.16
                                                                                
                                                
Pier Skew, UpSta & Num, DnSta & Num=  ,4995.4, 2 ,4995.4, 2 , 0 , 0 , 0 ,,
       1       1
  108.24  121.67
       1       1
  108.03  121.46
Pier Skew, UpSta & Num, DnSta & Num=  ,5009.6, 2 ,5009.6, 2 , 0 , 0 , 0 ,,
       1       1
  111.09  121.52
       1       1
  110.88  121.31
BR Coef= 1 , 1 , 1 ,1.25, 0 ,,,.8,0,2,0,
WSPro=,,,, 1 ,,,, 0 ,,,, 0 ,,,,-1 ,-1 ,-1 , 0 , 0 , 0 , 0 , 0
BR U #Sta/Elev= 67
    4597  124.14  4602.6  124.14    4627  123.25  4632.6  123.04    4637  122.69
  4642.6  122.24    4647  122.55  4652.6  122.94  4702.6  122.84  4852.6  123.14
    4857   123.1    4897  122.73  4938.7  122.34  4940.8  122.22  4942.3  122.14
  4946.1  122.09  4954.9  121.99  4956.1  121.99  4958.9     122  4968.6  122.02
  4971.2   121.9  4976.1  121.69  4976.7  121.66  4978.5  119.64 4978.61  119.52
  4978.7  119.42 4978.89  119.21    4979  119.08 4979.11  118.96  4981.1  116.73
  4981.2  116.62  4983.9  114.86  4989.2  112.95  4994.3  110.15  4995.4  109.33
  4996.4  109.22  4997.4  109.06  5000.6  108.53  5004.4  109.55  5005.6  110.13
  5009.6  112.42  5009.8  112.77  5018.2  115.74  5021.6  117.26  5024.3  118.46
  5024.4  118.53 5024.49  118.59  5024.6  118.67 5024.69  118.74  5024.8  118.81
  5024.9  118.88 5025.01  118.96  5025.4  119.24  5026.8  120.23  5035.7  121.37
    5038  121.66  5051.4  122.03  5054.5  122.12  5064.5  122.15    5068  122.33
    5070  122.43    5188  123.93    5189  123.94    5198  123.76    5199  123.74
  5222.1  124.54  5227.2  124.64
BR U #Mann= 3
    4597      .1  4976.7     .04  5026.8     .08
BR D #Sta/Elev= 67
    4597  124.14  4602.6  124.14    4627  123.25  4632.6  123.04    4637  122.69
  4642.6  122.24    4647  122.55  4652.6  122.94  4702.6  122.84  4852.6  123.14
    4857   123.1    4897  122.73  4938.7  122.34  4940.8  122.22  4942.3  122.14
  4946.1  122.09  4954.9  121.99  4956.1  121.99  4958.9     122  4968.6  122.02
  4971.2   121.9  4976.1  121.46  4976.7  121.43  4978.5  119.41 4978.61  119.29
  4978.7  119.19 4978.89  118.98    4979  118.85 4979.11  118.73  4981.1   116.5
  4981.2  116.39  4983.9  114.63  4989.2  112.72  4994.3  109.92  4995.4   109.1
  4996.4  108.99  4997.4  108.83  5000.6   108.3  5004.4  109.32  5005.6   109.9
  5009.6  112.19  5009.8  112.54  5018.2  115.51  5021.6  117.03  5024.3  118.23
  5024.4   118.3 5024.49  118.36  5024.6  118.44 5024.69  118.51  5024.8  118.58
  5024.9  118.65 5025.01  118.73  5025.4  119.01  5026.8     120  5035.7  121.37
    5038  121.66  5051.4  122.03  5054.5  122.12  5064.5  122.15    5068  122.33
    5070  122.43    5188  123.93    5189  123.94    5198  123.76    5199  123.74
  5222.1  124.54  5227.2  124.64
BR D #Mann= 3
    4597      .1  4981.1     .04  5024.3     .08
BC Design=,, 0 ,, 0 ,,,,,,
BC HTab HWMax=124.64

Type RM Length L Ch R = 1 ,17968   ,163.3,96,94
BEGIN DESCRIPTION:
Downstream Section of Bridge/Culvert/Weir
END DESCRIPTION:
XS GIS Cut Line= 4
       3081305.7     13948412.74        3081227.     13948079.64
      3081127.16     13947988.25      3081027.34     13947873.75
#Sta/Elev= 30
    4597  124.14  4602.6  124.14  4632.6  123.04  4642.6  122.24  4652.6  122.94
  4702.6  122.84  4852.6  123.14  4938.7  122.34  4942.3  122.14  4954.9  121.99
  4968.6  122.02  4976.7  121.43  4981.1   116.5  4983.9  114.63  4989.2  112.72
  4994.3  109.92  4995.4   109.1  5000.6   108.3  5004.4  109.32  5009.6  112.19
  5009.8  112.54  5018.2  115.51  5024.3  118.23  5026.8     120    5038  121.66
  5054.5  122.12  5064.5  122.15    5188  123.93    5199  123.74  5227.2  124.64
#Mann= 3 ,-1 , 0
    4597      .1       0  4981.1     .07       0  5024.3     .08       0
#XS Ineff= 2 , 0
       0  4978.9  121.89  5024.5       0  121.41
Permanent Ineff=
       F       F
Bank Sta=4976.7,5026.8
XS Rating Curve= 0
Exp/Cntr=.5,.3

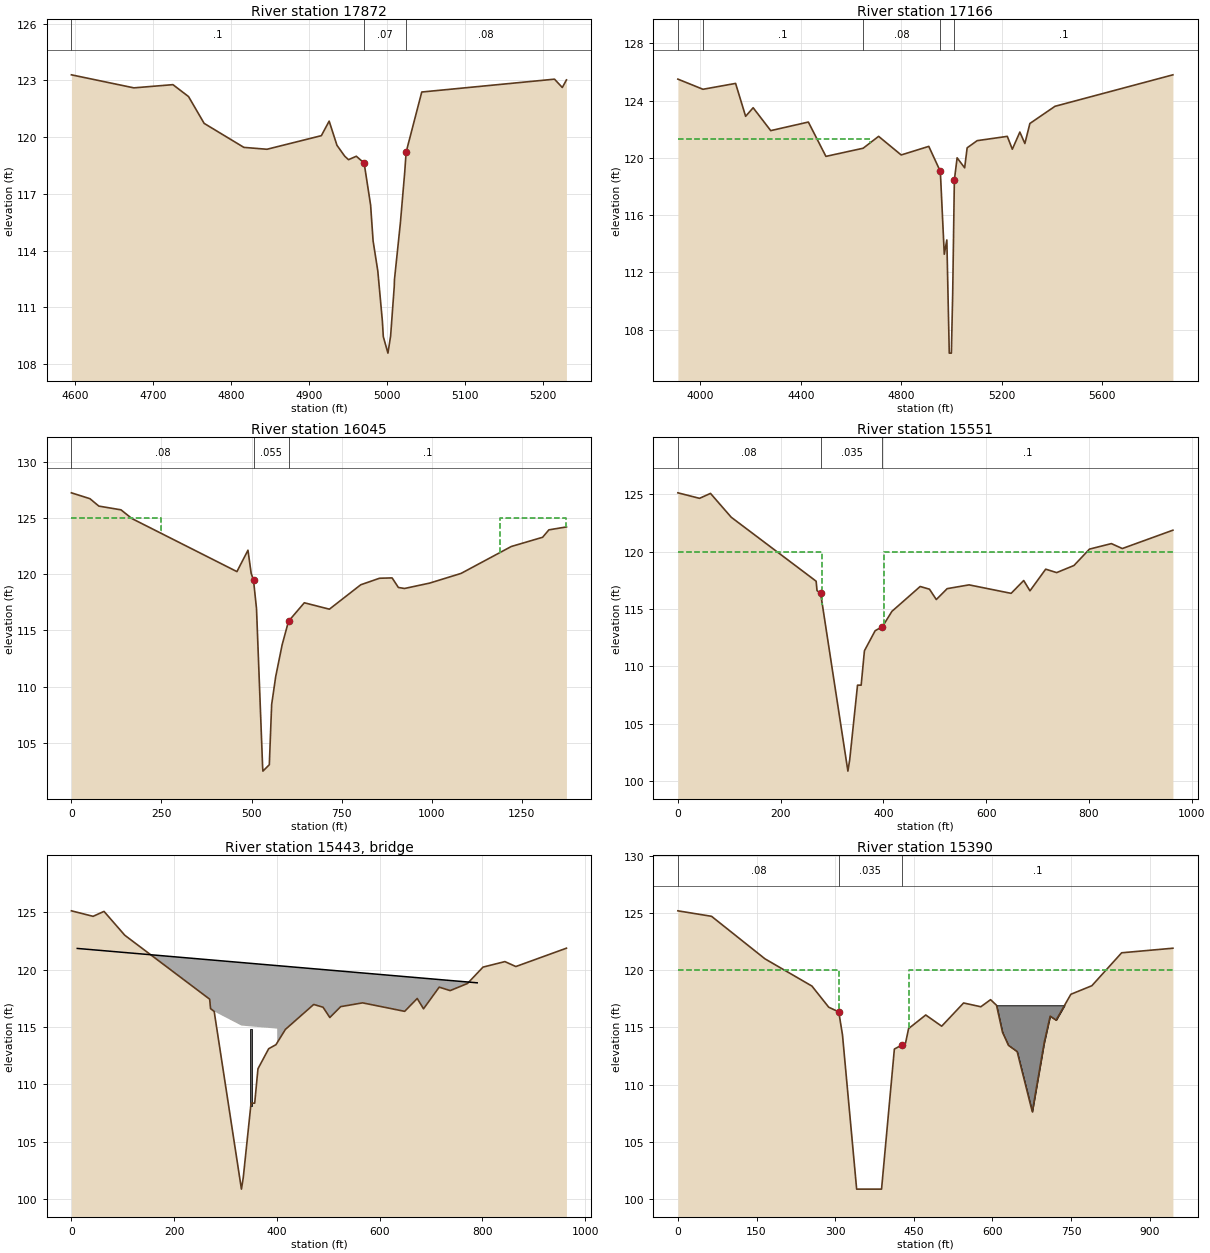
Type RM Length L Ch R = 1 ,17872   ,436.3,706,738.1
BEGIN DESCRIPTION:
WOOD BRIDGE_S5-1_DS-XS 1
END DESCRIPTION:
XS GIS Cut Line= 5
     3081317.662    13948433.444     3081251.786    13948165.504
      3081284.09    13948051.488      3081260.02    13947961.541
     3081119.573    13947833.301
#Sta/Elev= 30
  4595.6   123.3  4675.6  122.61  4725.6  122.78  4745.6  122.15  4765.6  120.73
 4816.47  119.46  4846.1  119.36  4915.7  120.08  4925.7  120.85  4935.7  119.57
  4945.7  118.99  4950.5  118.81  4960.5  118.99  4970.5  118.63 4978.78  116.41
 4981.97  114.51    4988  112.92 4993.81  110.29 4995.06  109.44 5000.98  108.57
 5004.42  109.48 5009.12  112.13 5009.31  112.45 5016.91  115.46 5022.43  118.12
  5024.3  119.21  5044.3  122.39  5214.3  123.07  5224.3  122.63  5229.6  123.03
#Mann= 3 , 0 , 0
  4595.6      .1       0  4970.5     .07       0  5024.3     .08       0
Bank Sta=4970.5,5024.3
XS Rating Curve= 0
Exp/Cntr=.3,.1

Type RM Length L Ch R = 1 ,17166   ,1060.59,1117.18,895.34
BEGIN DESCRIPTION:
Cross Section K124-00-00-X09
END DESCRIPTION:
XS GIS Cut Line= 4
      3081915.81      13949132.9      3081677.92     13948132.05
       3081737.3     13948072.48      3081184.31      13947413.8
#Sta/Elev= 30
  3909.9   125.5  4009.9  124.79  4139.9   125.2  4179.9   122.9  4209.9   123.5
  4279.9   121.9  4429.9   122.5  4499.9   120.1  4648.3  120.67  4709.9   121.5
  4799.9   120.2  4909.9   120.8  4955.9  119.05  4971.6  113.26  4981.8  114.26
  4991.5  106.35  4999.9  106.35  5005.2  110.58  5011.8  118.45  5022.8     120
  5052.8   119.3  5062.8   120.7  5102.8   121.2  5222.8   121.5  5242.8   120.6
  5272.8   121.8  5292.8     121  5312.8   122.4  5412.8   123.6  5882.8   125.8
#Mann= 5 ,-1 , 0
  3909.9     .08       0  4009.9      .1       0  4648.3     .08       0
  4955.9     .07       0  5011.8      .1       0
#XS Ineff= 2 , 0
       0    4676   121.3    5220       0   121.4
Permanent Ineff=
       F       F
Bank Sta=4955.9,5011.8
XS Rating Curve= 0
Exp/Cntr=.3,.1

Type RM Length L Ch R = 1 ,16045   ,384.61,493.7,495.6
BEGIN DESCRIPTION:
Dodson Cross Section
END DESCRIPTION:
XS GIS Cut Line= 4
 3082679.115685513948350.3252068 3082573.547519113947852.6467081
 3082490.6011027 13947799.862625 3082101.004298213947138.8048213
#Sta/Elev= 30
       0  127.22    51.4   126.7   76.18  126.04  137.52  125.71  168.17  124.93
  459.53  120.22  490.19  122.12  499.03  120.07  505.53  119.47   513.9  116.93
  530.82  102.89  531.68  102.49  549.46  103.06  555.94  108.41  567.23   110.9
  585.01  113.71  602.79  115.81  646.61  117.45  716.25  116.88  803.31  119.05
  855.54  119.63  890.36  119.66  907.78  118.81  924.94  118.72  994.83   119.2
 1081.89  120.06 1221.18  122.45 1308.23  123.27 1325.64  123.93 1374.39  124.19
#Mann= 3 ,-1 , 0
       0     .08       0  505.53    .055       0  602.79      .1       0
#XS Ineff= 2 , 0
       0     250     125    1190       0     125
Permanent Ineff=
       F       F
Bank Sta=505.53,602.79
XS Rating Curve= 0
Exp/Cntr=.5,.3

Type RM Length L Ch R = 1 ,15551   ,87.96,119.56,97.17
BEGIN DESCRIPTION:
Dodson Cross Section
END DESCRIPTION:
XS GIS Cut Line= 4
 3082771.499035913948095.3001233 3082799.304713713947715.7526203
 3082863.2577728 13947379.303918 3082544.882761213946824.5806444
#Sta/Elev= 30
       0  125.13  42.186  124.65  63.456  125.08 103.853     123 269.097  117.42
 270.822   116.6 277.893  116.35 330.926  100.85 334.461  101.85 349.664  108.35
 356.735  108.35 363.099  111.35 383.959   113.1 398.101  113.45  416.62  114.79
 471.619  116.96 489.763  116.72 502.993  115.82 524.122  116.77 566.739   117.1
 648.643  116.36 673.102  117.48 685.335  116.58 715.889  118.47 737.201  118.17
 770.937  118.79 801.124  120.22 843.741   120.7 865.046  120.27 963.525  121.87
#Mann= 3 ,-1 , 0
       0     .08       0 277.893    .035       0 398.101      .1       0
#XS Ineff= 2 , 0
       0 281.428     120 400.576       0     120
Permanent Ineff=
       F       F
Bank Sta=277.893,398.101
XS Rating Curve= 0
Skew Angle= 45
Exp/Cntr=.5,.3

Type RM Length L Ch R = 3 ,15443   ,,,
BEGIN DESCRIPTION:
NEW ELLA ROAD BRIDGE
END DESCRIPTION:
Bridge Culvert--1,0,-1,-1, 0
Deck Dist Width WeirC Skew NumUp NumDn MinLoCord MaxHiCord MaxSubmerge Is_Ogee
20,70,2.6,45, 6, 6, , , .95, 0, 0,0,,
  11.314 270.815 270.822 400.576 400.583 789.838
  121.85  120.85  120.85  120.35  120.35  118.85
     100     100  115.35  114.85     100     100
  40.305 299.806 299.813 429.567 429.574  818.83
  121.85  120.85  120.85  120.35  120.35  118.85
     100     100  115.35  114.85     100     100
Pier Skew, UpSta & Num, DnSta & Num=  ,349.077, 4 ,378.069, 4 , 3 , 3 , 0 ,,
    1.33    1.33       3       3
   39.35  111.35  111.35  114.85
    1.33    1.33       3       3
   39.35  111.35  111.35  114.85
BR Coef=-1 , 1 , 1 ,1.25, 0 ,,,.8,0,2,0,
WSPro=,,,, 1 ,,,, 0 ,,,, 0 ,,,,-1 ,-1 ,-1 , 0 , 0 , 0 , 0 , 0
BC Design=,, 0 ,, 0 ,,,,,,
BC HTab HWMax=125.34

Type RM Length L Ch R = 1 ,15390   ,119.64,141.33,160.6
BEGIN DESCRIPTION:
Dodson Cross Section
END DESCRIPTION:
XS GIS Cut Line= 6
 3082833.789197413948081.5081027 3082843.953053813947859.9360318
 3082868.3463094 13947632.265647 3082923.231134313947408.6608048
 3082974.050416613947266.3668143 3082793.133771513946796.7966456
#Sta/Elev= 30
       0  125.19  64.205  124.71  166.17  120.99  255.69  118.61  287.75  116.76
 306.884  116.35 313.955  114.35     341  100.85   388.5  100.85  412.95   113.1
 427.092  113.45 434.164   113.6 440.061  114.89 472.757  116.08 503.213   115.1
 544.995  117.13  577.89   116.8 596.445  117.42 607.808  116.93 619.178  114.57
 630.541  113.43  647.13  112.88 676.008  107.62 698.742  113.65 710.105  115.98
 721.475  115.63 749.583  117.89 789.676  118.64 846.506  121.52 944.263  121.92
#Mann= 3 ,-1 , 0
       0     .08       0 306.884    .035       0 427.092      .1       0
#XS Ineff= 2 , 0
       0  306.88     120     441       0     120
Permanent Ineff=
       F       F
#Block Obstruct= 1 ,-1
     600     740  116.93
Bank Sta=306.884,427.092
XS Rating Curve= 0
Skew Angle= 45
Exp/Cntr=.5,.3

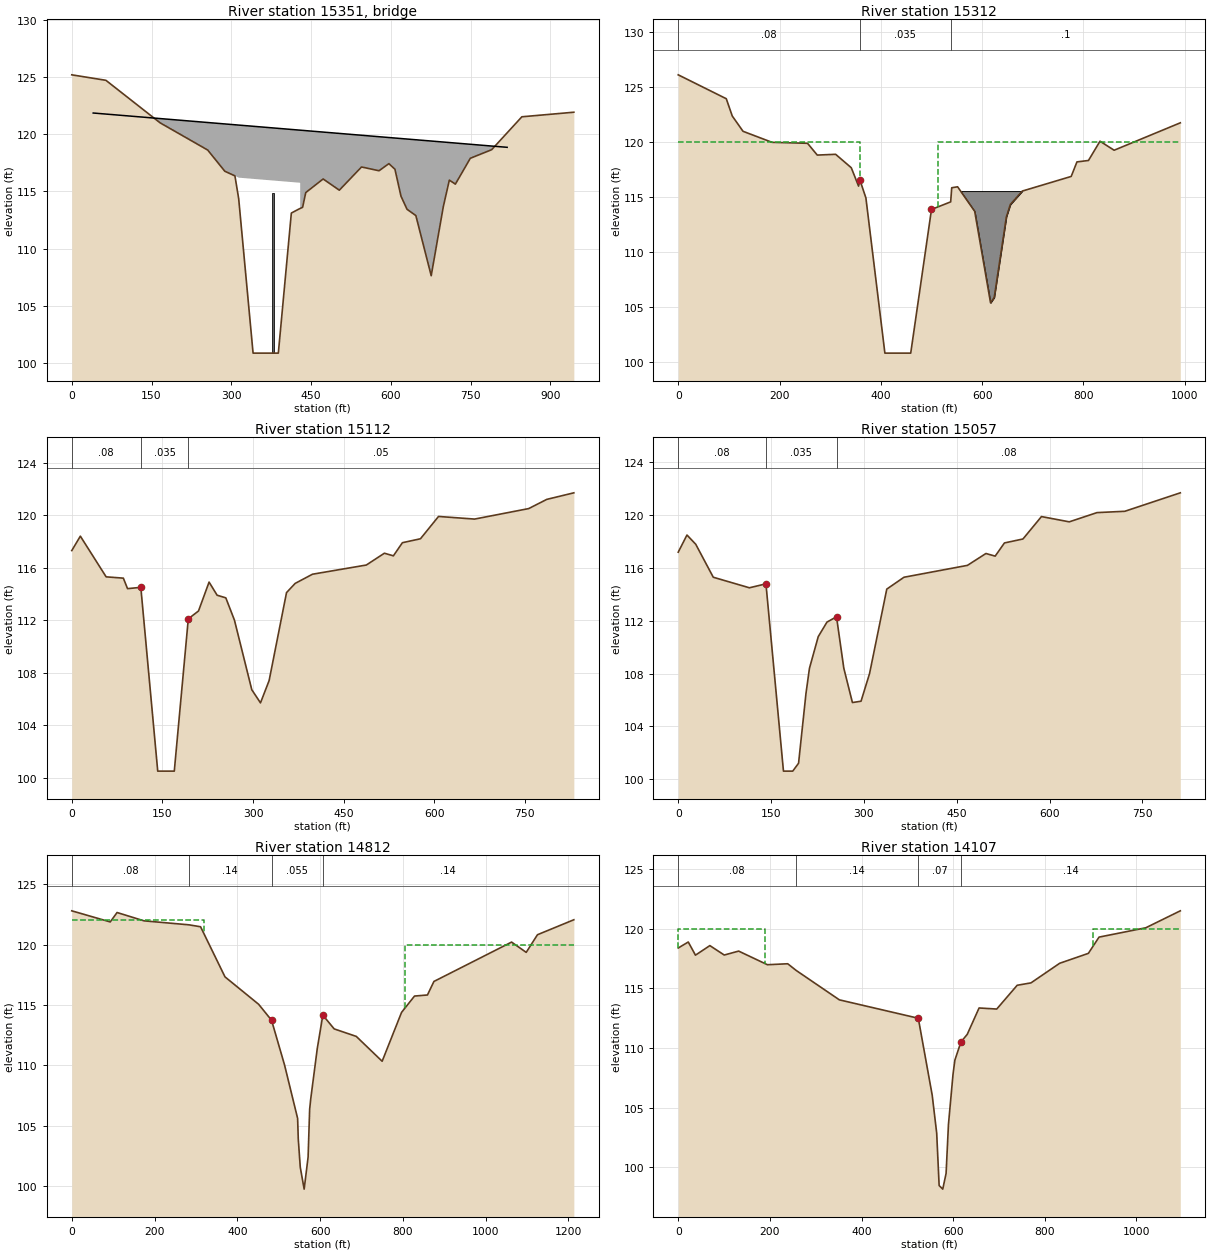
Type RM Length L Ch R = 3 ,15351   ,,,
BEGIN DESCRIPTION:
PROPOSED ELLA ROAD NORTHBOUND BRIDGE
END DESCRIPTION:
Bridge Culvert--1,0,-1,-1, 0
Deck Dist Width WeirC Skew NumUp NumDn MinLoCord MaxHiCord MaxSubmerge Is_Ogee
20,70,2.6,45, 6, 6, , , .95, 0, 0,0,,
   40.31  299.81  299.81  429.57  429.57  818.83
  121.85  120.85  120.85  120.35  120.35  118.85
     100     100  116.25  115.75     100     100
  113.59     370  370.25     500  500.25  892.12
  121.85  120.85  120.85  120.35  120.35  118.85
     100     100  116.25  115.75     100     100
Pier Skew, UpSta & Num, DnSta & Num=  ,377.949, 4 ,436.851, 4 , 3 , 3 , 0 ,,
    1.33    1.33       3       3
   39.35  111.35  111.35  114.85
    1.33    1.33       3       3
   39.35  111.35  111.35  114.85
BR Coef=-1 , 0 , 0 ,1.25, 0 ,,,.8,0,2,0,
WSPro=,,,, 1 ,,,, 0 ,,,, 0 ,,,,-1 ,-1 ,-1 , 0 , 0 , 0 , 0 , 0
BC Design=,, 0 ,, 0 ,,,,,,
BC HTab HWMax=125.23

Type RM Length L Ch R = 1 ,15312   ,250,196.7,1
BEGIN DESCRIPTION:
Dodson Cross Section
END DESCRIPTION:
XS GIS Cut Line= 6
  3082907.84671213948081.3777353 3082930.468462513947704.3485697
 3082978.225490213947455.5093204 3083025.982517813947322.2923485
 3083126.523628713947136.2912935 3082975.7119625 13946746.694489
#Sta/Elev= 30
       0  126.13  94.851  123.96 106.667  122.39 127.916     121 185.071     120
 255.244  119.91 274.499  118.84 310.745  118.91 341.639  117.69 356.049  116.02
 358.503   116.6   370.5  114.95     408  100.85     459  100.85     500   113.9
 537.868  114.59 539.926  115.87 551.536  115.96 585.301  113.73 616.604  105.42
 623.873  105.91 647.986  113.26 655.735  114.35 679.219  115.57 775.809   116.9
 787.187  118.22 809.927  118.35 832.675   120.1 860.577  119.28 991.229  121.77
#Mann= 3 ,-1 , 0
       0     .08       0 358.503    .035       0 537.868      .1       0
#XS Ineff= 2 , 0
       0     358     120     512       0     120
Permanent Ineff=
       F       F
#Block Obstruct= 1 ,-1
 551.543  679.53  115.57
Bank Sta=358.503,500
XS Rating Curve= 0
Skew Angle= 45
Exp/Cntr=.5,.3

Type RM Length L Ch R = 1 ,15112   ,43,51,1
BEGIN DESCRIPTION:
From BKI survey
END DESCRIPTION:
XS GIS Cut Line= 6
     3083158.581     13947487.87     3083131.103     13947407.05
     3083042.803     13947305.12     3083038.862     13947300.57
     3083127.623     13947136.36     3082976.645     13946746.33
#Sta/Elev= 30
       0   117.3    14.2   118.4    56.9   115.3    85.4   115.2    92.3   114.4
   114.3   114.5   142.3   100.5   169.7   100.5   192.9   112.1   209.8   112.7
   227.3   114.9   240.6   113.9     255   113.7   269.3     112     298   106.7
   312.4   105.7   326.7   107.4   355.5   114.1   369.8   114.8   398.5   115.5
   487.6   116.2   517.5   117.1   532.4   116.9   547.3   117.9   577.2   118.2
   607.1   119.9   666.8   119.7   756.4   120.5   786.3   121.2   831.1   121.7
#Mann= 3 , 0 , 0
       0     .08       0   114.3    .035       0   192.9     .05       0
#Block Obstruct= 2 , 0
       0                   227.3       0   114.9
Bank Sta=114.3,192.9
XS Rating Curve= 0
Exp/Cntr=.3,.1

Type RM Length L Ch R = 1 ,15057   ,159.03,245.4,329.57
XS GIS Cut Line= 6
     3083193.474     13947469.15     3083150.581     13947349.27
      3083072.02     13947268.11     3083062.731     13947258.51
     3083128.722     13947136.43     3082977.577     13946745.97
#Sta/Elev= 30
       0   117.2    14.1   118.5    28.3   117.8    56.6   115.3     115   114.5
   141.7   114.8     170   100.6     185   100.6   194.4   101.2   206.4   106.5
     212   108.4   226.2   110.8   240.3   111.9   255.7   112.3   267.5   108.4
   281.4   105.8   295.3   105.9   309.1     108   336.9   114.4   364.7   115.3
   467.2   116.2   497.1   117.1     512   116.9     527   117.9   556.9   118.2
   586.8   119.9   631.7   119.5   676.5   120.2   721.4   120.3   811.1   121.7
#Mann= 3 , 0 , 0
       0     .08       0   141.7    .035       0   255.7     .08       0
#Block Obstruct= 2 , 0
       0                   255.7       0   112.3
Bank Sta=141.7,255.7
XS Rating Curve= 0
Exp/Cntr=.3,.1

Type RM Length L Ch R = 1 ,14812   ,570.84,704.53,388.19
BEGIN DESCRIPTION:
Dodson Cross Section
END DESCRIPTION:
XS GIS Cut Line= 4
 3083423.119905613947870.2414025  3083287.38940613947390.1575983
 3083330.1193781 13947261.967682  3083166.74007313946706.4780447
#Sta/Elev= 30
       0  122.79   92.95  121.87  109.43  122.65  174.62  121.96  283.28  121.63
  311.18  121.47  370.21  117.32  451.47  115.05  482.65  113.73  514.04  110.03
  545.66   105.6  547.27  103.88  552.09  101.55  561.47   99.74  570.98  102.39
  574.74  106.35  577.28  107.19  593.09  111.37  606.56  114.15  634.03  113.01
  687.36  112.39   749.9  110.33  796.81  114.38  828.08  115.73  859.35  115.82
  874.98  116.94 1062.61   120.2 1097.98  119.35 1125.15  120.81 1213.04  122.05
#Mann= 4 ,-1 , 0
       0     .08       0  283.28     .14       0  482.65    .055       0
  606.56     .14       0
#XS Ineff= 2 , 0
       0     320     122     805       0     120
Permanent Ineff=
       F       F
Bank Sta=482.65,606.56
XS Rating Curve= 0
Exp/Cntr=.3,.1

Type RM Length L Ch R = 1 ,14107   ,408.17,516.36,488.76
BEGIN DESCRIPTION:
Dodson Cross Section
END DESCRIPTION:
XS GIS Cut Line= 4
 3083767.473210213947681.7268197 3083616.661543913947194.1024322
 3083639.283293913947040.7772382 3083516.120433213946628.5586838
#Sta/Elev= 30
       0  118.37    21.9  118.87   37.61  117.77   69.01  118.57  100.41  117.78
  131.81  118.11  194.62  116.97  238.92  117.05  257.42  116.49  351.63  114.03
  523.86  112.49  554.18  106.06  564.01  102.88  569.35   98.49  577.23   98.19
  584.51   99.51  589.66   103.6  599.67  107.81  603.65  108.98  616.86   110.5
  630.63  111.14   656.5  113.35  695.02  113.26  739.67  115.25  769.74  115.45
  832.36  117.09  894.98  117.92  918.28  119.28 1020.23  120.06 1095.62  121.48
#Mann= 4 ,-1 , 0
       0     .08       0  257.42     .14       0  523.86     .07       0
  616.86     .14       0
#XS Ineff= 2 , 0
       0     190     120     905       0     120
Permanent Ineff=
       F       F
Bank Sta=523.86,616.86
XS Rating Curve= 0
Exp/Cntr=.3,.1