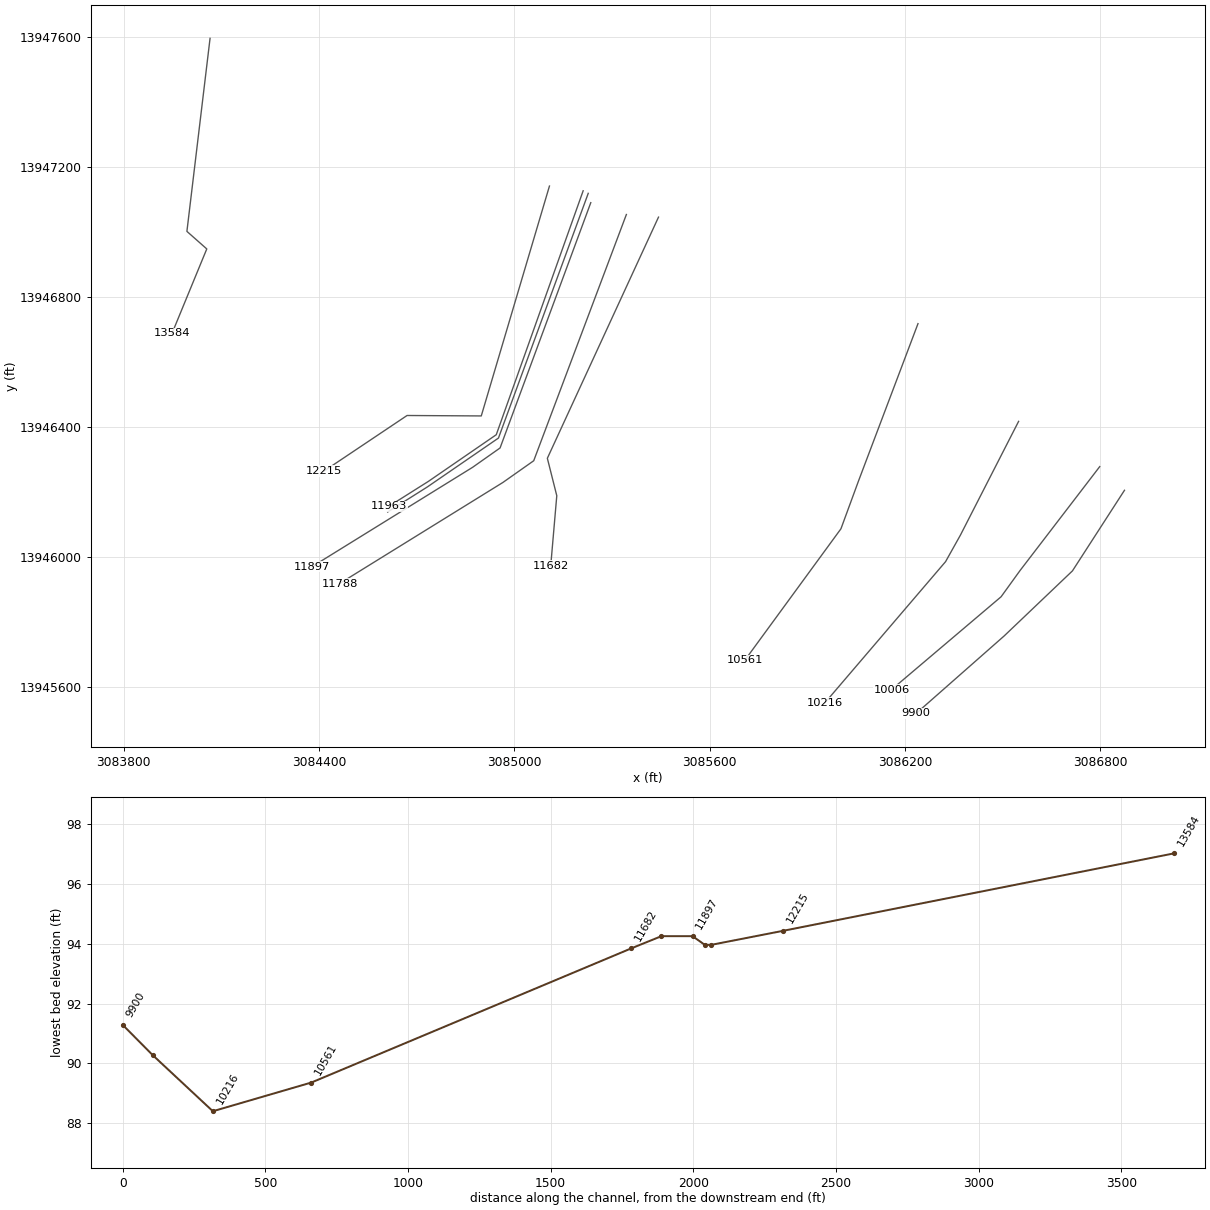
HEC-RAS study K124-00-00.prj: K124-00-00

--- K124-00-00.g05 (geometry) --- (continued)

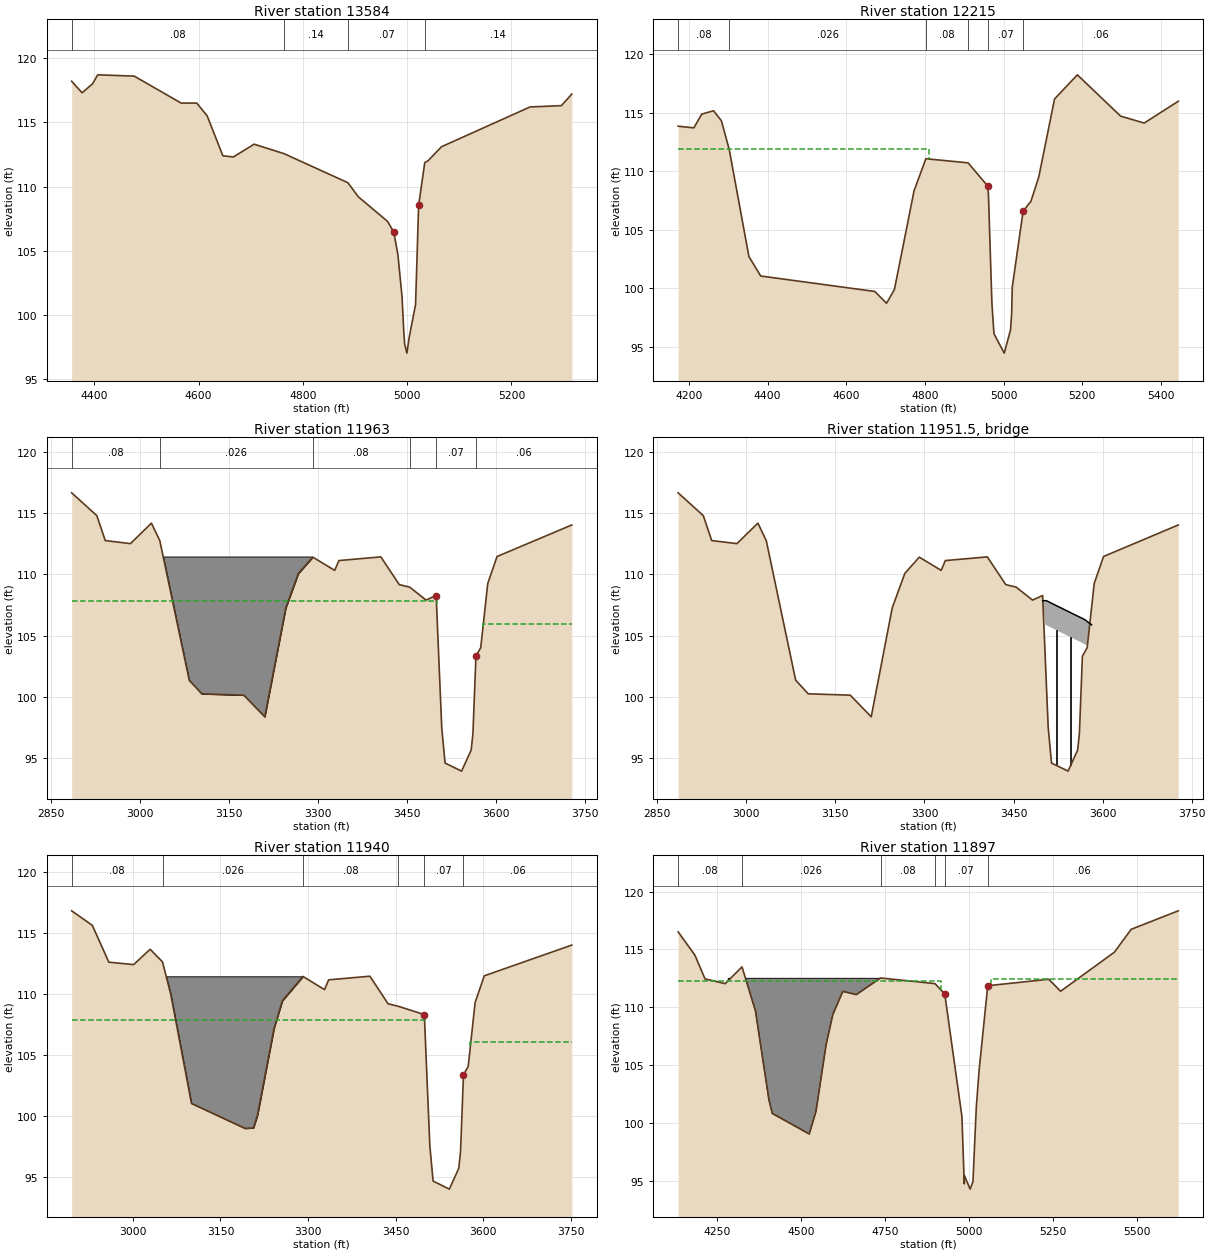
Type RM Length L Ch R = 1 ,13584   ,1413.3,1369,1107.1
BEGIN DESCRIPTION:
Cross Section K124-00-00-X07
END DESCRIPTION:
XS GIS Cut Line= 4
      3084065.11      13947596.1      3083993.98     13947002.51
      3084055.03     13946948.51       3083948.5      13946689.5
#Sta/Elev= 30
  4356.4   118.2  4376.4   117.3  4396.4     118  4406.4   118.7  4476.4   118.6
  4566.4   116.5  4596.4   116.5  4616.4   115.5  4646.4   112.4  4666.4   112.3
  4706.4   113.3  4763.9  112.56  4886.3   110.3  4906.4   109.2  4962.3  107.29
  4974.4  106.45  4982.3  104.67  4990.1  101.45  4993.5   98.69  4995.2   97.74
  4999.5   97.03  5003.8   98.24  5016.1  100.82    5022  108.54  5033.7  111.86
  5040.1  112.01  5065.8   113.1  5235.8   116.2  5295.8   116.3  5315.8   117.2
#Mann= 4 ,-1 , 0
  4356.4     .08       0  4763.9     .14       0  4886.3     .07       0
  5033.7     .14       0
Bank Sta=4974.4,5022
XS Rating Curve= 0
Exp/Cntr=.3,.1

Type RM Length L Ch R = 1 ,12215   ,167.9,252,259.6
BEGIN DESCRIPTION:
PIPE_S5-2_US-XS 4
END DESCRIPTION:
XS GIS Cut Line= 4
      3085107.95      13947141.9      3084898.45     13946435.02
      3084670.43     13946436.36      3084415.75     13946265.67
#Sta/Elev= 30
  4172.4  113.83  4212.4  113.69  4232.4  114.86  4262.4  115.15  4282.4   114.3
  4302.4  111.83  4352.4  102.69  4382.4  101.03  4672.4   99.71  4702.4    98.7
  4722.4   99.87  4772.4  108.31  4802.4  111.05  4909.7   110.7  4959.7  108.72
 4961.56     108 4970.37   98.71  4975.6    96.1 5001.71   94.44 5017.66   96.41
  5020.6   97.84 5022.14  100.08  5049.7  106.56  5069.7  107.42  5089.7  109.51
  5129.7  116.16  5187.7  118.22  5297.7  114.69  5357.7   114.1  5444.3  115.96
#Mann= 6 ,-1 , 0
  4172.4     .08       0  4302.4    .026       0  4802.4     .08       0
  4909.7     .06       0  4959.7     .07       0  5049.7     .06       0
#XS Ineff= 2 , 0
         4810.33  111.88
Permanent Ineff=
       F       F
#Block Obstruct= 2 , 0
         4806.93  110.99
Bank Sta=4959.7,5049.7
XS Rating Curve= 0
Exp/Cntr=.5,.3

Type RM Length L Ch R = 1 ,11963   ,18.8,23,19.6
BEGIN DESCRIPTION:
Upstream Section of Bridge/Culvert/Weir
END DESCRIPTION:
XS GIS Cut Line= 4
       3085211.5      13947127.3      3084944.54     13946377.25
      3084736.03      13946233.8      3084614.56     13946157.13
#Sta/Elev= 30
2885.066  116.652927.493  114.792941.635  112.762984.061  112.513019.417  114.18
3033.559  112.753083.056  101.38 3104.27  100.27 3174.98  100.163210.335    98.4
3245.691  107.273266.904  110.083291.229  111.41 3328.14  110.333335.211  111.13
3405.851  111.433436.942  109.173454.619  108.963481.985  107.913499.026  108.28
 3508.43   97.543514.016   94.633541.877   93.973557.999   95.683560.969   97.03
 3566.06  103.343574.121  104.033585.929  109.263601.627  111.463727.513  114.03
#Mann= 6 ,-1 , 0
2885.066     .08       03033.559    .026       03291.229     .08       0
3454.619     .06       03499.026     .07       0 3566.06     .06       0
#XS Ineff= 2 , 0
       03499.613   107.8 3577.96       0     106
Permanent Ineff=
       F       F
#Block Obstruct= 1 ,-1
3028.2983289.864  111.46
Bank Sta=3499.026,3566.06
XS Rating Curve= 0
Skew Angle= 45
Exp/Cntr=.5,.3

Type RM Length L Ch R = 3 ,11951.5 ,,,
BEGIN DESCRIPTION:
11958 PL1_K124-00-00-S5-2
END DESCRIPTION:
Bridge Culvert--1,0,-1,-1, 0
Deck Dist Width WeirC Skew NumUp NumDn MinLoCord MaxHiCord MaxSubmerge Is_Ogee
10,2,2.6,45, 18, 18, , , .95, 0, ,,,
3499.0263503.5733505.3193505.3973505.461 3508.433511.6833514.0163522.0073541.877
3546.3313557.9993559.4133560.9693562.524 3566.063570.2253581.496
  107.86  107.86  107.86  107.86  107.86  107.79  107.71  107.65  107.46  106.99
  106.88   106.6  106.57  106.53   106.5  106.41  106.31  105.89
  105.86  105.86  105.86  105.86  105.86  105.79  105.71  105.65  105.46  104.99
  104.88   104.6  104.57  104.53   104.5  104.41  104.31  103.89
3499.0263503.5733505.3193505.3973505.461 3508.433511.6833514.0163522.0073541.877
3546.3313557.9993559.4133560.9693562.524 3566.063570.2253581.496
  107.86  107.86  107.86  107.86  107.86  107.79  107.71  107.65  107.46  106.99
  106.88   106.6  106.57  106.53   106.5  106.41  106.31  105.89
  105.86  105.86  105.86  105.86  105.86  105.79  105.71  105.65  105.46  104.99
  104.88   104.6  104.57  104.53   104.5  104.41  104.31  103.89
Pier Skew, UpSta & Num, DnSta & Num=  ,3522.028, 2 ,3522.028, 2 , 0 , 0 , 0 ,,
     1.5     1.5
   93.23  106.47
     1.5     1.5
   93.23  106.47
Pier Skew, UpSta & Num, DnSta & Num=  ,3546.353, 2 ,3546.353, 2 , 0 , 0 , 0 ,,
     1.5     1.5
   91.36  105.89
     1.5     1.5
   91.36  105.89
BR Coef= 1 , 1 , 1 ,1.25, 0 ,,,.8,0,2,0,
WSPro=,,,, 1 ,,,, 0 ,,,, 0 ,,,,-1 ,-1 ,-1 , 0 , 0 , 0 , 0 , 0
BC Design=,, 0 ,, 0 ,,,,,,
BC HTab HWMax=116.65

Type RM Length L Ch R = 1 ,11940   ,29.2,43,43.2
BEGIN DESCRIPTION:
Downstream Section of Bridge/Culvert/Weir
END DESCRIPTION:
XS GIS Cut Line= 4
      3085227.13      13947119.5      3084951.29       13946367.
      3084732.65     13946216.58      3084610.84      13946139.7
#Sta/Elev= 30
2895.249  116.792930.604   115.62958.888  112.583001.315  112.383029.599  113.64
3050.812   112.63064.954  109.93 3100.31     1013192.233   98.953206.376   98.99
3213.447  100.053241.731  107.163255.873  109.413291.229  111.41 3328.14  110.33
3335.211  111.133405.851  111.433436.942  109.173454.619  108.963499.026  108.28
 3508.43   97.543514.016   94.633541.877   93.973557.999   95.683560.969   97.03
 3566.06  103.343574.121  104.033585.929  109.263601.627  111.463751.484  113.98
#Mann= 6 ,-1 , 0
2895.249     .08       03050.812    .026       03291.229     .08       0
3454.619     .06       03499.026     .07       0 3566.06     .06       0
#XS Ineff= 2 , 0
       03499.613   107.8 3577.96       0     106
Permanent Ineff=
       F       F
#Block Obstruct= 1 ,-1
3053.7823291.207  111.42
Bank Sta=3499.026,3566.06
XS Rating Curve= 0
Skew Angle= 45
Exp/Cntr=.5,.3

Type RM Length L Ch R = 1 ,11897   ,108,109,124.6
BEGIN DESCRIPTION:
Upstream Section of Bridge/Culvert/Weir
END DESCRIPTION:
XS GIS Cut Line= 4
      3085234.94      13947090.8      3084956.22     13946336.54
       3084871.7     13946276.95      3084378.57      13945971.5
#Sta/Elev= 30
  4135.1  116.52  4185.1   114.5  4215.1  112.45  4275.1  112.04  4325.1  113.49
  4365.1  109.68  4405.1  101.99  4415.1  100.81  4525.1   99.03  4545.1  100.98
  4575.1  106.73  4595.1  109.36  4625.1  111.37  4665.1  111.09  4737.2  112.53
  4899.2  112.04  4928.2  111.14  4979.2  100.55  4986.2   94.72  4986.6   95.44
  5003.5   94.26  5011.9   94.89    5022  101.37  5030.3  104.53    5056  111.86
  5237.6  112.42  5272.7  111.38  5432.7  114.76  5482.7  116.74  5622.7  118.34
#Mann= 6 ,-1 , 0
  4135.1     .08       0  4325.1    .026       0  4737.2     .08       0
  4899.2     .06       0  4928.2     .07       0    5056     .06       0
#XS Ineff= 2 , 0
       0  4918.2   112.3  5065.8       0  112.43
Permanent Ineff=
       F       F
#Block Obstruct= 1 ,-1
 4284.06 4736.96   112.5
Bank Sta=4928.2,5056
XS Rating Curve= 0
Exp/Cntr=.5,.3

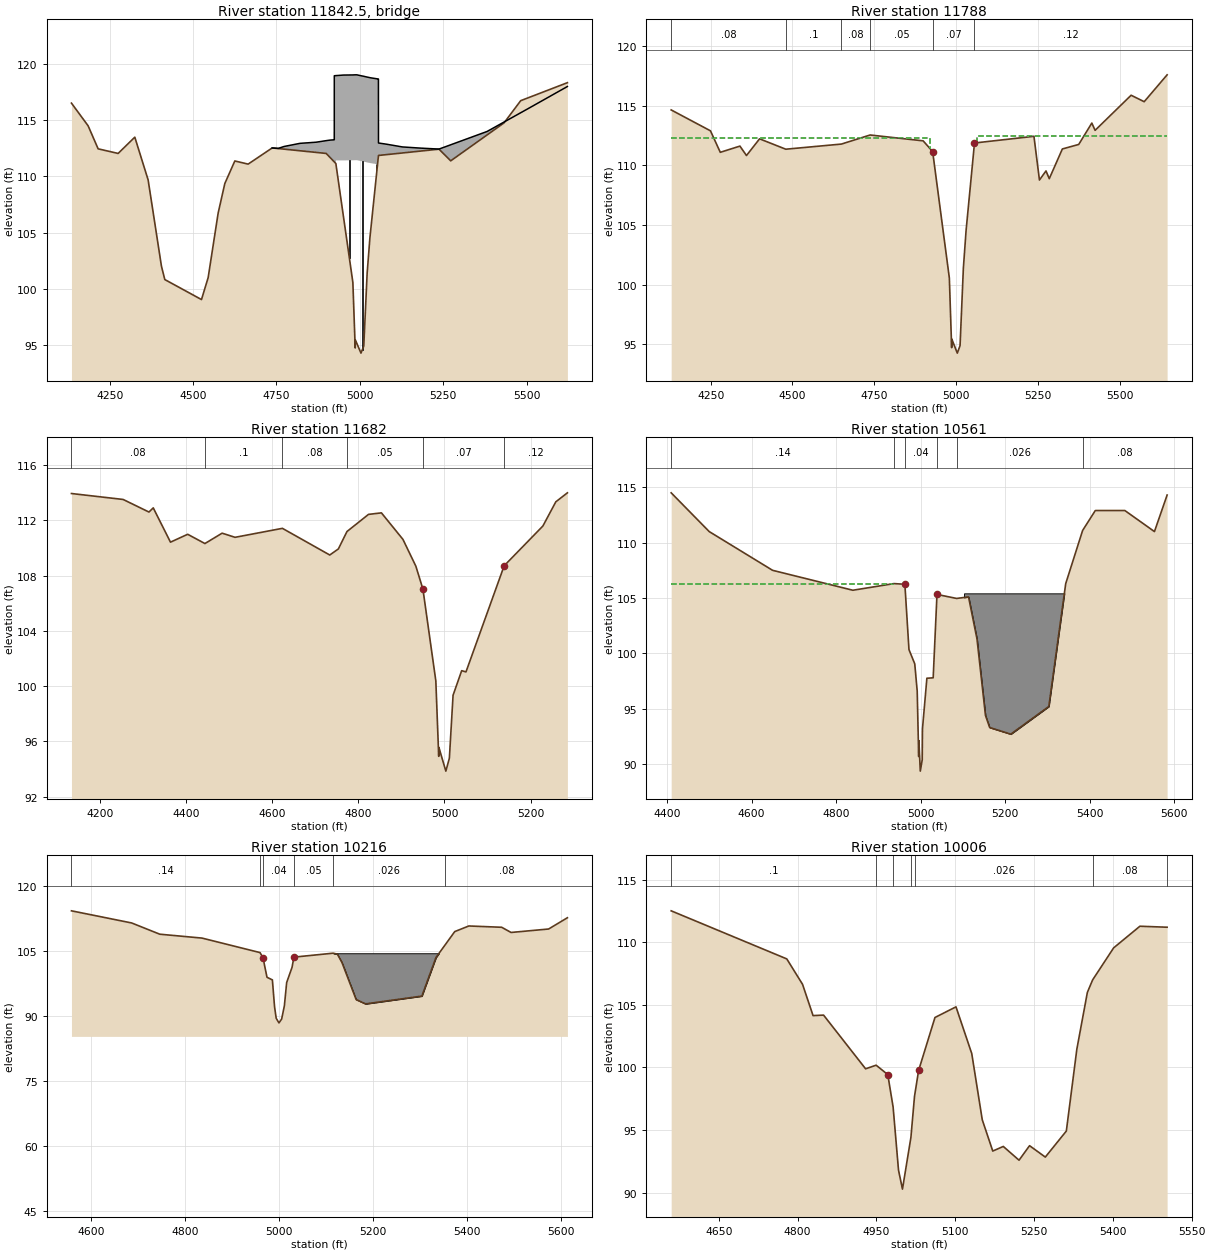
Type RM Length L Ch R = 3 ,11842.5 ,,,
BEGIN DESCRIPTION:
11893 LOUETTA ROAD
Structure ID: K124-00-00-S5
END DESCRIPTION:
Bridge Culvert--1,0,-1,-1, 0
Deck Dist Width WeirC Skew NumUp NumDn MinLoCord MaxHiCord MaxSubmerge Is_Ogee
10,79,2.6,0, 40, 40, , , .95, 0, ,,,
  4737.2  4755.2  4772.8  4820.6  4868.7  4899.2  4911.2 4921.11 4921.23  4921.3
 4923.39  4923.5 4923.61  4928.2  4951.3  4979.2  4986.2  4986.6  4991.2  5003.5
  5011.9  5013.4    5022  5030.3  5031.4 5052.85 5052.97 5053.08 5055.69  5055.8
  5055.9 5056.01  5078.8  5082.8  5127.8  5184.7  5237.6    5382    5503  5622.7
  112.53  112.49  112.66  112.94  113.04  113.18  113.23  113.25  113.25  113.25
  113.26  118.96  118.96  118.97  119.02  119.03  119.04  119.04  119.04  118.96
  118.91   118.9  118.84  118.79  118.78  118.68  118.68  118.68  118.67  118.67
  118.67  112.97  112.87  112.85  112.62  112.51  112.43     114     116     118
                                                                                
                          111.42  111.42  111.43  111.44  111.44  111.44  111.36
  111.31   111.3  111.24  111.19  111.18  111.08  111.08
                                                                                
  4737.2  4755.2  4772.8  4820.6  4868.7  4899.2  4911.2 4921.11 4921.23  4921.3
 4923.39  4923.5 4923.61  4928.2  4951.3  4979.2  4986.2  4986.6  4991.2  5003.5
  5011.9  5013.4    5022  5030.3  5031.4 5052.85 5052.97 5053.08 5055.69  5055.8
  5055.9 5056.01  5078.8  5082.8  5127.8  5184.7  5237.6    5382    5503  5644.4
  112.53  112.49  112.66  112.94  113.04  113.18  113.23  113.25  113.25  113.25
  113.26  118.96  118.96  118.97  119.02  119.03  119.04  119.04  119.04  118.96
  118.91   118.9  118.84  118.79  118.78  118.68  118.68  118.68  118.67  118.67
  118.67  112.97  112.87  112.85  112.62  112.51  112.43     114     116  117.57
                                                                                
                          111.42  111.42  111.43  111.44  111.44  111.44  111.36
  111.31   111.3  111.24  111.19  111.18  111.08  111.08
                                                                                
Pier Skew, UpSta & Num, DnSta & Num=  ,4968.7, 2 ,4968.7, 2 , 0 , 0 , 0 ,,
     1.3     1.3
  101.59  112.43
     1.3     1.3
  101.65  112.49
Pier Skew, UpSta & Num, DnSta & Num=  ,5007.5, 2 ,5007.5, 2 , 0 , 0 , 0 ,,
     1.3     1.3
   93.51  112.34
     1.3     1.3
   93.57   112.4
Pier Skew, UpSta & Num, DnSta & Num=  ,5049.3, 2 ,5049.3, 2 , 0 , 0 , 0 ,,
     1.3     1.3
   108.8   112.1
     1.3     1.3
  108.86  112.16
BR Coef= 1 , 1 , 1 ,1.25, 0 ,,,.8,0,2,0,
WSPro=,,,, 1 ,,,, 0 ,,,, 0 ,,,,-1 ,-1 ,-1 , 0 , 0 , 0 , 0 , 0
BC Design=,, 0 ,, 0 ,,,,,,
BC HTab HWMax=118.34

Type RM Length L Ch R = 1 ,11788   ,42.7,106,179.9
BEGIN DESCRIPTION:
Downstream Section of Bridge/Culvert/Weir
END DESCRIPTION:
XS GIS Cut Line= 4
      3085344.31      13947054.4      3085059.61     13946297.23
      3084964.83     13946230.41       3084463.2      13945919.7
#Sta/Elev= 30
  4129.5  114.63  4249.5  112.88  4279.5  111.08  4339.5   111.6  4359.5  110.81
  4399.5  112.21  4479.5  111.34  4649.5  111.77  4737.2  112.53  4899.2  112.04
  4928.2  111.14  4979.2  100.55  4986.2   94.72  4986.6   95.44  5003.5   94.26
  5011.9   94.89    5022  101.37  5030.3  104.53    5056  111.86  5237.6  112.42
  5254.4  108.76  5274.4  109.52  5284.4  108.87  5324.4  111.36  5374.4  111.74
  5414.4  113.53  5424.4  112.92  5534.4  115.86  5574.4  115.32  5644.4  117.57
#Mann= 6 ,-1 , 0
  4129.5     .08       0  4479.5      .1       0  4649.5     .08       0
  4737.2     .05       0  4928.2     .07       0    5056     .12       0
#XS Ineff= 2 , 0
       0 4921.53   112.3 5062.47       0  112.43
Permanent Ineff=
       F       F
Bank Sta=4928.2,5056
XS Rating Curve= 0
Exp/Cntr=.5,.3

Type RM Length L Ch R = 1 ,11682   ,1103,1121,1033.4
BEGIN DESCRIPTION:
S5_LOUETTA-DS-XS 1
END DESCRIPTION:
XS GIS Cut Line= 4
      3085443.02      13947046.3      3085101.49     13946304.78
      3085130.47     13946189.67       3085111.8     13945973.65
#Sta/Elev= 30
  4133.5  113.94  4253.5  113.51  4313.5   112.6  4323.5   112.9  4363.5  110.42
  4403.5  110.99  4443.5  110.32  4483.5  111.07  4513.5  110.77  4623.5  111.42
  4733.5  109.49  4753.5  109.93  4773.5  111.19  4823.5  112.43  4853.5  112.54
  4903.5  110.62  4933.5  108.68  4949.9  107.02 4979.88  100.38 4986.58   94.92
 4986.96   95.57 5003.13   93.85 5011.35   94.79  5019.9   99.34  5039.9  101.12
  5049.9  101.03  5138.6  108.71  5228.6  111.59  5258.6  113.34  5285.5  113.99
#Mann= 6 ,-1 , 0
  4133.5     .08       0  4443.5      .1       0  4623.5     .08       0
  4773.5     .05       0  4949.9     .07       0  5138.6     .12       0
#XS Ineff= 2 , 0
       0    4825   112.4               0
Permanent Ineff=
       F       F
Bank Sta=4949.9,5138.6
XS Rating Curve= 0
Exp/Cntr=.3,.1

Type RM Length L Ch R = 1 ,10561   ,351.8,345,338.7
BEGIN DESCRIPTION:
Cross Section K124-00-00-X06
END DESCRIPTION:
XS GIS Cut Line= 4
      3086240.34      13946718.8      3086057.54     13946234.98
      3086003.63     13946088.04      3085708.62      13945684.2
#Sta/Elev= 30
  4409.5   114.5  4499.5     111  4649.5   107.5  4839.5   105.7  4936.7   106.3
  4962.6  106.24  4972.3  100.34    4986   99.05  4991.8   96.59  4995.3   90.68
  4995.8   92.11  4999.1   89.36  5003.7   90.39  5004.2   93.16  5014.7   97.75
  5029.6   97.79  5038.6  105.32  5085.2  104.96  5113.3   105.1  5133.3   101.3
  5153.3    94.4  5163.3    93.3  5213.3    92.7  5303.3    95.2  5343.3   106.3
  5383.3   111.1  5413.3   112.9  5483.3   112.9  5553.3     111  5583.3   114.3
#Mann= 6 ,-1 , 0
  4409.5     .14       0  4936.7     .05       0  4962.6     .04       0
  5038.6     .05       0  5085.2    .026       0  5383.3     .08       0
#XS Ineff= 2 , 0
       0    4938   106.3               0
Permanent Ineff=
       F       F
#Block Obstruct= 1 ,-1
 5102.67 5344.34  105.42
Bank Sta=4962.6,5038.6
XS Rating Curve= 0
Exp/Cntr=.3,.1

Type RM Length L Ch R = 1 ,10216   ,224.9,210,204
BEGIN DESCRIPTION:
Cross Section K124-00-00-X05A
END DESCRIPTION:
XS GIS Cut Line= 4
      3086549.48      13946418.3      3086370.74     13946068.63
      3086325.02     13945986.88      3085954.76      13945553.4
#Sta/Elev= 30
  4557.7   114.3  4685.8   111.5  4745.8   108.9  4835.8     108  4959.4  104.65
  4965.7  103.45  4974.2   98.95  4985.7   98.34  4990.3   92.13  4993.8   89.48
  4999.7    88.4  5005.4    89.3  5011.2   92.34  5016.1   97.73  5027.6  101.26
  5031.5   103.6  5114.9  104.51  5124.1   104.3  5134.1   102.3  5164.1    93.8
  5184.1    92.8  5304.1    94.6  5334.1   103.5  5354.1   106.5  5374.1   109.5
  5404.1   110.8  5474.1   110.5  5494.1   109.3  5574.1   110.1  5614.1   112.7
#Mann= 6 ,-1 , 0
  4557.7     .14       0  4959.4     .05       0  4965.7     .04       0
  5031.5     .05       0  5114.9    .026       0  5354.1     .08       0
#Block Obstruct= 2 ,-1
    5115    5355   104.5    9000    9001      50
Bank Sta=4965.7,5031.5
XS Rating Curve= 0
Exp/Cntr=.3,.1

Type RM Length L Ch R = 1 ,10006   ,118.3,106,96.5
BEGIN DESCRIPTION:
Weir_S4-1_US-XS 4
END DESCRIPTION:
XS GIS Cut Line= 4
      3086798.74      13946279.2      3086554.12     13945959.91
      3086495.71     13945879.01      3086158.83     13945593.27
#Sta/Elev= 30
  4559.5   112.5  4779.5  108.66  4809.5  106.63  4829.5  104.13  4849.5  104.17
  4929.5   99.88  4949.5  100.17  4971.7   99.42 4981.86   96.82 4992.11   91.79
 4999.64   90.27 5015.71    94.4 5022.56   97.68 5030.39   99.75  5061.5  103.98
  5101.5  104.83  5131.5   101.1  5151.5   95.81  5171.5   93.31  5191.5   93.68
  5221.5   92.58  5241.5   93.74  5271.5   92.83  5311.5   94.91  5331.5  101.45
  5351.5  105.98  5361.5  106.98  5401.5  109.54  5451.5  111.27  5503.3  111.19
#Mann= 7 ,-1 , 0
  4559.5      .1       0  4949.5     .05       0 4981.86     .02       0
 5015.71     .05       0 5022.56    .026       0  5361.5     .08       0
  5503.3     .08       0
#Block Obstruct= 2 , 0
                         5100.71          104.66
Bank Sta=4971.7,5030.39
XS Rating Curve= 0
Exp/Cntr=.7,.5

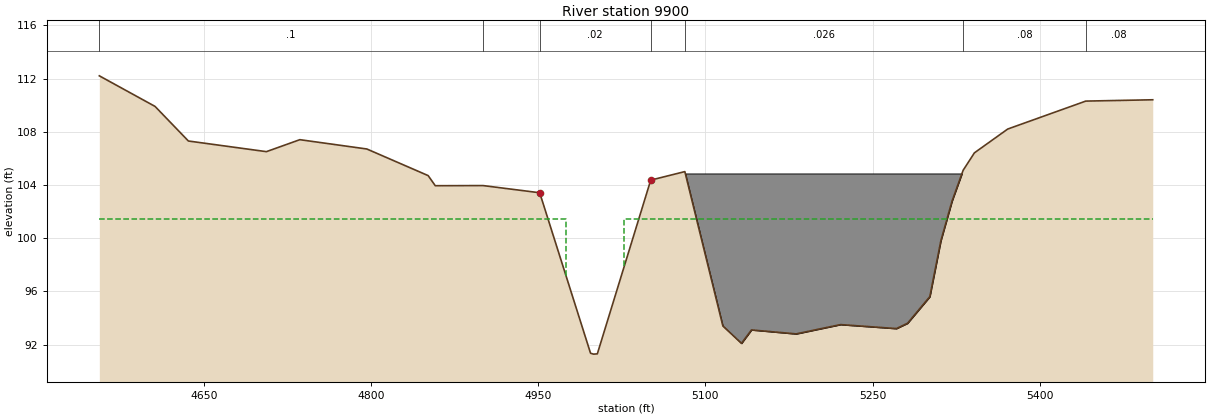
Type RM Length L Ch R = 1 ,9900    ,19.8,20,20.3
BEGIN DESCRIPTION:
Upstream Section of Bridge/Culvert/Weir
END DESCRIPTION:
XS GIS Cut Line= 4
      3086874.78      13946206.4       3086714.9     13945958.55
      3086504.98     13945758.39      3086234.87      13945520.4
#Sta/Elev= 30
  4556.3  112.21  4606.3  109.91  4636.2  107.31  4706.2  106.51  4736.2  107.41
  4796.3  106.71  4851.3  104.71  4857.7  103.95  4900.6  103.96  4951.4  103.42
    4997   91.36  4999.6   91.29  5003.1   91.31    5051  104.37  5081.6  105.01
  5115.7   93.41  5132.4    92.1  5141.4   93.11  5181.4   92.81  5221.3   93.51
  5271.4   93.21  5281.4   93.61  5301.4   95.61  5311.3   99.81  5321.4  102.81
  5331.3  105.11  5341.4  106.42  5371.3  108.21  5441.3  110.31  5501.4  110.41
#Mann= 7 ,-1 , 0
  4556.3      .1       0  4900.6     .05       0  4951.4     .02       0
    5051     .05       0  5081.6    .026       0  5331.3     .08       0
  5441.3     .08       0
#XS Ineff= 2 , 0
       0  4975.2  101.43  5027.2       0  101.42
Permanent Ineff=
       F       F
#Block Obstruct= 1 ,-1
 5079.83 5369.61  104.87
Bank Sta=4951.4,5051
XS Rating Curve= 0
Exp/Cntr=.7,.5