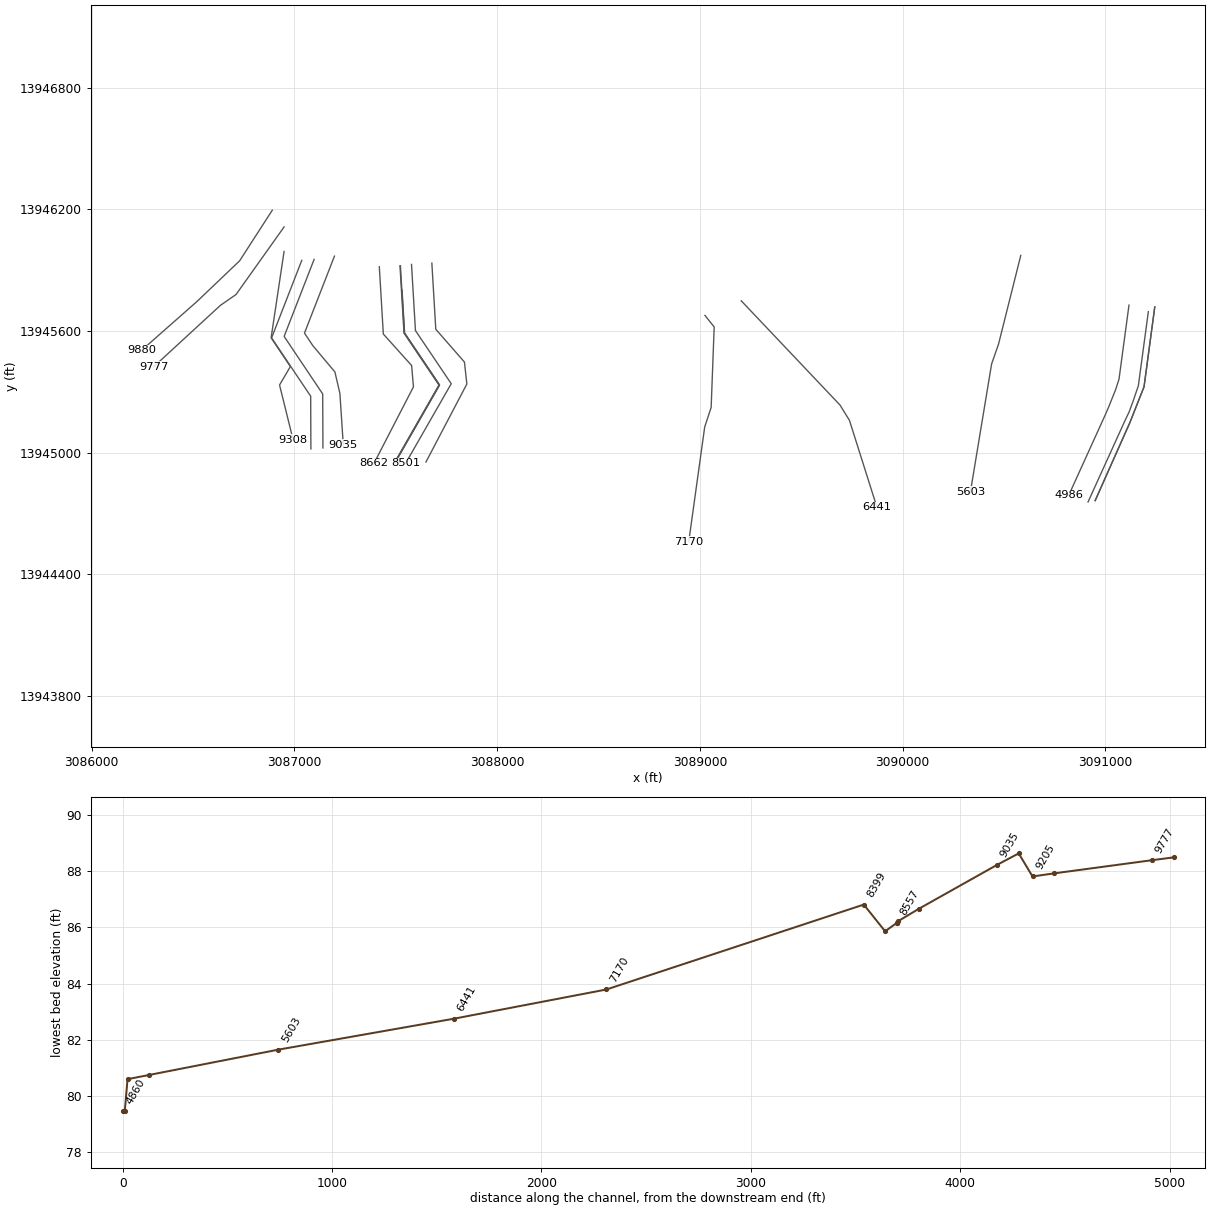
HEC-RAS study K124-00-00.prj: K124-00-00

--- K124-00-00.g05 (geometry) --- (continued)

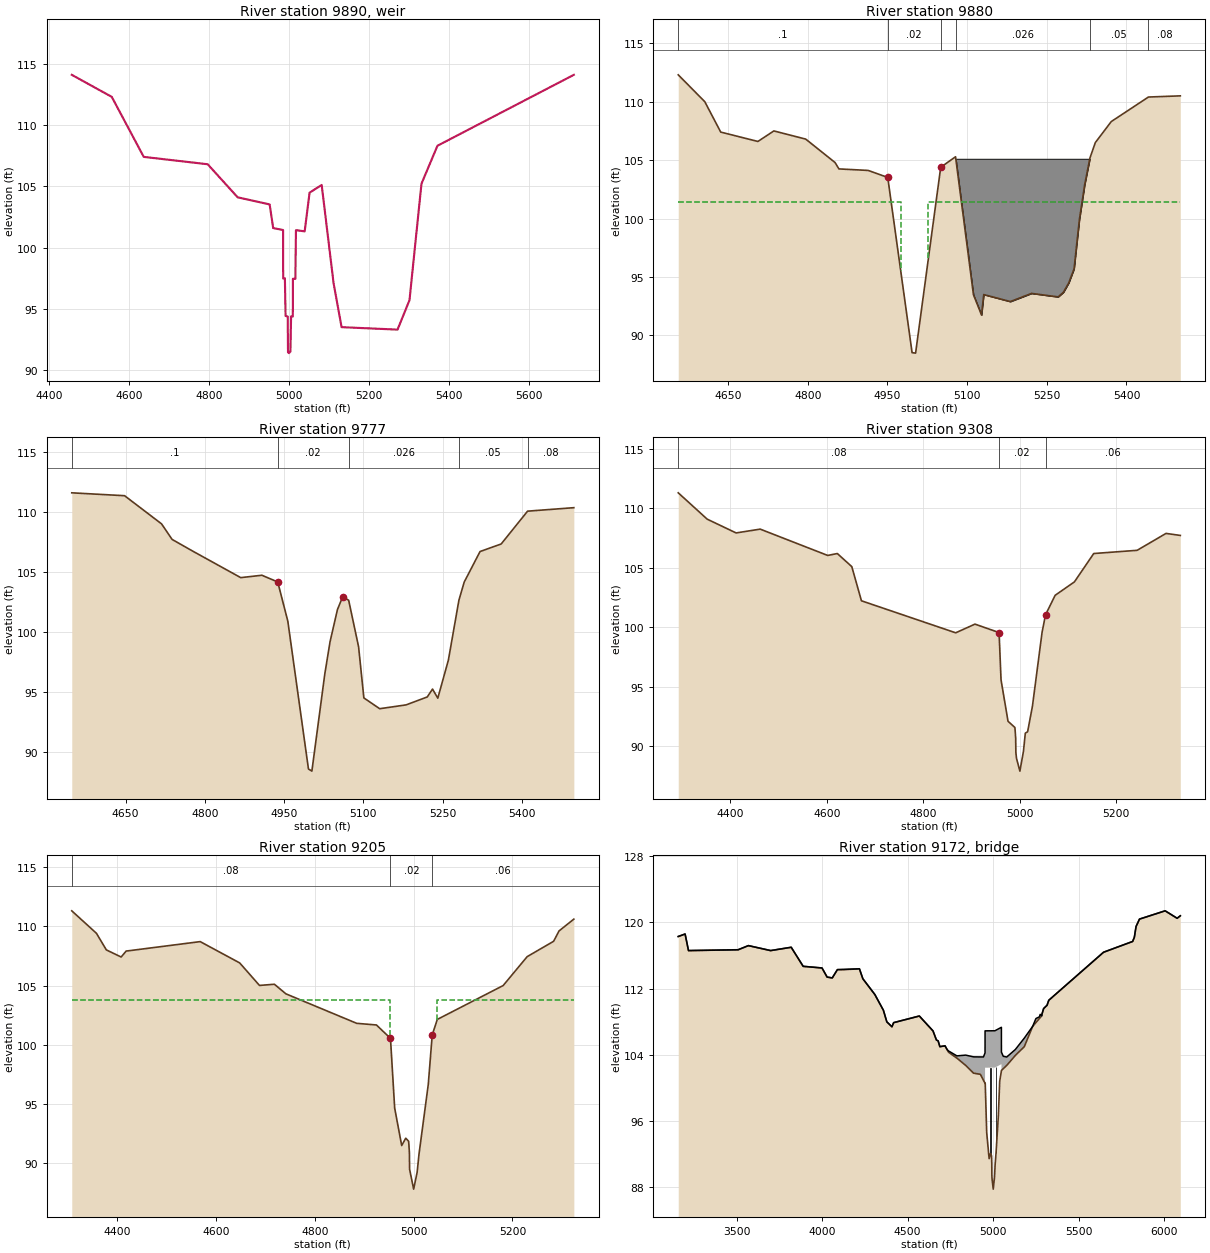
Type RM Length L Ch R = 5 ,9890    ,,,
BEGIN DESCRIPTION:
9884  9887.5  720 FEET US FROM MIRROR LAKE RD.
Structure ID: K124-00-00-S4-1
END DESCRIPTION:
IW Pilot Flow=0
#Inline Weir SE= 30
  4456.2   114.1  4556.3   112.3  4636.3   107.4  4796.3   106.8  4871.3   104.1
  4951.4  103.52  4960.2  101.59    4985  101.43  4985.2   97.47  4989.5    97.5
  4991.2   94.42  4996.6   94.37  4997.3   91.45  4999.6   91.38  5003.4   91.51
    5005   94.38  5009.4   94.37  5009.6   97.45  5015.7   97.44  5017.2  101.42
    5039  101.32  5051.3  104.48  5081.6  105.11  5111.3    97.1  5131.4    93.5
  5271.4    93.3  5301.3    95.7  5331.3  105.21  5371.3  108.31  5712.6   114.1
IW Dist,WD,Coef,Skew,MaxSub,Min_El,Is_Ogee,SpillHt,DesHd
10,1,3,0,.95,, 0 ,,,0,0,

Type RM Length L Ch R = 1 ,9880    ,104.7,103,94.7
BEGIN DESCRIPTION:
Cross Section FIELD_DS
Located At: 720 FEET US FROM MIRROR LAKE RD.
END DESCRIPTION:
XS GIS Cut Line= 4
      3086891.64      13946195.6      3086730.42     13945945.72
      3086518.49     13945743.64      3086248.09      13945505.4
#Sta/Elev= 30
  4556.3   112.3  4606.3     110  4636.3   107.4  4706.3   106.6  4736.3   107.5
  4796.3   106.8  4851.4   104.8  4858.8  104.25  4913.9  104.12  4950.7  103.52
  4996.5   88.53  5003.1   88.49  5050.4  104.39  5078.3  105.29    5112   93.49
  5127.2   91.75  5131.4    93.5  5181.4    92.9  5221.4    93.6  5271.4    93.3
  5281.4    93.7  5291.4    94.5  5301.4    95.7  5311.4    99.9  5321.4   102.9
  5331.4   105.2  5341.4   106.5  5371.4   108.3  5441.4   110.4  5501.4   110.5
#Mann= 6 ,-1 , 0
  4556.3      .1       0  4950.7     .02       0  5050.4     .05       0
  5078.3    .026       0  5331.4     .05       0  5441.4     .08       0
#XS Ineff= 2 , 0
       0  4975.2  101.43  5027.2       0  101.42
Permanent Ineff=
       F       F
#Block Obstruct= 1 ,-1
 5074.93 5390.39  105.12
Bank Sta=4950.7,5050.4
XS Rating Curve= 0
Exp/Cntr=.7,.5

Type RM Length L Ch R = 1 ,9777    ,164.7,469,512.2
BEGIN DESCRIPTION:
Weir_S4-1_DS- XS 1
END DESCRIPTION:
XS GIS Cut Line= 4
      3086949.89      13946113.1      3086712.87     13945779.71
      3086635.64     13945726.08      3086306.35     13945422.93
#Sta/Elev= 30
    4548  111.62    4648  111.38    4718  109.03    4738  107.73    4778  106.73
    4868  104.54    4908  104.74    4938  104.18  4957.1  100.91 4996.17   88.57
 5002.67   88.39  5027.1   96.49  5037.1    99.2  5051.1  101.88  5061.1  102.95
 5072.34  102.65  5091.1   98.77  5101.1    94.5  5131.1    93.6  5181.1   93.92
  5221.1   94.58  5231.1   95.24  5241.1   94.48  5261.1   97.65  5281.1  102.66
  5291.1  104.17  5321.1  106.72  5361.1  107.35  5411.1  110.09  5498.7  110.38
#Mann= 5 ,-1 , 0
    4548      .1       0    4938     .02       0 5072.34    .026       0
  5281.1     .05       0  5411.1     .08       0
#Block Obstruct= 2 , 0
                          5069.5          102.59
Bank Sta=4938,5061.1
XS Rating Curve= 0
Exp/Cntr=.3,.1

Type RM Length L Ch R = 1 ,9308    ,100,103,158.8
BEGIN DESCRIPTION:
S4_MIRROR LAKE RD-US-XS 4
END DESCRIPTION:
XS GIS Cut Line= 5
     3086949.631    13945991.722      3086885.77     13945566.07
     3086980.797    13945424.347     3086927.399    13945333.219
     3086994.534    13945061.772
#Sta/Elev= 30
  4291.9   111.3  4351.9  109.09  4411.9  107.93  4461.9  108.25  4601.9  106.04
  4621.9   106.2  4651.9   105.1  4671.9  102.23  4867.4   99.54  4907.4  100.27
  4957.4   99.56 4961.46   95.59 4975.93   92.11 4990.29   91.58 4991.82   90.69
 4992.23   89.48 4993.55   88.99 5000.58   87.92 5007.97   89.59 5011.82   91.11
  5016.6   91.23  5026.6   93.38  5046.6   99.59  5053.7  101.05  5073.7  102.69
  5113.7  103.82  5153.7   106.2  5243.7  106.47  5303.7  107.89  5333.3  107.72
#Mann= 3 , 0 , 0
  4291.9     .08       0  4957.4     .02       0  5053.7     .06       0
Bank Sta=4957.4,5053.7
XS Rating Curve= 0
Exp/Cntr=.5,.3

Type RM Length L Ch R = 1 ,9205    ,244.1,66,59.5
BEGIN DESCRIPTION:
Upstream Section of Bridge/Culvert/Weir
END DESCRIPTION:
XS GIS Cut Line= 5
        3087037.       13945948.      3086888.22     13945565.78
      3086935.53     13945494.83      3087080.88     13945278.13
       3087081.9       13945018.
#Sta/Elev= 30
    4308  111.31    4358  109.41    4378  108.01    4408  107.41    4418  107.91
    4568  108.71    4648  106.91    4688  105.01  4718.2  105.11  4741.5   104.3
  4884.8  101.81  4924.8  101.67  4953.2  100.54  4961.7   94.65  4975.9   91.49
  4984.1   92.11    4990   91.85  4991.5   90.91  4991.9   89.49  5000.1   87.81
  5007.2   89.24  5010.9   90.75  5029.7   96.65  5037.7  100.83    5048  102.14
  5181.3     105  5229.9  107.44  5283.5  108.74  5294.4  109.61  5324.4  110.61
#Mann= 3 ,-1 , 0
    4308     .08       0  4953.2     .02       0  5037.7     .06       0
#XS Ineff= 2 , 0
       0  4952.1  103.76  5047.9       0  103.75
Permanent Ineff=
       F       F
Bank Sta=4953.2,5037.7
XS Rating Curve= 0
Exp/Cntr=.5,.3

Type RM Length L Ch R = 3 ,9172    ,,,
BEGIN DESCRIPTION:
9190 Mirror Lake Road
Structure ID: K124-00-00-S4
Bridge deck width of 96 feet seems wrong based upon measurements from the sid images.  Reduced the bridge deck width from 96 feet to 45 feet. - JJA 3/20/03
END DESCRIPTION:
Bridge Culvert--1,0,-1,-1, 0
Deck Dist Width WeirC Skew NumUp NumDn MinLoCord MaxHiCord MaxSubmerge Is_Ogee
10,45,2.6,0, 60, 60, , , .95, 0, ,,,
  3159.3  3199.3  3219.3  3509.3  3569.3  3699.3  3819.3  3889.3  3999.3  4029.3
  4059.3  4089.3    4218    4238    4308    4358    4378    4408    4418    4568
    4648    4668    4678    4688  4718.2  4729.5  4737.3  4787.2  4838.8  4884.8
  4924.8  4942.8 4951.99  4952.1  5009.6 5047.67 5047.78 5047.89    5048  5058.5
  5078.7  5129.1  5181.3  5229.9  5249.5  5269.5  5274.2  5283.5    5284  5294.4
  5314.4  5324.4  5644.4  5814.4  5824.4  5834.4  5854.4  6004.4  6074.4    6093
   118.3   118.6   116.6   116.7   117.2   116.6     117   114.7   114.5   113.4
   113.3   114.3   114.4   113.2   111.3   109.4     108   107.4   107.9   108.7
   106.9   105.8   105.7     105   105.1  104.68   104.5  103.89  103.98  103.77
  103.76  103.76  104.26  106.91  106.92  107.34  104.34  104.33  104.33  103.84
  103.75  104.66  106.03  107.44   108.4   108.6   108.9  108.73  108.88   109.6
     110   110.6   116.4   117.7   118.2   119.5   120.4   121.4   120.5   120.8
   118.3   118.6   116.6   116.7   117.2   116.6     117   114.7   114.5   113.4
   113.3   114.3   114.4   113.2   111.3   109.4     108   107.4   107.9   108.7
   106.9   105.8   105.7     105   105.1  104.67  104.38  103.62  102.74   101.8
  101.66  100.94  100.58  102.46  102.47  102.89  102.89  102.88  102.13  102.34
  102.73  103.94  104.99  107.43  107.91  108.39   108.5  108.73  108.88   109.6
     110   110.6   116.4   117.7   118.2   119.5   120.4   121.4   120.5   120.8
  3159.3  3199.3  3219.3  3509.3  3569.3  3699.3  3819.3  3889.3  3999.3  4029.3
  4059.3  4089.3    4218    4238    4308    4358    4378    4408    4418    4568
    4648    4668    4678    4688  4718.2  4729.5  4737.3  4787.2  4838.8  4884.8
  4924.8  4942.8 4951.99  4952.1  5009.6 5047.67 5047.78 5047.89    5048  5058.5
  5078.7  5129.1  5181.3  5229.9  5249.5  5269.5  5274.2  5283.5    5284  5294.4
  5314.4  5324.4  5644.4  5814.4  5824.4  5834.4  5854.4  6004.4  6074.4    6093
   118.3   118.6   116.6   116.7   117.2   116.6     117   114.7   114.5   113.4
   113.3   114.3   114.4   113.2   111.3   109.4     108   107.4   107.9   108.7
   106.9   105.8   105.7     105   105.1  104.68   104.5  103.89  103.98  103.77
  103.76  103.76  104.26  106.91  106.92  107.34  104.34  104.33  104.33  103.84
  103.75  104.66  106.03  107.44   108.4   108.6   108.9  108.73  108.88   109.6
     110   110.6   116.4   117.7   118.2   119.5   120.4   121.4   120.5   120.8
   118.3   118.6   116.6   116.7   117.2   116.6     117   114.7   114.5   113.4
   113.3   114.3   114.4   113.2   111.3   109.4     108   107.4   107.9   108.7
   106.9   105.8   105.7     105   105.1  104.67  104.38  103.62  102.74   101.8
  101.66  100.94  100.58  102.46  102.47  102.89  102.89  102.88  102.13  102.34
  102.73  103.94  104.99  107.43  107.91  108.39   108.5  108.73  108.88   109.6
     110   110.6   116.4   117.7   118.2   119.5   120.4   121.4   120.5   120.8
Pier Skew, UpSta & Num, DnSta & Num=  ,4984.1, 2 ,4984.1, 2 , 0 , 0 , 0 ,,
     1.4     1.4
   91.05  103.44
     1.4     1.4
   91.93  104.32
Pier Skew, UpSta & Num, DnSta & Num=  ,5016.3, 2 ,5016.3, 2 , 0 , 0 , 0 ,,
     1.4     1.4
   90.98  103.55
     1.4     1.4
   91.86  104.43
BR Coef= 1 , 1 , 1 ,1.25, 0 ,,,.8,0,2,0,
WSPro=,,,, 1 ,,,, 0 ,,,, 0 ,,,,-1 ,-1 ,-1 , 0 , 0 , 0 , 0 , 0
BR U #Sta/Elev= 95
  3159.3   118.3  3199.3   118.6  3219.3   116.6  3509.3   116.7  3569.3   117.2
  3699.3   116.6  3819.3     117  3889.3   114.7  3999.3   114.5  4029.3   113.4
  4059.3   113.3  4089.3   114.3    4128   114.3    4218   114.4    4238   113.2
    4308   111.3    4358   109.4    4378     108    4408   107.4    4418   107.9
    4568   108.7    4648   106.9    4668   105.8    4678   105.7    4688     105
    4718   105.1  4718.2   105.1  4729.5  104.67  4737.3  104.38  4741.5  104.29
  4787.2  103.62  4787.5  103.62  4838.1  102.75  4838.8  102.74  4883.7  101.82
  4884.8   101.8  4924.8  101.66  4942.8  100.94  4951.8  100.59 4951.91  100.58
 4951.99  100.58  4952.1  100.57  4952.2  100.57 4952.31  100.57  4953.2  100.53
  4953.3  100.46  4961.7   94.64  4962.7   94.42  4975.9   91.48  4984.1    92.1
    4990   91.84  4991.5    90.9  4991.9   89.48  4993.2      89  5000.1    87.8
  5007.2   89.23    5008   89.52  5009.6   90.19  5010.9   90.74  5016.3   92.17
  5029.7   96.64  5037.7  100.82 5047.46  102.06 5047.57  102.08 5047.67  102.09
 5047.78   102.1 5047.89  102.12    5048  102.13  5048.1  102.13  5058.5  102.34
  5058.6  102.34  5078.7  102.73    5079  102.74  5129.1  103.94  5129.9  103.96
  5181.3  104.99  5182.5  105.05  5229.9  107.43    5231  107.46  5249.5  107.91
  5269.5  108.39  5274.2   108.5  5283.5  108.73    5284  108.88  5294.4   109.6
  5314.4     110  5324.4   110.6  5644.4   116.4  5814.4   117.7  5824.4   118.2
  5834.4   119.5  5854.4   120.4  6004.4   121.4  6074.4   120.5    6093   120.8
BR U #Mann= 3
  3159.3     .08  4953.2     .02  5037.7     .08
BR U Banks=4953.2,5037.7
BR D #Sta/Elev= 95
  3159.3   118.3  3199.3   118.6  3219.3   116.6  3509.3   116.7  3569.3   117.2
  3699.3   116.6  3819.3     117  3889.3   114.7  3999.3   114.5  4029.3   113.4
  4059.3   113.3  4089.3   114.3    4128   114.3    4218   114.4    4238   113.2
    4308   111.3    4358   109.4    4378     108    4408   107.4    4418   107.9
    4568   108.7    4648   106.9    4668   105.8    4678   105.7    4688     105
    4718   105.1  4718.2   105.1  4729.5  104.67  4737.3  104.38  4741.5  104.29
  4787.2  103.62  4787.5  103.62  4838.1  102.75  4838.8  102.74  4883.7  101.82
  4884.8   101.8  4924.8  101.66  4942.8  100.94  4951.8  100.59 4951.91  100.58
 4951.99  100.58  4952.1  100.57  4952.2  100.57 4952.31  100.57  4953.2  100.53
  4953.3  100.48  4961.7   95.52  4962.7    95.3  4975.9   92.36  4984.1   92.98
    4990   92.72  4991.5   91.78  4991.9   90.36  4993.2   89.88  5000.1   88.68
  5007.2   90.11    5008    90.4  5009.6   91.07  5010.9   91.62  5016.3   93.05
  5029.7   97.52  5037.7   101.7 5047.46  102.06 5047.57  102.08 5047.67  102.09
 5047.78   102.1 5047.89  102.12    5048  102.13  5048.1  102.13  5058.5  102.34
  5058.6  102.34  5078.7  102.73    5079  102.74  5129.1  103.94  5129.9  103.96
  5181.3  104.99  5182.5  105.05  5229.9  107.43    5231  107.46  5249.5  107.91
  5269.5  108.39  5274.2   108.5  5283.5  108.73    5284  108.88  5294.4   109.6
  5314.4     110  5324.4   110.6  5644.4   116.4  5814.4   117.7  5824.4   118.2
  5834.4   119.5  5854.4   120.4  6004.4   121.4  6074.4   120.5    6093   120.8
BR D #Mann= 3
  3159.3     .08  4953.2     .02  5037.7     .08
BR D Banks=4953.2,5037.7
BC Design=,, 0 ,, 0 ,,,,,,
BC HTab HWMax=111.31

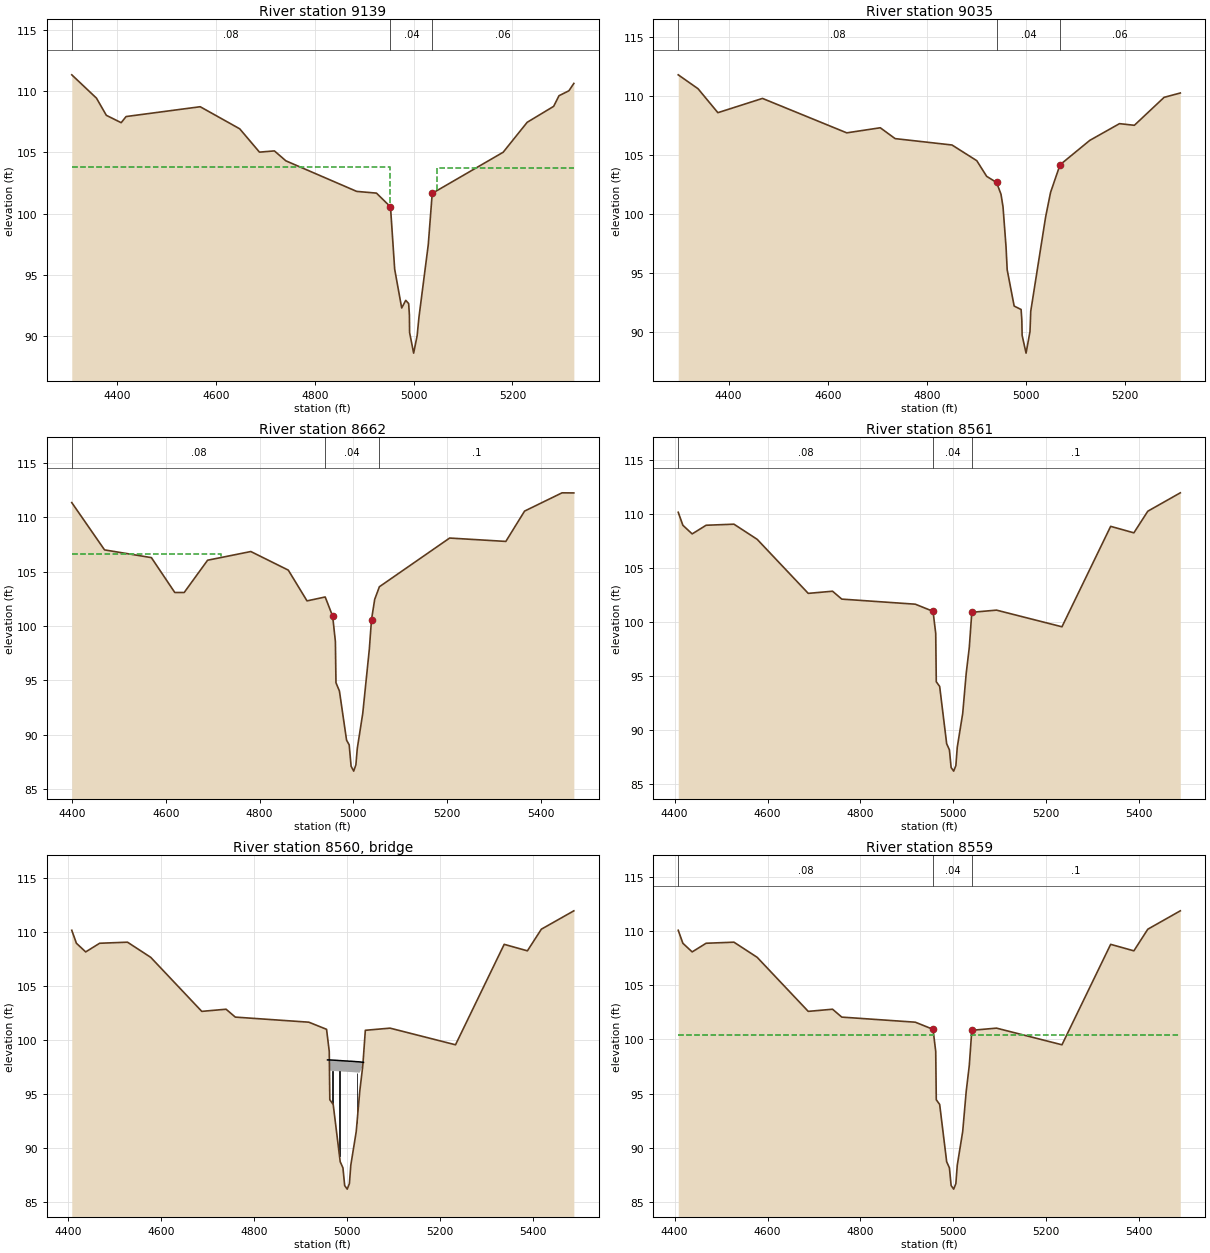
Type RM Length L Ch R = 1 ,9139    ,121.3,104,85.9
BEGIN DESCRIPTION:
Downstream Section of Bridge/Culvert/Weir
END DESCRIPTION:
XS GIS Cut Line= 5
      3087097.84      13945952.9      3086949.99       13945573.
      3086991.52      13945510.8      3087140.22      13945289.1
      3087141.27       13945023.
#Sta/Elev= 30
    4308  111.31    4358  109.41    4378  108.01    4408  107.41    4418  107.91
    4568  108.71    4648  106.91    4688  105.01  4718.2  105.11  4741.5   104.3
  4884.8  101.81  4924.8  101.67 4953.22  100.55  4961.7   95.47  4975.9   92.31
  4984.1   92.93    4990   92.67  4991.5   91.73  4991.9   90.31  5000.1   88.63
  5007.2   90.06  5010.9   91.57  5029.7   97.47  5037.7  101.65  5181.3     105
  5229.9  107.44  5283.5  108.74  5294.4  109.61  5314.4  110.01  5324.4  110.61
#Mann= 3 ,-1 , 0
    4308     .08       0 4953.22     .04       0  5037.7     .06       0
#XS Ineff= 2 , 0
       0  4952.1  103.76  5047.9       0  103.75
Permanent Ineff=
       F       F
Bank Sta=4953.22,5037.7
XS Rating Curve= 0
Exp/Cntr=.5,.3

Type RM Length L Ch R = 1 ,9035    ,384.6,373,348.7
BEGIN DESCRIPTION:
S4_MIRROR LAKE RD-DS-XS 1
END DESCRIPTION:
XS GIS Cut Line= 6
      3087198.16       13945969.      3087050.31     13945589.18
      3087091.84     13945526.98      3087200.39     13945397.58
      3087225.06     13945291.39      3087241.59     13945039.18
#Sta/Elev= 30
  4298.4  111.82  4338.4  110.64  4378.4  108.61  4468.4  109.82  4638.4   106.9
  4706.1  107.33  4736.1  106.41  4850.8  105.87  4900.8  104.54  4920.8  103.21
  4940.8  102.69  4949.7  101.69 4953.77  100.62 4959.83   97.24 4962.17   95.29
 4976.25   92.21 4990.23   91.92 4991.72   91.03 4992.31   89.73 5000.24   88.22
 5008.19   90.05  5009.7   91.77  5039.7   99.76  5049.7  101.85  5068.8  104.19
  5128.8  106.26  5188.8  107.68  5218.8  107.54  5278.8  109.91  5311.5  110.28
#Mann= 3 , 0 , 0
  4298.4     .08       0  4940.8     .04       0  5068.8     .06       0
Bank Sta=4940.8,5068.8
XS Rating Curve= 0
Exp/Cntr=.3,.1

Type RM Length L Ch R = 1 ,8662    ,70.7,101,123.7
BEGIN DESCRIPTION:
PL2_K124-00-00-S3_US-XS 4
END DESCRIPTION:
XS GIS Cut Line= 5
      3087419.41      13945916.3      3087439.15     13945584.69
      3087578.79     13945429.43      3087587.69     13945324.07
      3087392.78     13944946.16
#Sta/Elev= 30
  4398.8  111.36  4468.8  107.01  4568.8   106.3  4618.8  103.09  4638.8  103.09
  4688.8  106.06  4781.1  106.86  4861.1  105.15  4901.1  102.32  4939.9  102.68
 4955.84  100.91  4961.7   98.57 4962.91   94.79 4970.29   94.03 4985.53   89.51
  4991.1   89.08 4995.23   87.11 5000.78   86.66 5005.45   87.24 5008.43   88.75
 5020.06   91.96 5034.16   97.89 5038.79   100.6  5045.6  102.46  5055.6  103.62
  5205.6   108.1  5325.6  107.79  5365.6  110.58  5445.6  112.26  5470.8  112.25
#Mann= 3 ,-1 , 0
  4398.8     .08       0  4939.9     .04       0  5055.6      .1       0
#XS Ineff= 2 , 0
       0    4718   106.6               0
Permanent Ineff=
       F       F
Bank Sta=4955.84,5038.79
XS Rating Curve= 0
Exp/Cntr=.5,.3

Type RM Length L Ch R = 1 ,8561    ,2,2,2.1
BEGIN DESCRIPTION:
Upstream Section of Bridge/Culvert/Weir
END DESCRIPTION:
XS GIS Cut Line= 4
      3087521.35      13945921.2      3087541.08      13945589.5
      3087713.66      13945333.1      3087494.72       13944951.
#Sta/Elev= 30
  4407.7  110.15  4417.7  108.95  4437.7  108.15  4467.7  108.95  4527.7  109.05
  4577.7  107.65  4687.7  102.65    4740  102.85 4759.94  102.12 4918.24  101.65
 4956.44  100.99 4962.24   98.95 4963.44   94.48 4970.74   94.04 4985.84   88.74
 4991.74   88.18 4995.44   86.54 5000.94   86.21 5005.64   86.72 5008.64   88.42
 5020.34   91.54 5027.94   95.27 5034.54   97.65 5039.94   100.9 5093.14   101.1
 5234.14   99.56    5339  108.85    5389  108.25    5419  110.25    5489  111.95
#Mann= 3 ,-1 , 0
  4407.7     .08       0 4956.44     .04       0 5039.94      .1       0
#XS Ineff= 2 , 0
       0 4958.02  100.41 5039.12       0   100.4
Permanent Ineff=
       F       F
Bank Sta=4956.44,5039.94
XS Rating Curve= 0
Exp/Cntr=.5,.3

Type RM Length L Ch R = 3 ,8560    ,,,
BEGIN DESCRIPTION:
8554 PL2_K124-00-00-S3
END DESCRIPTION:
Bridge Culvert--1,0,-1,-1, 0
Deck Dist Width WeirC Skew NumUp NumDn MinLoCord MaxHiCord MaxSubmerge Is_Ogee
.5,1,2.6,0, 19, 19, , , .95, 0, ,,,
 4958.54 4962.24 4963.44 4970.74 4978.74 4983.94 4985.84 4988.24 4991.74 4993.34
 4995.44 5000.94 5005.64 5006.64 5008.64 5015.04 5020.34 5027.94    5036
   98.16   98.16   98.16   98.14   98.12    98.1    98.1   98.09   98.08   98.08
   98.07   98.06   98.04   98.04   98.04   98.02      98   97.98   97.93
   97.16   97.16   97.16   97.14   97.12    97.1    97.1   97.09   97.08   97.08
   97.07   97.06   97.04   97.04   97.04   97.02      97   96.98   96.93
 4958.54 4962.24 4963.44 4970.74 4978.74 4983.94 4985.84 4988.24 4991.74 4993.34
 4995.44 5000.94 5005.64 5006.64 5008.64 5015.04 5020.34 5027.94    5036
   98.16   98.16   98.16   98.14   98.12    98.1    98.1   98.09   98.08   98.08
   98.07   98.06   98.04   98.04   98.04   98.02      98   97.98   97.93
   97.16   97.16   97.16   97.14   97.12    97.1    97.1   97.09   97.08   97.08
   97.07   97.06   97.04   97.04   97.04   97.02      97   96.98   96.93
Pier Skew, UpSta & Num, DnSta & Num=  ,4968.4, 2 ,4968.4, 2 , 0 , 0 , 0 ,,
       2       2
   93.37   99.61
       2       2
   93.37   99.61
Pier Skew, UpSta & Num, DnSta & Num=  ,4984.4, 2 ,4984.4, 2 , 0 , 0 , 0 ,,
       2       2
   89.79   98.12
       2       2
   89.79   98.12
Pier Skew, UpSta & Num, DnSta & Num=  ,5022, 2 ,5022, 2 , 0 , 0 , 0 ,,
       2       2
   89.44   98.02
       2       2
   89.44   98.02
BR Coef= 1 , 1 , 1 ,1.25, 0 ,,,.8,0,2,0,
WSPro=,,,, 1 ,,,, 0 ,,,, 0 ,,,,-1 ,-1 ,-1 , 0 , 0 , 0 , 0 , 0
BC Design=,, 0 ,, 0 ,,,,,,
BC HTab HWMax=111.95

Type RM Length L Ch R = 1 ,8559    ,1.1,2,1
BEGIN DESCRIPTION:
Downstream Section of Bridge/Culvert/Weir
END DESCRIPTION:
XS GIS Cut Line= 4
       3087523.4      13945921.3      3087543.13      13945589.6
      3087715.71      13945333.3      3087496.91      13944951.4
#Sta/Elev= 30
  4407.7   110.1  4417.7   108.9  4437.7   108.1  4467.7   108.9  4527.7     109
  4577.7   107.6  4687.7   102.6    4740   102.8 4759.94  102.07 4918.24   101.6
 4956.44  100.94 4962.24    98.9 4963.44   94.43 4970.74   93.99 4985.84   88.69
 4991.74   88.13 4995.44   86.49 5000.94   86.16 5005.64   86.67 5008.64   88.37
 5020.34   91.49 5027.94   95.22 5034.54    97.6 5039.94  100.85 5093.14  101.05
 5234.14   99.51    5339   108.8    5389   108.2    5419   110.2    5489   111.9
#Mann= 3 ,-1 , 0
  4407.7     .08       0 4956.44     .04       0 5039.94      .1       0
#XS Ineff= 2 , 0
       0 4958.02  100.41 5039.12       0   100.4
Permanent Ineff=
       F       F
Bank Sta=4956.44,5039.94
XS Rating Curve= 0
Exp/Cntr=.5,.3

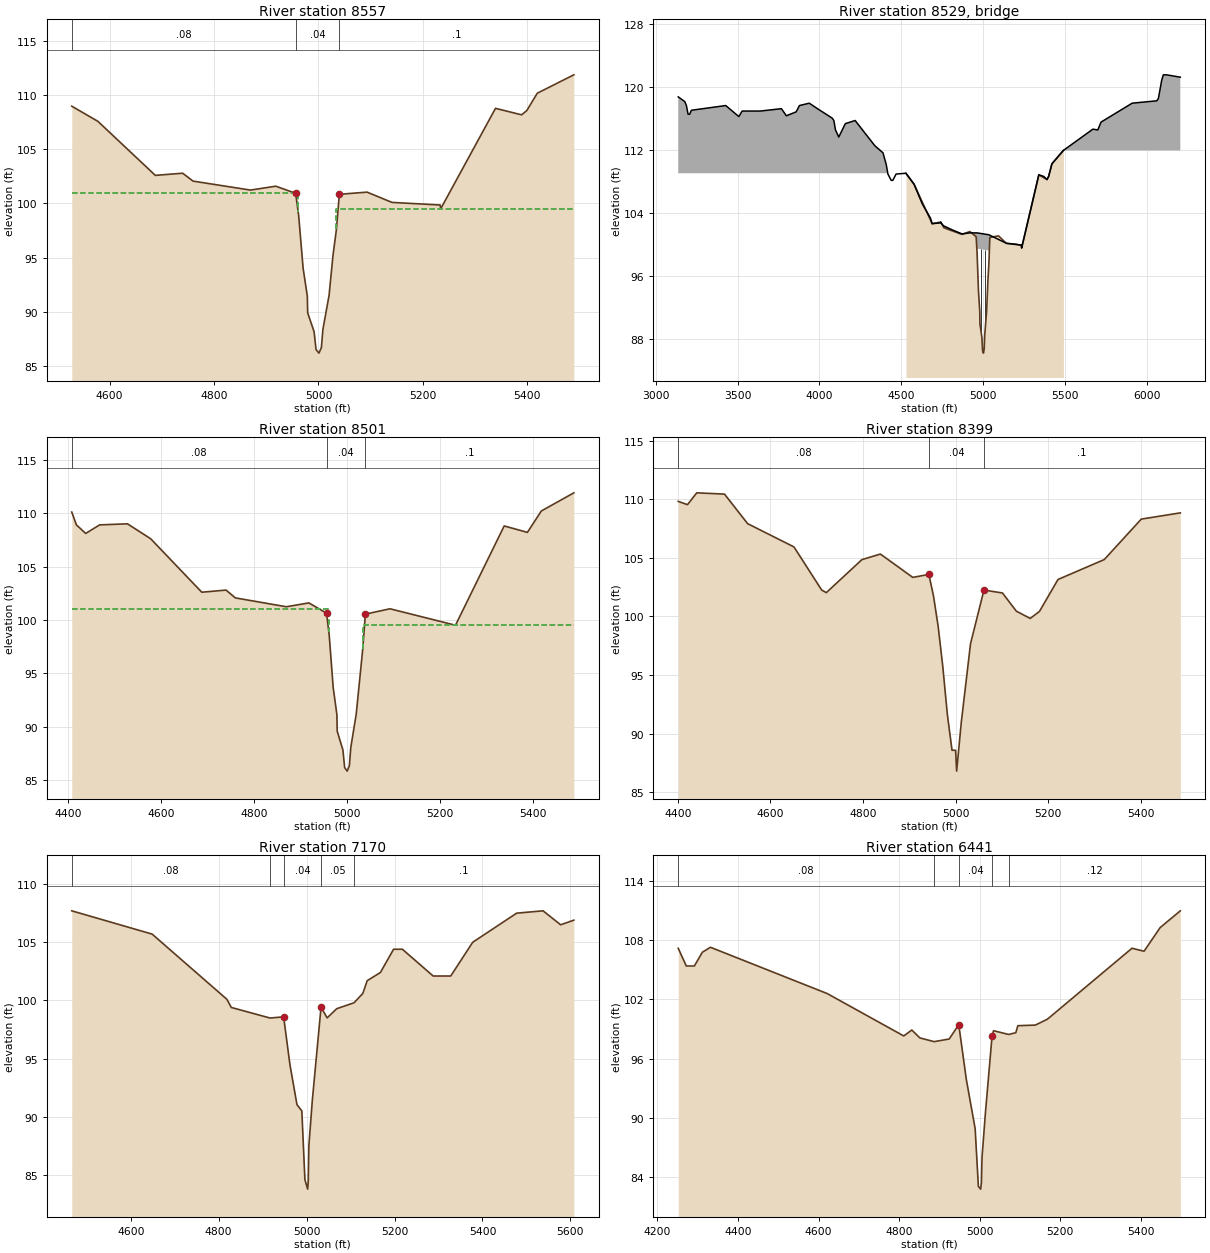
Type RM Length L Ch R = 1 ,8557    ,59.3,56,55.8
BEGIN DESCRIPTION:
Upstream Section of Bridge/Culvert/Weir
END DESCRIPTION:
XS GIS Cut Line= 5
      3087531.56      13945801.6      3087544.17      13945589.7
       3087662.6      13945413.9      3087716.75      13945333.3
      3087497.46      13944950.6
#Sta/Elev= 30
  4527.7     109  4577.7   107.6  4687.7   102.6    4740   102.8  4759.9  102.07
  4869.8  101.24  4918.3   101.6  4956.4  100.94  4962.1    98.9  4970.7   93.99
  4978.7   91.44  4979.4   89.89  4991.7   88.13  4995.4   86.49  5000.9   86.16
  5005.6   86.67  5008.6   88.37  5020.3   91.49  5027.9   95.22  5034.4    97.6
    5040  100.85  5093.1  101.05  5140.9   100.1    5233   99.86  5234.1   99.51
    5339   108.8    5389   108.2    5399   108.6    5419   110.2    5489   111.9
#Mann= 3 ,-1 , 0
  4527.7     .08       0  4956.4     .04       0    5040      .1       0
#XS Ineff= 2 , 0
       0  4961.3     101  5034.4       0   99.51
Permanent Ineff=
       F       F
Bank Sta=4956.4,5040
XS Rating Curve= 0
Exp/Cntr=.5,.3

Type RM Length L Ch R = 3 ,8529    ,,,
BEGIN DESCRIPTION:
8542 Candle Creek Road
Structure ID: K124-00-00-S3
END DESCRIPTION:
Bridge Culvert--1,0,-1,-1, 0
Deck Dist Width WeirC Skew NumUp NumDn MinLoCord MaxHiCord MaxSubmerge Is_Ogee
10,38,2.6,0, 77, 77, , , .95, 0, ,,,
  3137.7  3177.7  3187.7  3197.7  3207.7  3217.7  3427.7  3507.7  3527.7  3637.7
  3767.7  3797.7  3857.7  3877.7  3937.7  3987.7  4077.7  4087.7  4097.7  4117.7
  4157.7  4217.7  4337.7  4387.7  4407.7  4417.7  4437.7  4447.7  4467.7  4527.7
  4577.7  4627.7  4677.7  4687.7  4737.7    4740  4749.2  4758.9  4759.9  4813.6
  4813.7  4869.8  4869.9  4918.2  4918.3  4956.4  4959.8 4960.87 4960.98 4961.09
 4961.21  4961.3  5034.4  5140.9    5142  5191.8    5198  5231.3    5233  5234.1
    5339    5369    5389    5399    5419    5489    5669    5699    5719    5909
    6059    6069    6089    6099    6119  6202.7  6202.8
   118.7   118.1   117.6   116.5   116.5     117   117.6   116.2   116.9   116.9
   117.2   116.3   116.8   117.6   117.9   117.2     116   115.7   114.5   113.6
   115.3   115.7   112.5   111.6   110.1   108.9   108.1   108.1   108.9     109
   107.6   105.1   103.3   102.6   102.7   102.8  102.51  102.31   102.3  101.78
  101.78   101.3   101.3  101.43  101.43  101.43  101.43  101.43  101.43  101.43
  101.43  101.43  101.19  100.11  100.11     100   99.99   99.88   99.86   99.51
   108.8   108.6   108.2   108.6   110.2   111.9   114.6   114.5   115.5   117.9
   118.2   118.5   120.8   121.5   121.5   121.2   121.2
                                                                                
                                                                                
                                                                                
                                                                                
                                                                                
           99.43   99.19
                                                                                
                                                        
  3137.7  3177.7  3187.7  3197.7  3207.7  3217.7  3427.7  3507.7  3527.7  3637.7
  3767.7  3797.7  3857.7  3877.7  3937.7  3987.7  4077.7  4087.7  4097.7  4117.7
  4157.7  4217.7  4337.7  4387.7  4407.7  4417.7  4437.7  4447.7  4467.7  4527.7
  4577.7  4627.7  4677.7  4687.7  4737.7    4740  4749.2  4758.9  4759.9  4813.6
  4813.7  4869.8  4869.9  4918.2  4918.3  4956.4  4959.8 4960.87 4960.98 4961.09
 4961.21  4961.3  5034.4  5140.9    5142  5191.8    5198  5231.3    5233  5234.1
    5339    5369    5389    5399    5419    5489    5669    5699    5719    5909
    6059    6069    6089    6099    6119  6202.7  6202.8
   118.7   118.1   117.6   116.5   116.5     117   117.6   116.2   116.9   116.9
   117.2   116.3   116.8   117.6   117.9   117.2     116   115.7   114.5   113.6
   115.3   115.7   112.5   111.6   110.1   108.9   108.1   108.1   108.9     109
   107.6   105.1   103.3   102.6   102.7   102.8  102.51  102.31   102.3  101.78
  101.78   101.3   101.3  101.43  101.43  101.43  101.43  101.43  101.43  101.43
  101.43  101.43  101.19  100.11  100.11     100   99.99   99.88   99.86   99.51
   108.8   108.6   108.2   108.6   110.2   111.9   114.6   114.5   115.5   117.9
   118.2   118.5   120.8   121.5   121.5   121.2   121.2
                                                                                
                                                                                
                                                                                
                                                                                
                                                                                
           99.43   99.19
                                                                                
                                                        
Pier Skew, UpSta & Num, DnSta & Num=  ,4985.8, 2 ,4985.8, 2 , 0 , 0 , 0 ,,
     1.2     1.2
    88.1  100.72
     1.2     1.2
   87.82  100.44
Pier Skew, UpSta & Num, DnSta & Num=  ,5011.3, 2 ,5011.3, 2 , 0 , 0 , 0 ,,
     1.2     1.2
   85.65  100.71
     1.2     1.2
   85.37  100.43
BR Coef= 1 , 1 , 1 ,1.25, 0 ,,,.8,0,2,0,
WSPro=,,,, 1 ,,,, 0 ,,,, 0 ,,,,-1 ,-1 ,-1 , 0 , 0 , 0 , 0 , 0
BC Design=,, 0 ,, 0 ,,,,,,
BC HTab HWMax=111.9

Type RM Length L Ch R = 1 ,8501    ,129.7,102,82
BEGIN DESCRIPTION:
Downstream Section of Bridge/Culvert/Weir
END DESCRIPTION:
XS GIS Cut Line= 5
      3087578.18      13945927.9      3087597.59     13945601.74
      3087712.98     13945430.48      3087774.06     13945339.58
      3087549.13       13944947.
#Sta/Elev= 30
  4407.7   110.1  4417.7   108.9  4437.7   108.1  4467.7   108.9  4527.7     109
  4577.7   107.6  4687.7   102.6    4740   102.8  4759.9  102.07  4869.8  101.24
  4918.3   101.6  4956.4  100.64  4962.1    98.6  4970.7   93.69  4978.7   91.14
  4979.4   89.59  4991.7   87.83  4995.4   86.19  5000.9   85.86  5005.6   86.37
  5008.6   88.07  5020.3   91.19  5034.4    97.3    5040  100.55  5093.1  101.05
  5234.1   99.51    5339   108.8    5389   108.2    5419   110.2    5489   111.9
#Mann= 3 ,-1 , 0
  4407.7     .08       0  4956.4     .04       0    5040      .1       0
#XS Ineff= 2 , 0
       0  4961.3     101  5034.4       0   99.51
Permanent Ineff=
       F       F
Bank Sta=4956.4,5040
XS Rating Curve= 0
Exp/Cntr=.5,.3

Type RM Length L Ch R = 1 ,8399    ,1260.9,1229,1215.4
BEGIN DESCRIPTION:
S3_CANDLE CREEK RD-DS-XS 1
END DESCRIPTION:
XS GIS Cut Line= 5
      3087678.51      13945934.4      3087697.91     13945608.21
      3087839.22     13945446.49      3087851.09     13945338.17
      3087649.45     13944953.48
#Sta/Elev= 30
  4400.7  109.81  4420.7  109.53  4440.7  110.54  4500.7  110.43  4550.7  107.91
  4650.7  105.93  4710.7  102.25  4720.7  102.03  4797.5  104.84  4837.5  105.32
  4907.5  103.33  4942.3  103.58  4952.3  101.74  4962.3   99.17  4972.3   95.75
  4982.3   91.62  4992.3   88.59    5000   88.59  5002.3   86.81  5012.3   90.96
  5032.3   97.67  5061.3  102.25  5101.3     102  5131.3  100.45  5161.3   99.83
  5181.3  100.43  5221.3  103.15  5321.3  104.85  5401.3   108.3  5485.6  108.83
#Mann= 3 , 0 , 0
  4400.7     .08       0  4942.3     .04       0  5061.3      .1       0
#XS Ineff= 2 , 0
       0    4835     105               0
Permanent Ineff=
       F       F
Bank Sta=4942.3,5061.3
XS Rating Curve= 0
Exp/Cntr=.3,.1

Type RM Length L Ch R = 1 ,7170    ,623.7,729,778.4
BEGIN DESCRIPTION:
Cross Section K124-00-00-X04
END DESCRIPTION:
XS GIS Cut Line= 5
      3089025.44      13945676.5      3089070.89     13945619.63
      3089055.96     13945223.07      3089024.08     13945125.89
      3088945.57      13944561.2
#Sta/Elev= 30
  4465.9   107.7  4648.7   105.7  4818.7   100.1  4828.7    99.4  4916.8   98.49
  4947.8   98.59  4962.1    94.5  4978.1   91.05  4989.2   90.51  4996.2    84.6
  5002.5   83.79  5003.8   84.48  5005.2   87.53  5013.1   91.44  5032.9   99.43
  5046.7    98.5  5068.5   99.29  5107.9    99.8  5127.9   100.6  5137.9   101.7
  5167.9   102.4  5197.9   104.4  5217.9   104.4  5287.9   102.1  5327.9   102.1
  5377.9     105  5477.9   107.5  5537.9   107.7  5577.9   106.5  5607.9   106.9
#Mann= 5 ,-1 , 0
  4465.9     .08       0  4916.8     .05       0  4947.8     .04       0
  5032.9     .05       0  5107.9      .1       0
#Block Obstruct= 2 , 0
                         5219.36          104.24
Bank Sta=4947.8,5032.9
XS Rating Curve= 0
Exp/Cntr=.3,.1

Type RM Length L Ch R = 1 ,6441    ,919.4,838,764.8
BEGIN DESCRIPTION:
Cross Section K124-00-00-X03
END DESCRIPTION:
XS GIS Cut Line= 4
      3089204.33      13945748.6      3089691.23     13945234.61
      3089737.96     13945159.22      3089873.63      13944730.1
#Sta/Elev= 30
  4251.6   107.2  4271.6   105.4  4291.6   105.4  4311.6   106.8  4331.6   107.3
  4621.6   102.6  4811.6    98.3  4831.6    98.9  4851.6    98.1    4887   97.72
  4924.4   97.99  4948.2   99.44  4967.1   93.85  4988.9   88.88  4996.9   83.02
  5002.5   82.75  5004.4   83.39  5005.9   85.95  5014.3   90.46  5030.9    98.3
  5034.6   98.83  5072.1   98.45 5089.84   98.63 5094.86   99.34  5138.3    99.4
  5168.3     100  5378.3   107.2  5408.3   106.9  5448.3   109.3  5498.3     111
#Mann= 5 ,-1 , 0
  4251.6     .08       0    4887     .05       0  4948.2     .04       0
  5030.9     .05       0  5072.1     .12       0
Bank Sta=4948.2,5030.9
XS Rating Curve= 0
Exp/Cntr=.3,.1

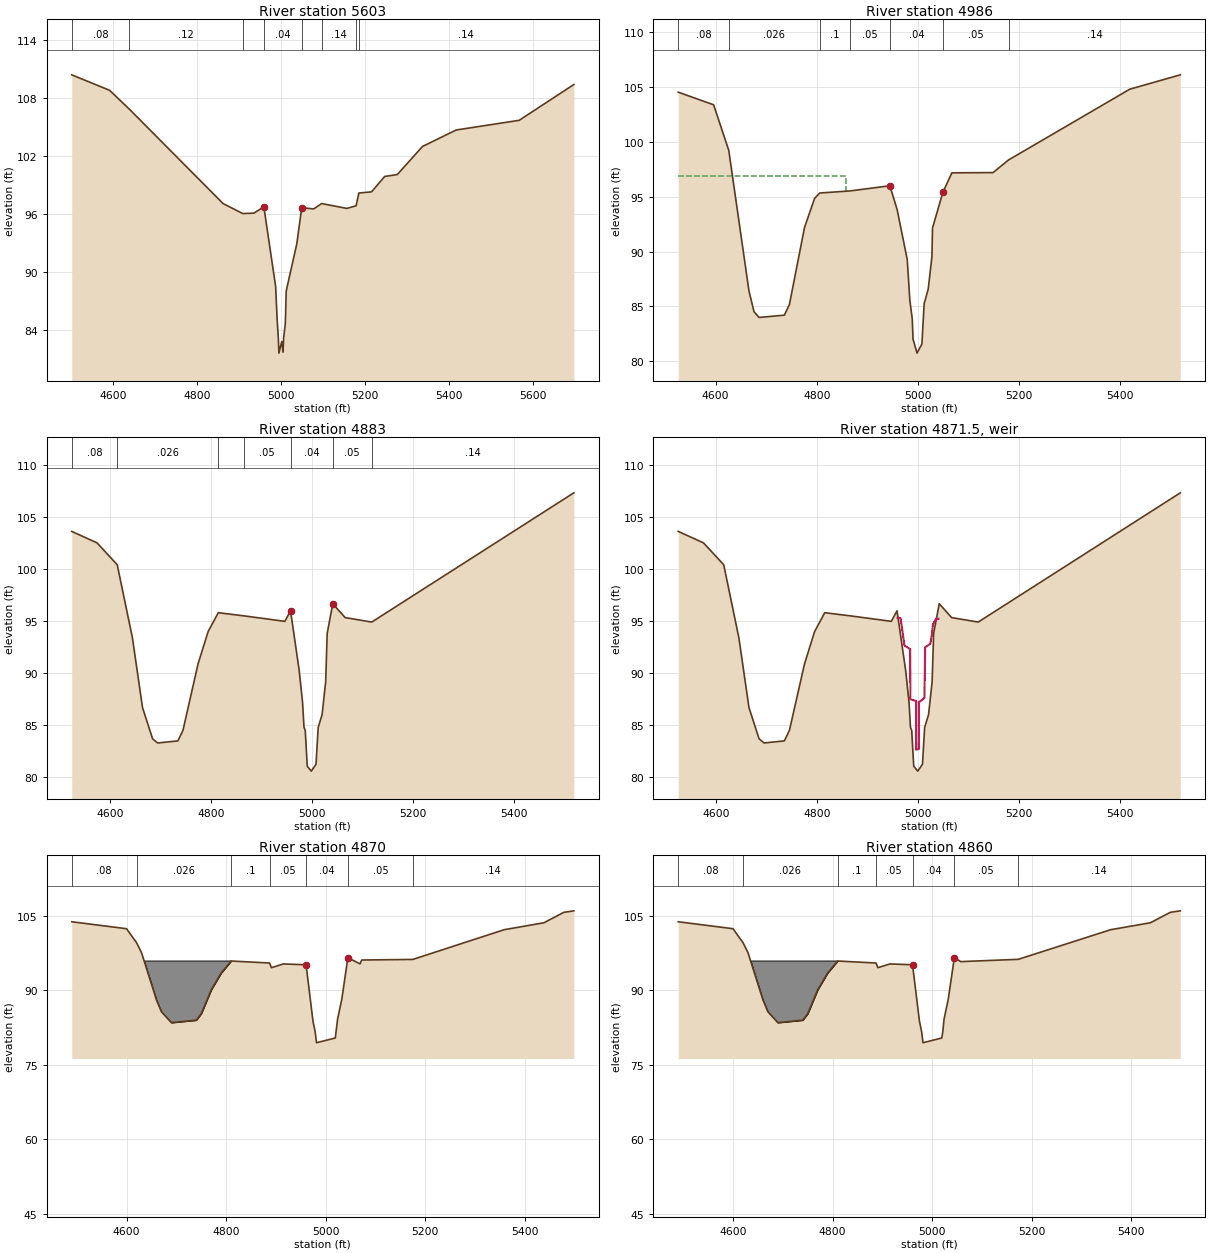
Type RM Length L Ch R = 1 ,5603    ,622.2,617,605.4
BEGIN DESCRIPTION:
Cross Section K124-00-00-X02
END DESCRIPTION:
XS GIS Cut Line= 4
      3090582.95      13945972.5      3090473.26     13945534.91
      3090439.16     13945437.48      3090334.57       13944806.
#Sta/Elev= 30
  4502.3   110.4  4592.3   108.8  4638.2   106.9  4862.3    97.1    4909   96.07
  4935.3   96.11  4959.3   96.75  4987.3   88.54  4990.8   85.19  4993.7   83.21
  4995.1   81.65  5001.8   82.85    5005   81.75  5006.3   83.21  5010.3   84.72
  5012.5   88.08  5037.6   92.94  5049.4   96.67  5077.8   96.55  5096.7    97.1
  5156.7    96.6 5178.67   96.87 5185.29   98.19 5215.48   98.31  5246.7    99.9
  5276.7   100.1  5336.7     103  5416.7   104.7  5566.7   105.7  5696.7   109.4
#Mann= 8 ,-1 , 0
  4502.3     .08       0  4638.2     .12       0    4909     .05       0
  4959.3     .04       0  5049.4     .05       0  5096.7     .14       0
 5178.67     .08       0 5185.29     .14       0
Bank Sta=4959.3,5049.4
XS Rating Curve= 0
Exp/Cntr=.3,.1

Type RM Length L Ch R = 1 ,4986    ,100.4,103,100.6
BEGIN DESCRIPTION:
Weir S1-1_US-XS 4
END DESCRIPTION:
XS GIS Cut Line= 6
      3091116.64      13945727.4      3091067.39     13945361.97
      3091050.61     13945310.16      3091016.99     13945226.12
       3091001.2     13945189.52      3090819.27     13944788.91
#Sta/Elev= 30
  4525.9  104.53  4595.9  103.38  4625.9   99.23  4665.9   86.41  4675.9   84.52
  4685.9      84  4735.9   84.21  4745.9   85.18  4775.9   92.21  4795.9   94.86
  4805.9   95.34  4865.9   95.53  4944.7      96  4959.1   93.83  4979.1   89.28
 4984.21   85.59 4989.02   83.87 4990.59   82.03 4998.44   80.75 5008.11   81.58
 5012.58   85.26 5020.59   86.58 5027.97   89.54  5029.1   92.15  5049.6    95.4
 5067.43   97.18 5148.89    97.2  5179.5   98.35  5419.5   104.8  5519.5  106.11
#Mann= 7 ,-1 , 0
  4525.9     .08       0  4625.9    .026       0  4805.9      .1       0
  4865.9     .05       0  4944.7     .04       0  5049.6     .05       0
  5179.5     .14       0
#XS Ineff= 2 , 0
       0    4857    96.9               0
Permanent Ineff=
       F       F
#Block Obstruct= 2 , 0
         4806.62   95.25
Bank Sta=4944.7,5049.6
XS Rating Curve= 0
Exp/Cntr=.7,.5

Type RM Length L Ch R = 1 ,4883    ,13,13,13
BEGIN DESCRIPTION:
Upstream Section of Bridge/Culvert/Weir
END DESCRIPTION:
XS GIS Cut Line= 6
       3091212.1       13945695.      3091162.85     13945329.61
      3091136.75     13945253.13      3091117.62     13945201.28
      3091096.67     13945157.16      3090914.73      13944756.5
#Sta/Elev= 30
  4524.9   103.6  4574.9   102.5  4614.9   100.4  4644.9    93.4  4664.9    86.7
  4684.9    83.7  4694.9    83.3  4734.9    83.5  4744.9    84.5  4774.9    90.9
  4794.9      94  4814.9    95.8  4864.9    95.5  4946.6   94.97  4957.9   95.98
  4974.8   90.34  4981.7    87.2  4984.5   84.82    4987    84.5    4991   81.07
    4999    80.6  5008.3   81.26  5012.6   84.79  5020.3   86.01  5027.4   89.17
  5030.4   93.81  5041.5   96.66    5066   95.33  5118.6    94.9  5518.6   107.3
#Mann= 7 ,-1 , 0
  4524.9     .08       0  4614.9    .026       0  4814.9      .1       0
  4864.9     .05       0  4957.9     .04       0  5041.5     .05       0
  5118.6     .14       0
#XS Ineff= 2 , 0
       0 4957.85   95.97 5041.59       0   95.97
Permanent Ineff=
       F       F
#Block Obstruct= 2 , 0
            4815   95.78
Bank Sta=4957.9,5041.5
XS Rating Curve= 0
Exp/Cntr=.7,.5

Type RM Length L Ch R = 5 ,4871.5  ,,,
BEGIN DESCRIPTION:
4873  4872.5  SHEET PILE WEIR 1700' U/S OF CYPRESSWOOD
Structure ID: K124-00-00-S1-1
END DESCRIPTION:
IW Pilot Flow=0
#Inline Weir SE= 17
    4959   95.32  4960.3   95.32  4964.9   95.26  4972.7   92.65    4984    92.3
  4984.4    87.5  4995.6   87.32 4995.61   82.65  5000.8   82.72    5001    87.2
  5012.1   87.61  5013.7   92.49  5023.7   92.81    5027    93.7  5028.9   94.66
  5034.9   95.22    5040   95.22
IW Dist,WD,Coef,Skew,MaxSub,Min_El,Is_Ogee,SpillHt,DesHd
11,1,3.087,0,.95,, 0 ,,,0,0,

Type RM Length L Ch R = 1 ,4870    ,10,10,10
XS GIS Cut Line= 4
      3091243.76      13945718.1      3091190.83     13945324.44
       3091120.6     13945146.85      3090949.77      13944763.1
#Sta/Elev= 30
    4490   103.8    4600   102.4    4620    99.6    4630    97.6    4660    88.1
    4670    85.7    4690    83.5    4740      84    4750    85.3    4770    90.1
    4790    93.5    4810    95.9  4887.2    95.5  4890.9   94.56  4914.9   95.31
  4960.5   95.15  4974.4   83.78  4978.8   81.65  4981.5   79.46  5019.2   80.41
  5023.7   84.15  5032.3   88.25  5044.4   96.56  5068.8   95.33 5072.18    96.1
 5174.85   96.22  5358.2   102.2  5438.2   103.6  5478.2   105.7  5498.2     106
#Mann= 7 ,-1 , 0
    4490     .08       0    4620    .026       0    4810      .1       0
  4887.2     .05       0  4960.5     .04       0  5044.4     .05       0
 5174.85     .14       0
#XS Ineff= 2 , 0
       0 4960.48   95.15 5044.43       0    95.5
Permanent Ineff=
       F       F
#Block Obstruct= 2 ,-1
    4630 4809.75      96    9000    9001      50
Bank Sta=4960.5,5044.4
XS Rating Curve= 0
Exp/Cntr=.7,.5

Type RM Length L Ch R = 1 ,4860    ,77.5,81,77.8
BEGIN DESCRIPTION:
Cross Section FIELD_DS
Located At: SHEET PILE WEIR 1700' U/S OF CYPRESSWOOD
END DESCRIPTION:
XS GIS Cut Line= 4
      3091243.76      13945718.1      3091190.83     13945324.44
       3091120.6     13945146.85      3090949.77      13944763.1
#Sta/Elev= 30
    4490   103.8    4600   102.4    4620    99.6    4630    97.6    4660    88.1
    4670    85.7    4690    83.5    4740      84    4750    85.3    4770    90.1
    4790    93.5    4810    95.9  4887.2    95.5  4890.9   94.56  4914.9   95.31
  4960.5   95.15  4974.4   83.78  4978.8   81.65  4981.5   79.46  5019.2   80.41
  5021.2   81.62  5023.7   84.15  5032.3   88.25  5044.4   96.56  5057.3   95.78
 5172.84   96.24  5358.2   102.2  5438.2   103.6  5478.2   105.7  5498.2     106
#Mann= 7 ,-1 , 0
    4490     .08       0    4620    .026       0    4810      .1       0
  4887.2     .05       0  4960.5     .04       0  5044.4     .05       0
 5172.84     .14       0
#XS Ineff= 2 , 0
       0 4960.48   95.15 5044.43       0    95.5
Permanent Ineff=
       F       F
#Block Obstruct= 2 ,-1
    4630 4809.75      96    9000    9001      50
Bank Sta=4960.5,5044.4
XS Rating Curve= 0
Exp/Cntr=.7,.5