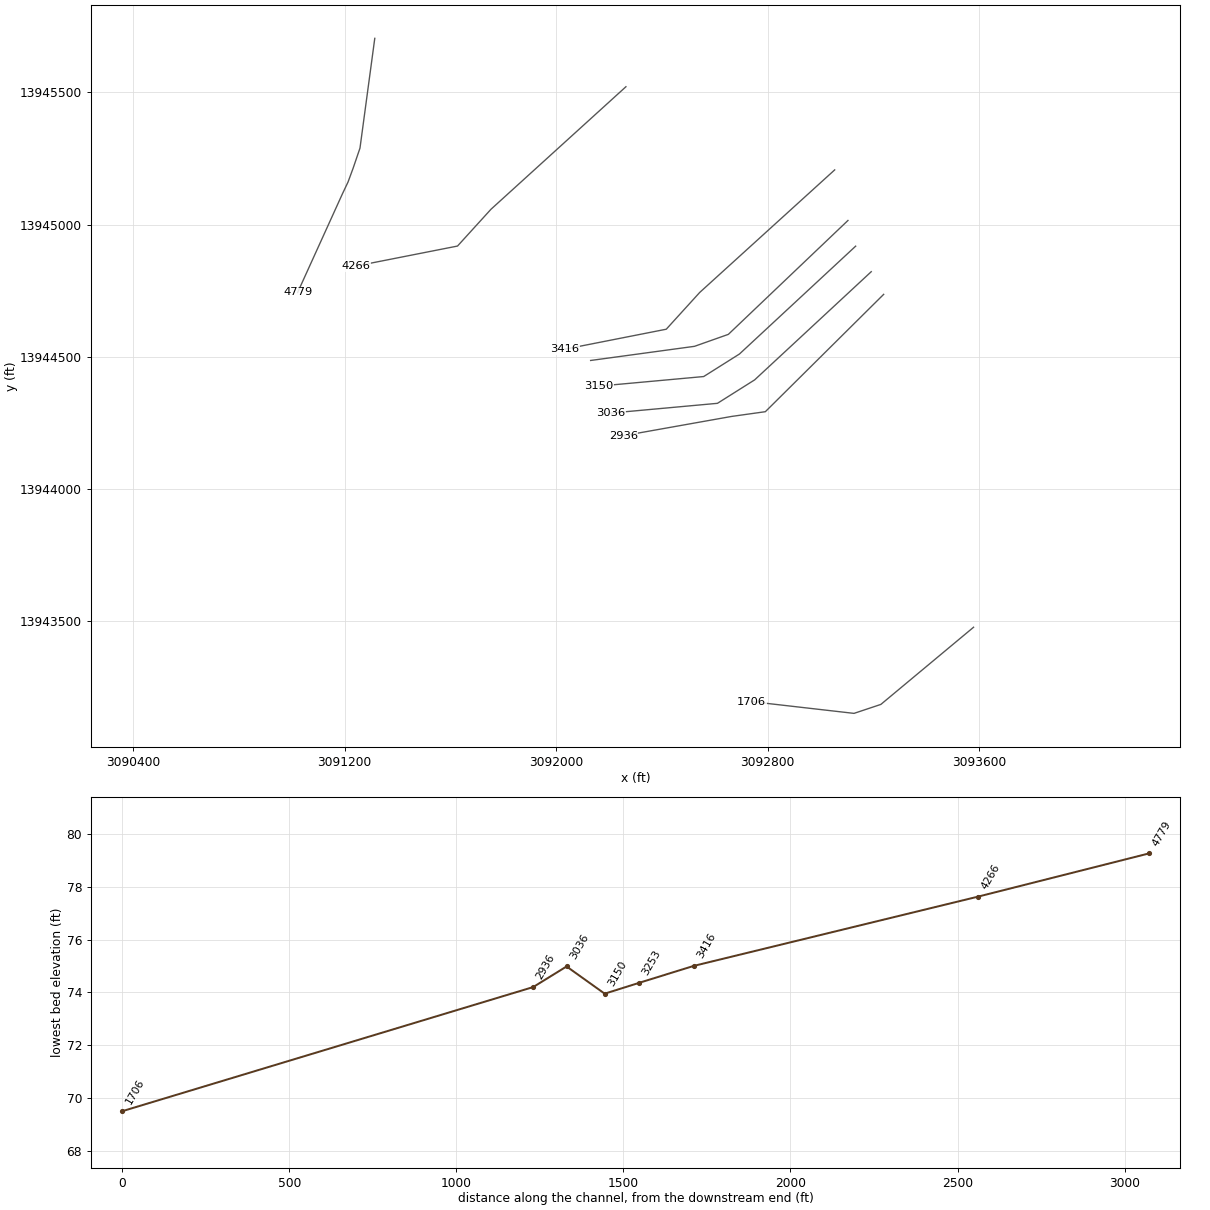
HEC-RAS study K124-00-00.prj: K124-00-00

--- K124-00-00.g05 (geometry) --- (continued)

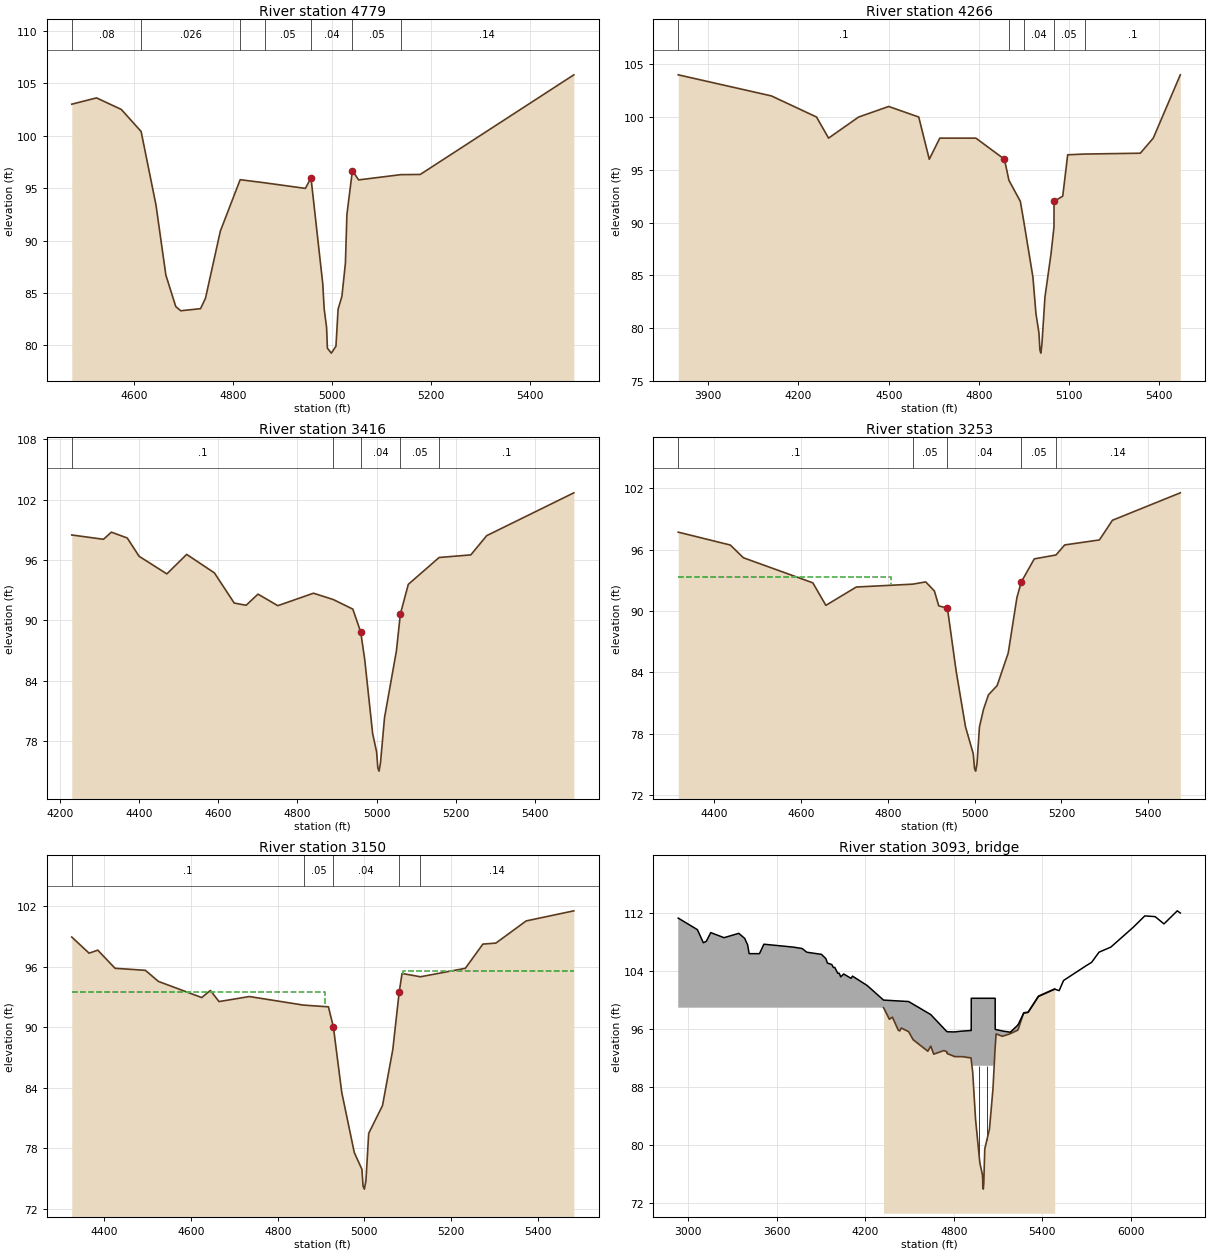
Type RM Length L Ch R = 1 ,4779    ,590.4,513,441.6
BEGIN DESCRIPTION:
Weir S1-1 DS-XS 1
END DESCRIPTION:
XS GIS Cut Line= 6
      3091314.31      13945704.3      3091258.38      13945289.3
      3091232.27      13945212.9      3091213.15       13945161.
      3091192.19      13945116.9      3091022.65      13944743.6
#Sta/Elev= 30
  4474.9     103  4524.9   103.6  4574.9   102.5  4614.9   100.4  4644.9    93.4
  4664.9    86.7  4684.9    83.7  4694.9    83.3  4734.9    83.5  4744.9    84.5
  4774.9    90.9  4814.9    95.8  4864.9    95.5  4946.6   94.97  4957.9   95.98
  4981.7   85.86  4984.5   83.48  4989.4   81.71    4991   79.73    4999   79.26
  5008.3   79.92  5012.6   83.45  5020.3   84.67  5027.4   87.83  5030.4   92.47
  5041.5   96.66  5054.1   95.78 5139.12   96.28 5178.51    96.3  5488.6   105.8
#Mann= 7 ,-1 , 0
  4474.9     .08       0  4614.9    .026       0  4814.9      .1       0
  4864.9     .05       0  4957.9     .04       0  5041.5     .05       0
 5139.12     .14       0
#Block Obstruct= 2 , 0
            4815   95.78
Bank Sta=4957.9,5041.5
XS Rating Curve= 0
Exp/Cntr=.3,.1

Type RM Length L Ch R = 1 ,4266    ,900,850,800
XS GIS Cut Line= 4
  3092263.73198813945521.3853048 3091753.501988413945058.0853048
 3091627.061988413944919.0853048 3091244.411988413944843.6853048
#Sta/Elev= 30
    3800     104    4110     102    4260     100    4300      98    4400     100
    4500     101    4600     100    4635      96    4670      98    4790      98
    4885      96    4900      94    4938      92    4950      90  4979.8   84.82
  4989.8   81.37  4999.8   79.54    5003   77.92    5006   77.62  5009.6   78.44
  5019.8   82.94  5039.8      87  5049.8   89.57    5050      92 5078.96    92.5
 5095.35   96.42  5151.4   96.49 5337.01   96.57    5380      98    5470     104
#Mann= 5 ,-1 , 0
    3800      .1       0    4900     .05       0    4950     .04       0
    5050     .05       0  5151.4      .1       0
Bank Sta=4885,5050
XS Rating Curve= 0
Exp/Cntr=.3,.1

Type RM Length L Ch R = 1 ,3416    ,197.8,163,122.3
BEGIN DESCRIPTION:
X1a-Interp
END DESCRIPTION:
XS GIS Cut Line= 4
      3093052.86       13945207.      3092542.63      13944743.7
      3092416.19      13944604.7      3092033.54      13944529.3
#Sta/Elev= 30
  4230.5   98.48  4310.5   98.05  4330.5   98.76  4370.5   98.18  4400.5   96.36
  4470.5   94.61  4520.5   96.55  4590.5   94.71  4640.5   91.71  4670.5   91.49
  4700.5    92.6  4750.5   91.45  4840.5   92.69  4890.5   92.06  4939.8   91.11
  4959.8   88.82  4969.8   86.11  4989.8   78.75  4999.8   76.92    5003    75.3
    5006      75  5009.6   75.82  5019.8   80.32  5049.8   86.95  5059.8   90.62
  5079.8   93.57  5157.6   96.24  5237.6    96.5  5277.6   98.41  5497.6  102.67
#Mann= 5 ,-1 , 0
  4230.5      .1       0  4890.5     .05       0  4959.8     .04       0
  5059.8     .05       0  5157.6      .1       0
Bank Sta=4959.8,5059.8
XS Rating Curve= 0
Exp/Cntr=.3,.1

Type RM Length L Ch R = 1 ,3253    ,87.8,103,119
BEGIN DESCRIPTION:
S1_CYPRESSWOOD-US-XS 4
END DESCRIPTION:
XS GIS Cut Line= 4
      3093103.05      13945015.8      3092650.89     13944585.25
      3092522.99     13944540.03      3092130.31     13944486.55
#Sta/Elev= 30
  4317.4    97.7  4437.4   96.44  4467.4    95.2  4627.4   92.75  4657.4   90.55
  4727.4   92.34  4857.4   92.62  4887.4   92.84  4907.4   91.95  4917.4    90.5
  4937.4   90.27 4957.36   84.16  4978.9   78.71 4996.87   76.05 4999.76   74.62
 5002.34   74.36 5005.48   75.07 5011.05   78.66 5020.29   80.37  5031.8   81.81
  5051.8   82.71  5077.4    85.9  5097.4   91.31  5107.4   92.83  5137.4   95.09
  5187.4   95.47  5207.4   96.45  5287.4   96.94  5317.4   98.86  5473.7  101.54
#Mann= 5 ,-1 , 0
  4317.4      .1       0  4857.4     .05       0  4937.4     .04       0
  5107.4     .05       0  5187.4     .14       0
#XS Ineff= 2 , 0
       0    4808   93.35               0
Permanent Ineff=
       F       F
Bank Sta=4937.4,5107.4
XS Rating Curve= 0
Exp/Cntr=.5,.3

Type RM Length L Ch R = 1 ,3150    ,113.1,114,113.4
BEGIN DESCRIPTION:
Upstream Section of Bridge/Culvert/Weir
END DESCRIPTION:
XS GIS Cut Line= 4
      3093132.17      13944918.7      3092692.88       13944511.
       3092557.7      13944425.8      3092159.43      13944389.4
#Sta/Elev= 30
  4324.5   98.95  4364.5   97.35  4384.5   97.65  4424.5   95.85  4494.5   95.65
  4524.5   94.55  4624.5   92.95  4644.5   93.65  4664.5   92.55  4734.5   93.05
  4859.5    92.2    4917   92.03 4928.41   90.05  4947.8   83.54  4976.8   77.57
  4994.3   75.92    4997   74.25    5000   73.95  5003.6   74.77    5010   79.48
  5041.9   82.24  5065.7   87.81  5080.3   93.47    5087   95.34  5129.5   95.01
  5233.1   95.85  5273.6   98.25  5303.6   98.35  5373.6  100.55  5483.6  101.55
#Mann= 5 ,-1 , 0
  4324.5      .1       0  4859.5     .05       0 4928.41     .04       0
  5080.3     .05       0  5129.5     .14       0
#XS Ineff= 2 , 0
       0  4908.3    93.5  5090.3       0   95.58
Permanent Ineff=
       F       F
Bank Sta=4928.41,5080.3
XS Rating Curve= 0
Exp/Cntr=.5,.3

Type RM Length L Ch R = 3 ,3093    ,,,
BEGIN DESCRIPTION:
3140 CYPRESSWOOD RD.
Structure ID: K124-00-00-S1
END DESCRIPTION:
Bridge Culvert--1,0,-1,-1, 0
Deck Dist Width WeirC Skew NumUp NumDn MinLoCord MaxHiCord MaxSubmerge Is_Ogee
10,92,2.6,0, 71, 71, , , .95, 0, ,,,
  2934.5  3064.5  3104.5  3124.5  3154.5  3244.5  3344.5  3384.5  3404.5  3414.5
  3484.5  3514.5  3714.5  3774.5  3804.5  3904.5  3934.5  3944.5  3974.5  3984.5
  3994.5  4014.5  4024.5  4034.5  4054.5  4104.5  4114.5  4214.5  4324.5  4494.5
  4644.5  4751.2  4754.5  4755.1  4804.2  4806.8  4853.9  4859.5    4917  4918.3
 4918.39  4918.5  5080.5 5080.61  5081.1    5087  5129.5  5135.2  5178.8  5183.5
  5231.2  5233.1  5237.6  5241.2  5242.4  5273.6  5303.6  5373.6  5483.6  5513.6
  5543.6  5693.6  5733.6  5783.6  5863.6  6013.6  6093.6  6163.6  6223.6  6313.6
  6334.1
   111.3   109.7   107.9   108.1   109.3   108.6   109.2   108.5   107.6   106.4
   106.4   107.7   107.3   107.1   106.6   106.3   105.7   105.1   104.9   104.5
   104.5   103.7   103.7   103.2   103.6     103   103.3     102     100    99.8
      98    95.7   95.65   95.64   95.61   95.62   95.72   95.73   95.81   95.81
   95.81  100.25  100.25   96.85   95.96   95.93   95.75   95.72   95.59   95.58
    96.5   96.56   96.69    96.8    96.9    98.2    98.3   100.5   101.5   101.3
   102.7   104.7   105.2   106.6   107.3     110   111.6   111.5   110.5   112.3
     112
                                                                                
                                                                                
                                                                                
                                                                   90.95   90.95
   90.95   90.95   90.95   90.95   90.95   90.95   90.95   90.95   90.95   90.95
   90.95   90.95   90.95   90.95   90.95   90.95    98.3   100.5   101.5   101.3
   102.7   104.7   105.2   106.6   107.3     110   111.6   111.5   110.5   112.3
     112
  2934.5  3064.5  3104.5  3124.5  3154.5  3244.5  3344.5  3384.5  3404.5  3414.5
  3484.5  3514.5  3714.5  3774.5  3804.5  3904.5  3934.5  3944.5  3974.5  3984.5
  3994.5  4014.5  4024.5  4034.5  4054.5  4104.5  4114.5  4214.5  4324.5  4494.5
  4644.5  4751.2  4754.5  4755.1  4804.2  4806.8  4853.9  4859.5    4917  4918.3
 4918.39  4918.5  5080.5 5080.61  5081.1    5087  5129.5  5135.2  5178.8  5183.5
  5231.2  5233.1  5237.6  5241.2  5242.4  5273.6  5303.6  5373.6  5483.6  5513.6
  5543.6  5693.6  5733.6  5783.6  5863.6  6013.6  6093.6  6163.6  6223.6  6313.6
  6334.1
   111.3   109.7   107.9   108.1   109.3   108.6   109.2   108.5   107.6   106.4
   106.4   107.7   107.3   107.1   106.6   106.3   105.7   105.1   104.9   104.5
   104.5   103.7   103.7   103.2   103.6     103   103.3     102     100    99.8
      98    95.7   95.65   95.64   95.61   95.62   95.72   95.73   95.81   95.81
   95.81  100.25  100.25   96.85   95.96   95.93   95.75   95.72   95.59   95.58
    96.5   96.56   96.69    96.8    96.9    98.2    98.3   100.5   101.5   101.3
   102.7   104.7   105.2   106.6   107.3     110   111.6   111.5   110.5   112.3
     112
                                                                                
                                                                                
                                                                                
                                                                   90.95   90.95
   90.95   90.95   90.95   90.95   90.95   90.95   90.95   90.95   90.95   90.95
   90.95   90.95   90.95   90.95   90.95   90.95    98.3   100.5   101.5   101.3
   102.7   104.7   105.2   106.6   107.3     110   111.6   111.5   110.5   112.3
     112
Pier Skew, UpSta & Num, DnSta & Num=  ,4972, 2 ,4972, 2 , 0 , 0 , 0 ,,
     1.4     1.4
   77.36   91.12
     1.4     1.4
   78.48   92.24
Pier Skew, UpSta & Num, DnSta & Num=  ,5024.9, 2 ,5024.9, 2 , 0 , 0 , 0 ,,
     1.4     1.4
   79.66   91.17
     1.4     1.4
   80.78   92.29
BR Coef= 1 , 1 , 1 ,1.25, 0 ,,,.8,0,2,0,
WSPro=,,,, 1 ,,,, 0 ,,,, 0 ,,,,-1 ,-1 ,-1 , 0 , 0 , 0 , 0 , 0
BR U #Sta/Elev= 60
  4324.5   98.95  4364.5   97.35  4384.5   97.65  4424.5   95.85  4434.5   95.75
  4444.5   96.15  4494.5   95.65  4524.5   94.55  4624.5   92.95  4644.5   93.65
  4664.5   92.55  4734.5   93.05  4751.2   92.88  4754.5   92.85  4755.1   92.63
  4791.2   92.34  4804.2   92.23  4806.8   92.21  4853.9    92.2  4859.5    92.2
    4917   92.03 4928.41   90.05 4928.53   90.01  4928.6   89.98  4947.8   83.54
  4972.8   78.39  4976.8   77.57  4994.3   75.92  4995.9    75.3    4997   74.25
    5000   73.95  5000.1   73.97  5003.6   74.77  5004.1   75.26    5010   79.48
  5027.3   80.98  5041.9   82.24  5065.7   87.81 5074.77   91.33 5074.89   91.37
    5075   91.42  5080.3   93.47 5080.39    93.5  5080.5   93.53 5080.61   93.56
  5081.1   93.69    5087   95.34  5129.5   95.01  5135.2   95.05  5178.8   95.33
  5183.5   95.38  5231.2   95.83  5233.1   95.85  5237.6   96.03  5241.2   96.25
  5242.4   96.33  5273.6   98.25  5303.6   98.35  5373.6  100.55  5483.6  101.55
BR U #Mann= 7
  4324.5      .1  4859.5     .05 4928.41     .02  4972.8     .04  5027.3     .02
  5080.3     .05  5129.5     .14
BR D #Sta/Elev= 59
  4324.5   98.95  4364.5   97.35  4384.5   97.65  4424.5   95.85  4434.5   95.75
  4444.5   96.15  4494.5   95.65  4524.5   94.55  4624.5   92.95  4644.5   93.65
  4664.5   92.55  4734.5   93.05  4751.2   92.88  4754.5   92.85  4755.1   92.63
  4791.2   92.34  4804.2   92.23  4806.8   92.21  4853.9    92.2  4859.5    92.2
    4917   92.03 4928.41   91.08 4928.53   91.04  4928.6   91.01  4947.8   84.57
  4972.8   79.42  4976.8    78.6  4994.3   76.95  4995.9   76.33    4997   75.28
    5000   74.98  5000.1      75  5003.6    75.8  5004.1   76.29    5010   80.51
  5027.3   82.01  5041.9   83.27  5065.7   88.84 5074.77   92.36 5074.89    92.4
    5075   92.45 5080.39    93.5  5080.5   93.53 5080.61   93.56  5081.1   93.69
    5087   95.34  5129.5   95.01  5135.2   95.05  5178.8   95.33  5183.5   95.38
  5231.2   95.83  5233.1   95.85  5237.6   96.03  5241.2   96.25  5242.4   96.33
  5273.6   98.25  5303.6   98.35  5373.6  100.55  5483.6  101.55
BR D #Mann= 7
  4324.5      .1  4859.5     .05 4928.41     .02  4972.8     .04  5027.3     .02
 5080.39     .05  5129.5     .14
BR D Banks=,5080.39
BC Design=,, 0 ,, 0 ,,,,,,
BC HTab HWMax=101.55

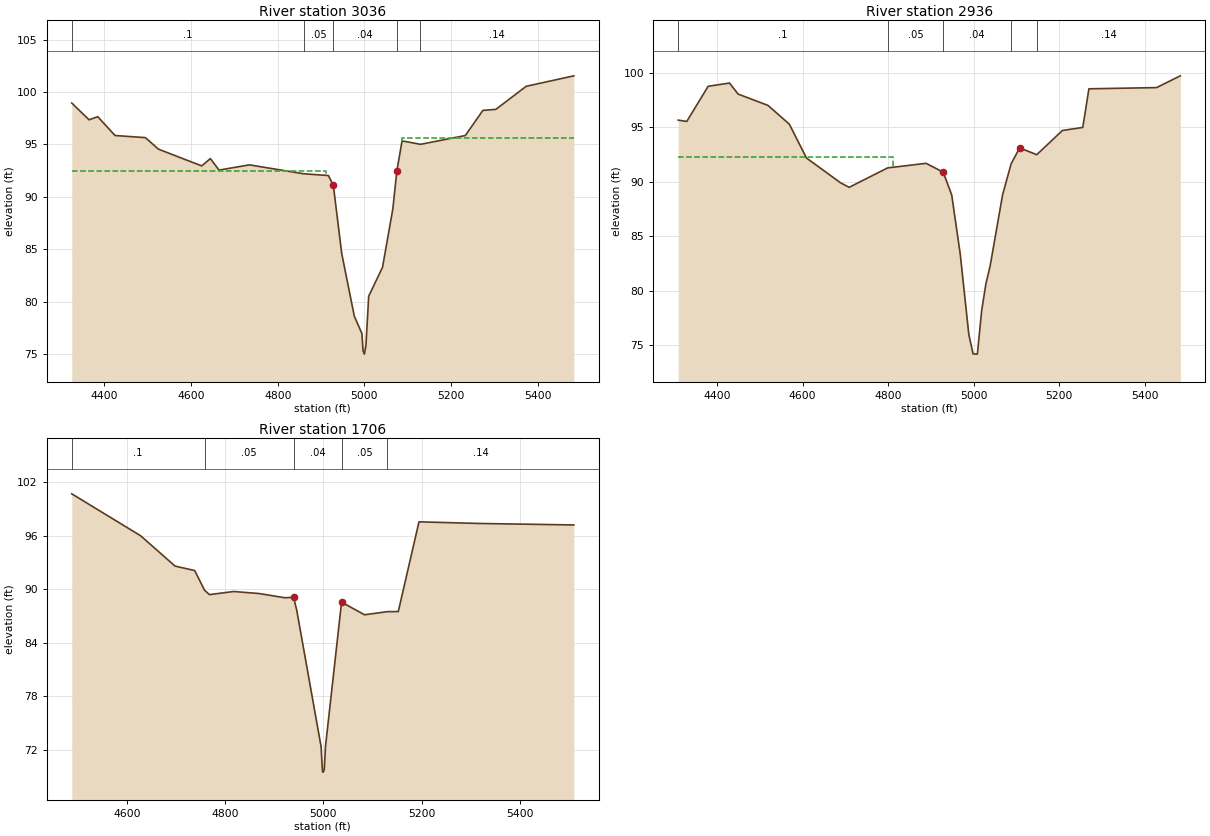
Type RM Length L Ch R = 1 ,3036    ,127,100,66.3
BEGIN DESCRIPTION:
Downstream Section of Bridge/Culvert/Weir
END DESCRIPTION:
XS GIS Cut Line= 4
      3093191.11      13944822.2      3092750.46     13944413.31
      3092609.63     13944324.55      3092206.58      13944287.7
#Sta/Elev= 30
  4324.5   98.95  4364.5   97.35  4384.5   97.65  4424.5   95.85  4494.5   95.65
  4524.5   94.55  4624.5   92.95  4644.5   93.65  4664.5   92.55  4734.5   93.05
  4859.5    92.2    4917   92.03 4928.41   91.08  4947.8   84.57  4976.8    78.6
  4994.3   76.95    4997   75.28    5000   74.98  5003.6    75.8    5010   80.51
  5041.9   83.27  5065.7   88.84    5075   92.45    5087   95.34  5129.5   95.01
  5233.1   95.85  5273.6   98.25  5303.6   98.35  5373.6  100.55  5483.6  101.55
#Mann= 5 ,-1 , 0
  4324.5      .1       0  4859.5     .05       0 4928.41     .04       0
    5075     .05       0  5129.5     .14       0
#XS Ineff= 2 , 0
       0 4911.63    92.5 5086.97       0   95.58
Permanent Ineff=
       F       F
Bank Sta=4928.41,5075
XS Rating Curve= 0
Exp/Cntr=.5,.3

Type RM Length L Ch R = 1 ,2936    ,1229.9,1230,1240
BEGIN DESCRIPTION:
S1_CYPRESSWOOD-DS-XS 1
This section is LIDAR generated.
END DESCRIPTION:
XS GIS Cut Line= 4
      3093238.04      13944736.5      3092790.73     13944292.91
      3092662.98     13944274.98      3092253.51     13944202.02
#Sta/Elev= 30
  4308.9   95.65  4328.9   95.53  4378.9   98.75  4428.9   99.05  4448.9   98.04
  4518.9      97  4568.9   95.28  4608.9   92.18  4688.9    89.9  4708.9   89.49
  4798.9   91.27  4888.9   91.69  4928.9   90.88  4948.9   88.79  4968.9   83.34
  4988.9      76  4998.9   74.22  5008.9    74.2  5018.9   78.17  5028.9   80.65
  5038.9    82.3  5067.9    88.8  5087.9   91.65  5107.9    93.1  5147.9   92.48
  5207.9    94.7  5255.6   94.98 5269.92   98.52 5428.27   98.63  5483.8   99.71
#Mann= 5 ,-1 , 0
  4308.9      .1       0  4798.9     .05       0  4928.9     .04       0
  5087.9     .05       0  5147.9     .14       0
#XS Ineff= 2 , 0
       0    4811    92.3               0
Permanent Ineff=
       F       F
Bank Sta=4928.9,5107.9
XS Rating Curve= 0
Exp/Cntr=.3,.1

Type RM Length L Ch R = 1 ,1706    ,0,0,0
BEGIN DESCRIPTION:
Cross Section K124-00-00-X1
END DESCRIPTION:
XS GIS Cut Line= 4
      3093577.84      13943478.1      3093227.44      13943186.4
      3093125.88      13943152.5      3092738.41      13943196.9
#Sta/Elev= 25
  4488.3   100.7  4628.3      96  4698.3    92.6  4738.3    92.1  4758.3    89.9
  4768.3    89.4  4817.6   89.75  4869.4   89.52  4921.6   89.05  4939.5    89.1
  4945.8   87.66  4995.4   72.35  4997.6   70.07  4998.5    69.5  5000.2   69.53
  5001.9   69.84  5002.4   70.32  5004.3   72.38    5037   88.55  5083.8   87.14
  5129.9   87.49 5152.34    87.5 5194.47   97.56 5314.65   97.38  5509.4   97.21
#Mann= 5 ,-1 , 0
  4488.3      .1       0  4758.3     .05       0  4939.5     .04       0
    5037     .05       0  5129.9     .14       0
Bank Sta=4939.5,5037
XS Rating Curve= 0
Exp/Cntr=.3,.1

Chan Stop Cuts=-1